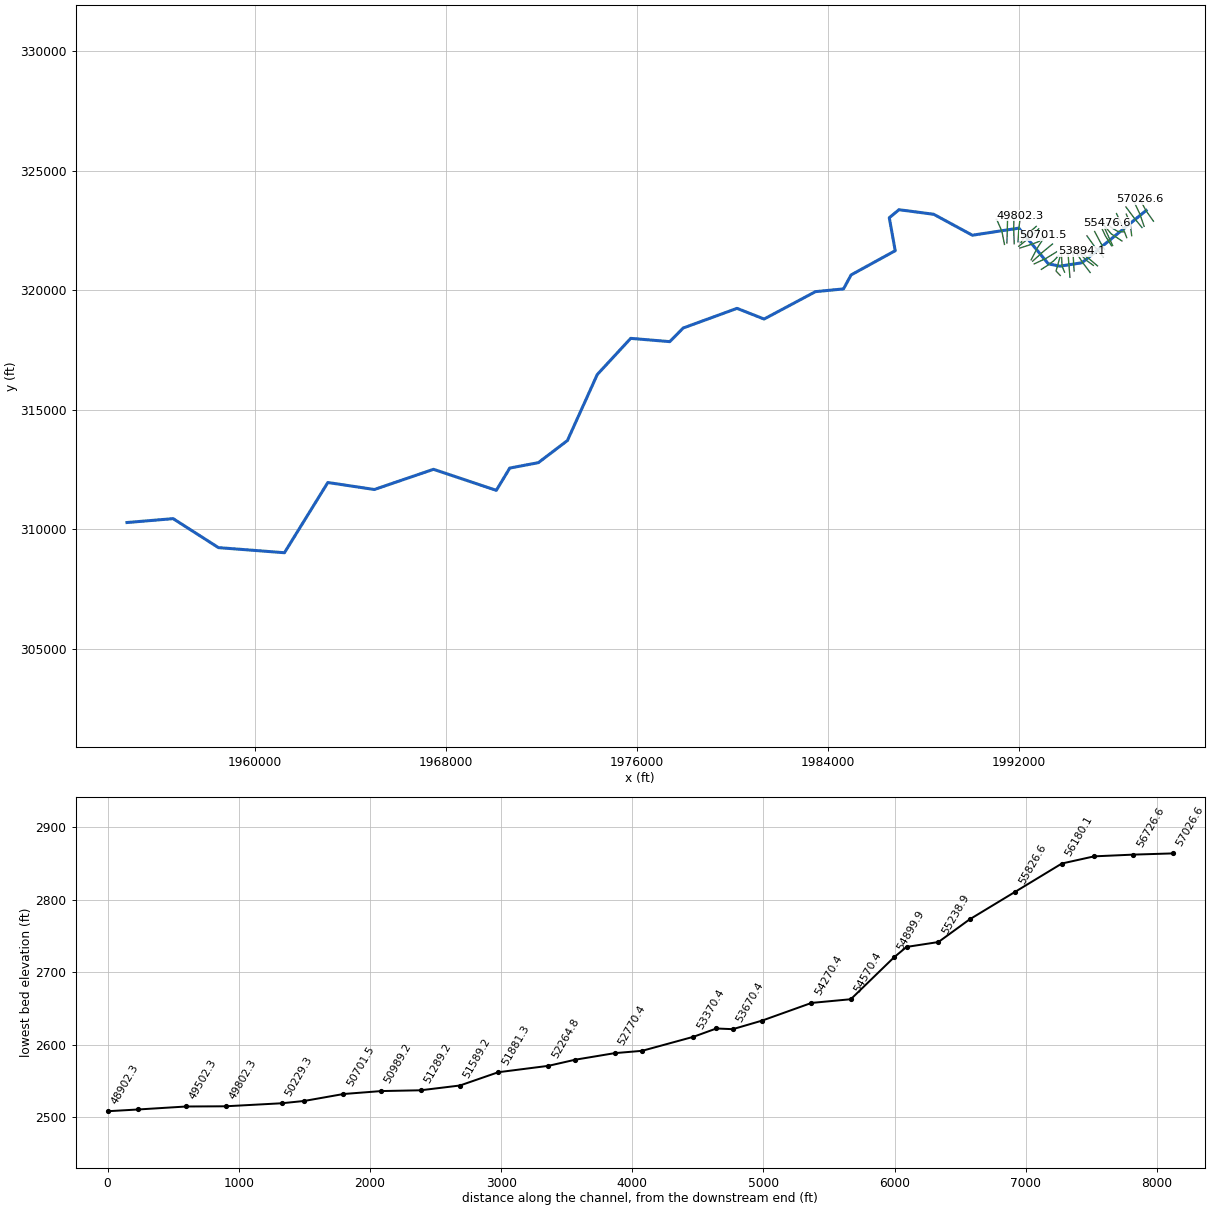
--- LaurelCrk.prj (project) ---

Proj Title=LaurelCrk
Current Plan=p01
Default Exp/Contr=0,0
English Units
Geom File=g01
Flow File=f01
Plan File=p01
BEGIN DESCRIPTION:
END DESCRIPTION:
DSS Export Rating Curves= 0
DSS Export Rating Curve Sorted= 0
DSS Export Volume Flow Curves= 0
DXF OffsetX= 0
DXF OffsetY= 0
DXF ScaleX= 0
DXF ScaleY= 0

--- LaurelCrk.p01 (plan) ---

Plan Title=Floodplain
Program Version=4.00
Geom File=g01
Flow File=f01
K Sum by GR=0
Std Step Tol=0.01
Critical Tol=0.01
Num of Std Step Trials=20
Max Error Tol=0.3
Flow Tol Ratio=0.001
Split Flow NTrial=30
Split Flow Tol=0.02
Split Flow Ratio=0.02
Log Output Level=0
Friction Slope Method=1
Unsteady Friction Slope Method=2
Unsteady Bridges Friction Slope Method=1
Global Log Level=0
CheckData=False
Run HTab=0
Run UNet=0
Run PostProcess=0
UNET Theta=0
UNET Theta Warmup=0
UNET ZTol=0
UNET ZSATol=0
UNET MxIter=0
UNET MaxInSteps=0
UNET DtIC=0
UNET DtMin=0
UNET MaxCRTS=0
UNET WFStab=0
UNET SFStab=0
UNET WFX=0
UNET SFX=0
UNET DSS MLevel=0
UNET DZMax Abort=0
UNET Convert EG Bridges=0
UNET Use Existing IB Tables=0
UNET Froude Limit=0
UNET Froude Power=0
Write IC File=0
Echo Input=False
Echo Output=False
Write Detailed=0

--- LaurelCrk.f01 (steady flow) ---

Flow Title=NFF Regression Equation
Program Version=4.10
Number of Profiles= 1
Profile Names=P100yr
River Rch & RM=LaurelCrk,Main            ,57026.6
417.3588
River Rch & RM=LaurelCrk,Main            ,56726.6
417.3588
River Rch & RM=LaurelCrk,Main            ,56426.6
539.7373
River Rch & RM=LaurelCrk,Main            ,55826.6
564.1575
River Rch & RM=LaurelCrk,Main            ,53370.4
     606
River Rch & RM=LaurelCrk,Main            ,52978.7
840.4063
River Rch & RM=LaurelCrk,Main            ,52264.8
845.8977
River Rch & RM=LaurelCrk,Main            ,51881.3
989.2965
River Rch & RM=LaurelCrk,Main            ,50229.3
1008.596
River Rch & RM=LaurelCrk,Main            ,49802.3
1119.139
River Rch & RM=LaurelCrk,Main            ,46202.3
1181.804
River Rch & RM=LaurelCrk,Main            ,45218
1312.934
River Rch & RM=LaurelCrk,Main            ,42902.3
1453.656
River Rch & RM=LaurelCrk,Main            ,39217.7
1601.968
River Rch & RM=LaurelCrk,Main            ,36604.6
1766.725
River Rch & RM=LaurelCrk,Main            ,34202.3
1961.884
River Rch & RM=LaurelCrk,Main            ,32082.1
2009.168
River Rch & RM=LaurelCrk,Main            ,28640.9
2225.839
River Rch & RM=LaurelCrk,Main            ,28202.3
2910.688
River Rch & RM=LaurelCrk,Main            ,26952.7
3072.073
River Rch & RM=LaurelCrk,Main            ,22932.1
3365.426
River Rch & RM=LaurelCrk,Main            ,18764.6
 3518.67
River Rch & RM=LaurelCrk,Main            ,10758.9
3892.903
Boundary for River Rch & Prof#=LaurelCrk,Main            , 1
Up Type= 0
Dn Type= 3
Dn Slope=0.025703
DSS Import GetInterval= 0
DSS Import GetPeak= 0
DSS Import FillOption= 0

--- LaurelCrk.g01 (geometry) ---

Geom Title=USGS 10m DEM
Program Version=4.10

River Reach=LaurelCrk       ,Main
Reach XY= 30
     1997345.219      323344.545     1994655.983      321155.309
     1993731.161      321013.218     1993247.667      321109.917
     1992012.679      322604.147     1990065.705      322308.087
     1988444.966      323185.056     1986992.933      323375.762
     1986586.538      323039.287     1986834.854      321659.953
     1984986.266      320646.198     1984669.923      320060.994
     1983496.312      319946.411     1981342.967      318800.288
     1980207.867      319247.006     1977954.645      318423.841
     1977392.146      317854.397     1975755.401      317991.063
     1974355.687      316477.661     1973105.687      313715.508
     1971886.937      312788.425     1970690.756       312562.73
     1970128.257      311630.438     1967496.312      312510.647
      1965019.34       311665.76     1963070.965      311958.563
     1961253.257      309019.328     1958489.368      309232.869
     1956591.358      310445.922       1954658.2         310283.

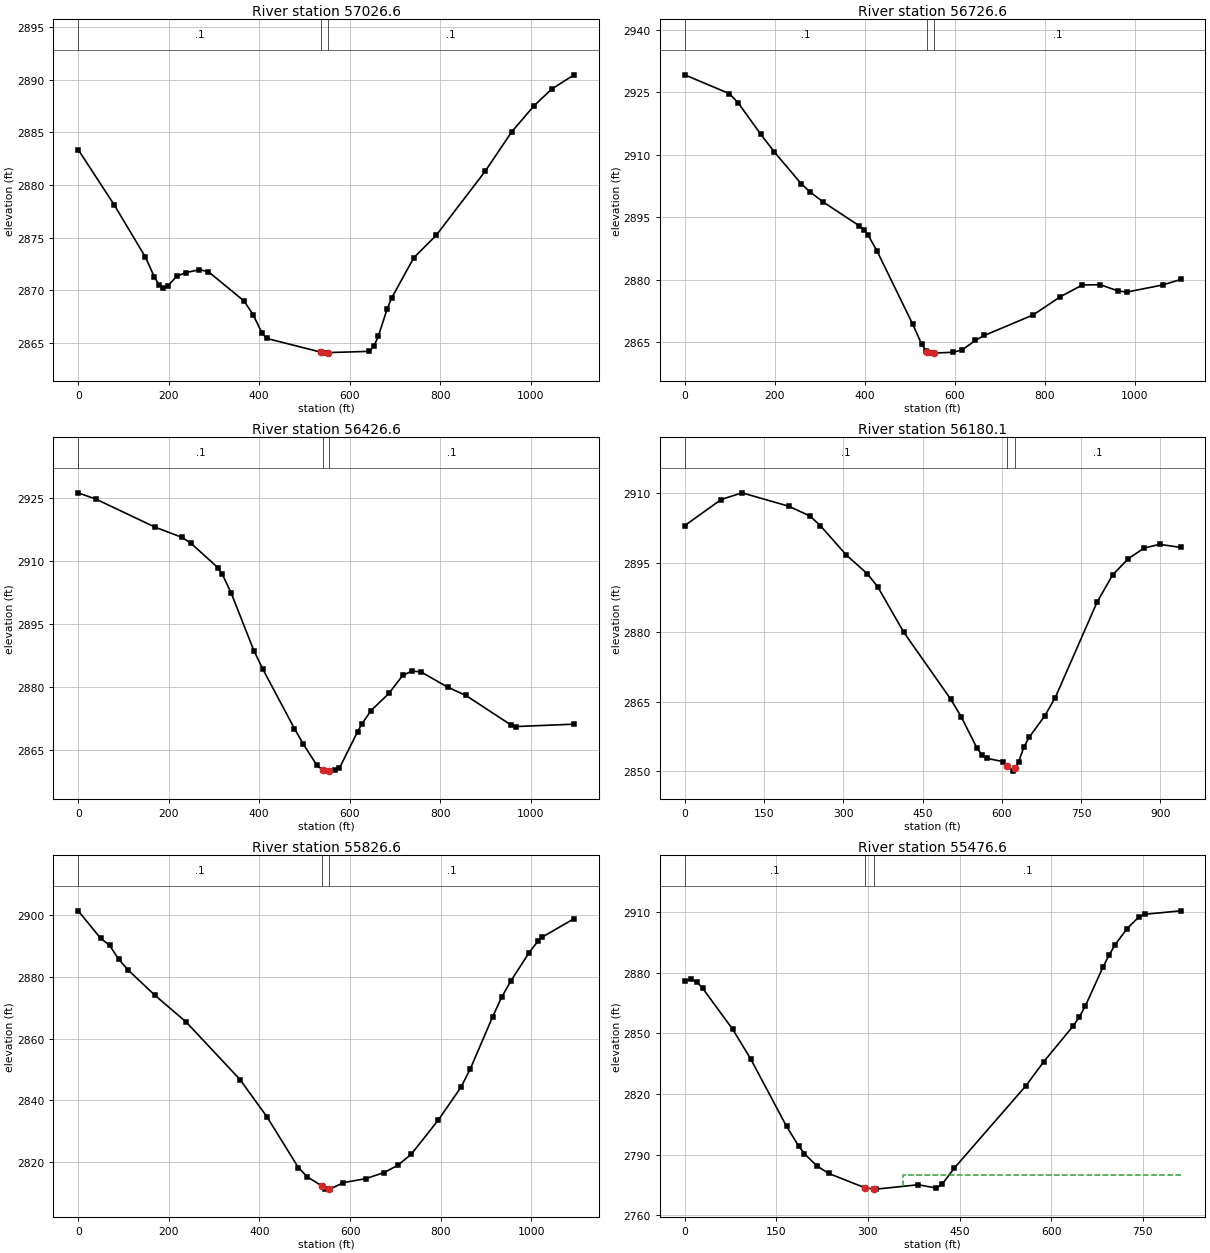
Type RM Length L Ch R = 1 ,57026.6 ,306.3,299.9,298.9
XS GIS Cut Line= 3
       1997651.4      322893.444     1997337.049      323338.778
     1997077.056      323824.666
#Sta/Elev= 30
       0 2883.35    79.3 2878.13   148.7 2873.14   168.5 2871.25   178.4 2870.54
   188.3 2870.22   198.2 2870.42     218 2871.35   237.9 2871.68   267.6 2871.95
   287.4 2871.78   366.7 2868.98   386.5 2867.69   406.4 2865.95   416.3 2865.44
   537.6 2864.12   545.1 2864.04   552.6 2864.09   643.5 2864.21   653.4 2864.69
   663.2 2865.62   682.9 2868.24   692.7 2869.27   741.9  2873.1   791.1 2875.21
   899.4 2881.29   958.4 2885.05  1007.6 2887.52    1047 2889.11  1096.2 2890.45
#Mann= 3 , 0 , 0
       0      .1       0   537.6    .045       0   552.6      .1       0
Bank Sta=537.6,552.6
XS Rating Curve= 0 ,0
Exp/Cntr=0.3,0.1

Type RM Length L Ch R = 1 ,56726.6 ,291.9,299.8,304.2
XS GIS Cut Line= 3
     1997259.269      322681.566      1997080.33      323198.068
     1996842.294      323699.477
#Sta/Elev= 30
       0 2929.13    99.4 2924.61   119.3 2922.34     169 2914.87   198.8 2910.68
   258.4 2903.06   278.3 2901.07   308.1 2898.59   387.6 2892.94   397.5 2892.03
   407.5  2890.7   427.4 2886.85   506.9 2869.25   526.7 2864.46   536.7 2862.85
   539.1 2862.74   546.6 2862.38   554.1 2862.39   596.2 2862.59     616 2863.12
   645.7 2865.43   665.6 2866.61   774.6 2871.57     834 2875.88   883.6 2878.74
   923.3 2878.79   962.9 2877.29   982.7 2877.04    1062 2878.73  1101.7 2880.04
#Mann= 3 , 0 , 0
       0      .1       0   539.1    .045       0   554.1      .1       0
Bank Sta=539.1,554.1
XS Rating Curve= 0 ,0
Exp/Cntr=0.3,0.1

Type RM Length L Ch R = 1 ,56426.6 ,252.8,246.4,241.1
XS GIS Cut Line= 3
     1997171.864      322628.013     1996825.608      323052.124
     1996497.577      323491.768
#Sta/Elev= 30
       0 2926.23    39.8  2924.7   169.2 2918.09     229 2915.64   248.9 2914.26
   308.6 2908.42   318.6 2906.81   338.5 2902.27   388.2 2888.66   408.1 2884.23
   477.8 2870.12   497.7 2866.37   527.6 2861.36     540 2860.24   547.5 2859.98
     555    2860   567.4 2860.14   577.4 2860.73   617.3 2869.34   627.3 2871.28
   647.2 2874.39   687.1 2878.54     717 2882.76     737 2883.78     757 2883.63
   816.8 2879.95   856.7    2878   956.4 2870.97   966.4 2870.59    1096 2871.16
#Mann= 3 , 0 , 0
       0      .1       0     540    .045       0     555      .1       0
Bank Sta=540,555
XS Rating Curve= 0 ,0
Exp/Cntr=0.3,0.1

Type RM Length L Ch R = 1 ,56180.1 ,354.5,353.6,354.3
XS GIS Cut Line= 3
     1996739.648      322288.846     1996673.044      322817.512
     1996512.779      323190.076
#Sta/Elev= 30
       0 2903.04    69.1 2908.68   108.5 2910.12   197.4 2907.21   236.8 2905.13
   256.6 2903.05   305.9 2896.69   345.4 2892.69   365.1 2889.87   414.4 2880.07
   503.2 2865.63     523 2861.86   552.6 2855.15   562.5 2853.59   572.4 2852.82
   602.1 2852.14   610.1 2851.22   621.9 2850.08   625.1 2850.71   631.8 2852.04
   641.7 2855.24   651.6 2857.34   681.2 2861.98     701 2865.89   780.1 2886.48
   809.8 2892.42   839.5 2895.91   869.2  2898.2   898.8 2899.01   938.4 2898.34
#Mann= 3 , 0 , 0
       0      .1       0   610.1    .045       0   625.1      .1       0
Bank Sta=610.1,625.1
XS Rating Curve= 0 ,0
Exp/Cntr=0.3,0.1

Type RM Length L Ch R = 1 ,55826.6 ,334.7,349.8,363.3
XS GIS Cut Line= 3
     1996530.921      322206.931     1996336.896       322716.65
     1996103.885      323213.832
#Sta/Elev= 30
       0 2901.38    49.6 2892.46    69.4 2890.18    89.2 2885.74   109.1 2882.36
   168.6 2874.13     238 2865.41     357 2846.77   416.5 2834.69   485.9 2818.27
   505.7 2815.23   537.9  2812.3   545.4 2811.44   552.9 2811.32   555.4 2811.28
   585.3 2813.38   635.2 2814.69   675.2 2816.66   705.1 2818.98   735.1 2822.59
     795 2833.71   844.9 2844.32   864.9 2850.07   914.8 2867.15   934.7 2873.48
   954.7 2878.64   994.6 2887.76  1014.6 2891.57  1024.6 2892.92  1094.5 2898.85
#Mann= 3 , 0 , 0
       0      .1       0   537.9    .045       0   552.9      .1       0
Bank Sta=537.9,552.9
XS Rating Curve= 0 ,0
Exp/Cntr=0.3,0.1

Type RM Length L Ch R = 1 ,55476.6 ,238.9,237.7,236.5
XS GIS Cut Line= 4
     1996382.682      322446.262     1996148.668      322471.466
     1995879.359      322631.431     1995692.507        322816.6
#Sta/Elev= 30
       0 2875.76     9.8 2876.69    19.6  2875.5    29.4  2872.3    78.5 2852.05
   107.9 2837.44   166.7 2804.01   186.3 2794.41   196.1 2790.42   215.8  2784.6
   235.4 2780.75   294.8 2773.65   309.8 2773.03   313.7 2772.96   382.2 2775.13
   411.6  2773.5   421.4  2775.4   440.9 2783.22   558.4 2824.05   587.6 2835.96
   636.3 2853.81     646 2858.14   655.8 2863.57     685 2883.02   694.8  2888.8
   704.5 2893.86     724 2901.79   743.5  2907.6   753.2 2908.89   811.7  2910.6
#Mann= 3 , 0 , 0
       0      .1       0   294.8    .045       0   309.8      .1       0
#XS Ineff= 2 , 0
                          357.47         2780.19
Permanent Ineff=
       F       F
Bank Sta=294.8,309.8
XS Rating Curve= 0 ,0
Exp/Cntr=0.3,0.1

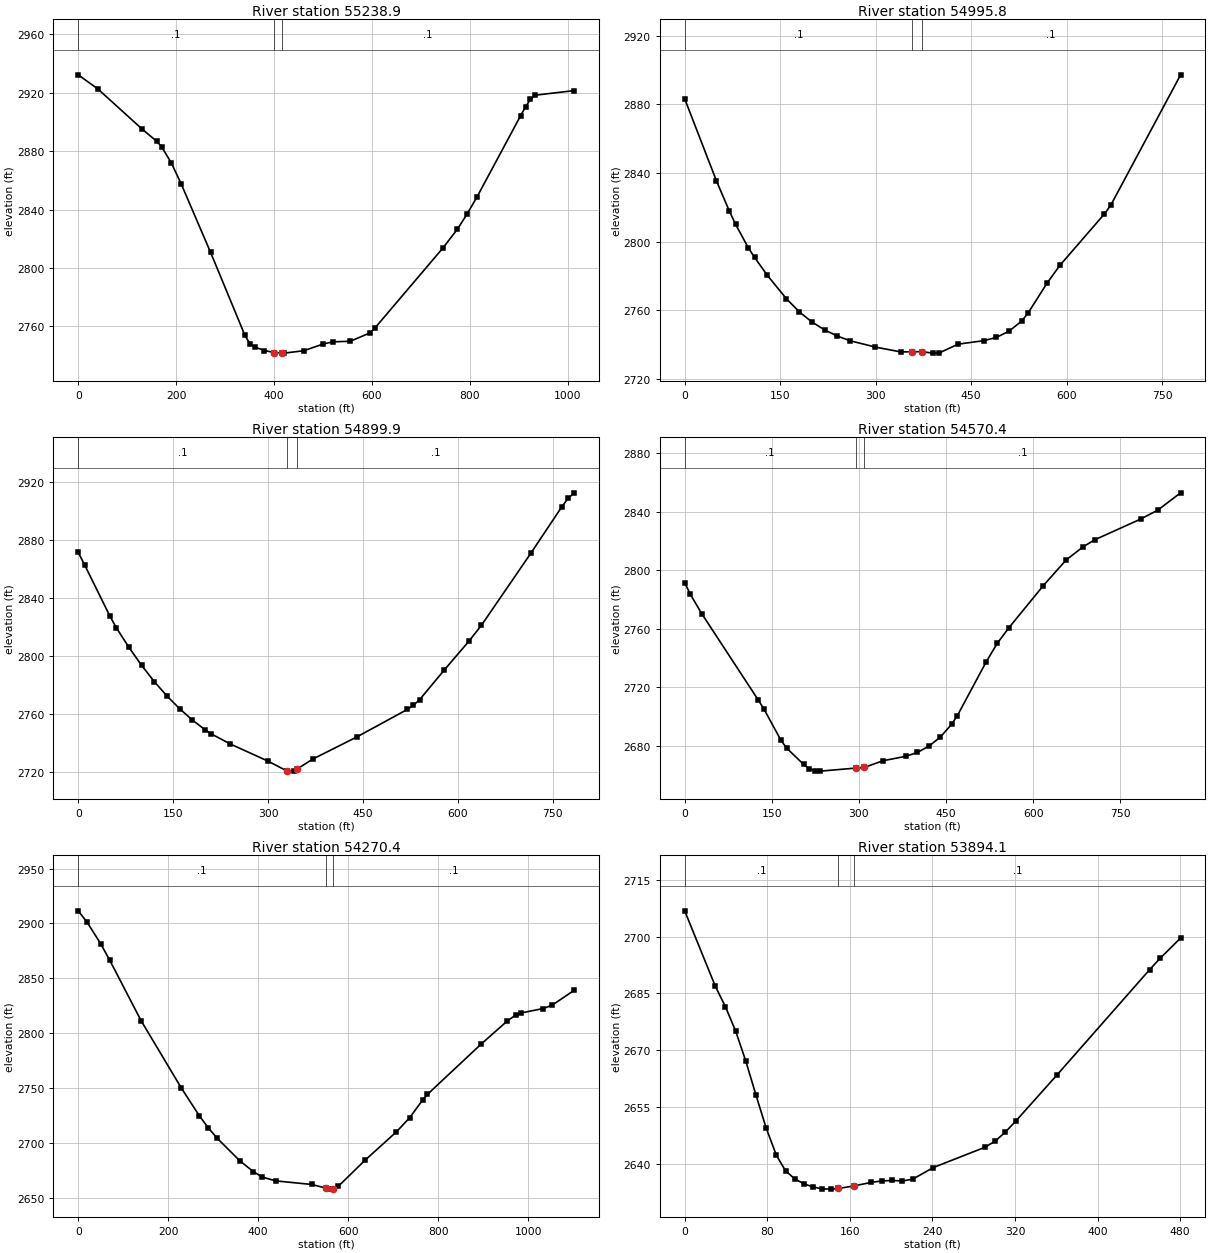
Type RM Length L Ch R = 1 ,55238.9 ,252.3,243,230.5
XS GIS Cut Line= 4
     1996331.496      322067.076     1995881.538      322367.047
     1995877.196      322369.942     1995578.039      322729.066
#Sta/Elev= 30
       0 2932.32    40.1 2922.65   130.2 2895.28   160.2 2886.85   170.2 2883.17
   190.3 2871.95   210.3 2857.69   270.4 2810.75   340.5 2753.98   350.5 2748.27
   360.5 2745.92   380.6 2743.47   400.4  2742.1   415.4 2741.74   420.6 2741.69
   460.7 2743.31   500.7 2747.95   520.8 2749.44   555.9 2749.81   595.7 2755.46
   605.7 2758.65   744.9 2813.58   774.7 2826.51   794.6 2836.98   814.5 2848.42
     904 2904.32     914 2910.39   923.9 2915.43   933.8 2918.36  1013.4 2921.52
#Mann= 3 , 0 , 0
       0      .1       0   400.4    .045       0   415.4      .1       0
Bank Sta=400.4,415.4
XS Rating Curve= 0 ,0
Exp/Cntr=0.3,0.1

Type RM Length L Ch R = 1 ,54995.8 ,96.4,95.9,98.8
XS GIS Cut Line= 2
     1995941.643      321877.289     1995615.073      322584.297
#Sta/Elev= 30
       0  2883.2    49.9 2835.35    69.9 2817.94    79.9 2810.04    99.8 2796.43
   109.8  2790.7   129.8  2780.3   159.8 2766.63   179.7 2759.12   199.7 2753.12
   219.7 2748.51   239.6 2744.91   259.6 2742.17   299.5 2738.48   339.5 2735.64
   357.4 2735.75   372.4 2735.82   389.4 2734.95   399.4    2735   429.3 2740.18
   469.3 2742.18   489.2 2744.08   509.2  2747.7   529.2 2753.64   539.2 2758.29
   569.1 2775.76   589.1 2786.05     659 2816.02     669 2821.09   778.8 2897.15
#Mann= 3 , 0 , 0
       0      .1       0   357.4    .045       0   372.4      .1       0
Bank Sta=357.4,372.4
XS Rating Curve= 0 ,0
Exp/Cntr=0.3,0.1

Type RM Length L Ch R = 1 ,54899.9 ,328.8,329,328
XS GIS Cut Line= 3
     1995892.826      321867.189     1995630.223      322293.077
     1995512.388       322550.63
#Sta/Elev= 30
       0 2871.66      10 2863.15      50 2827.67      60 2819.74      80 2806.11
   100.1 2793.63   120.1 2782.42   140.1  2772.5   160.1 2763.68   180.1  2755.9
   200.1 2749.19   210.1 2746.27   240.2 2739.27   300.2 2727.35   330.2  2720.5
   330.6 2720.51   340.2 2720.64   345.6 2721.84   370.2 2728.73   440.3 2744.14
   519.9  2763.1   529.6 2765.94   539.4 2769.88   578.5 2790.44   617.5 2810.37
   637.1 2821.27   715.2 2871.11     764 2903.08   773.8 2908.92   783.6 2912.82
#Mann= 3 , 0 , 0
       0      .1       0   330.6    .045       0   345.6      .1       0
Bank Sta=330.6,345.6
XS Rating Curve= 0 ,0
Exp/Cntr=0.3,0.1

Type RM Length L Ch R = 1 ,54570.4 ,296.3,299.8,302.8
XS GIS Cut Line= 3
     1995600.425      321716.314     1995446.323      321976.038
     1995188.064      322463.829
#Sta/Elev= 30
       0 2791.45     9.7 2783.53    29.2 2770.37   126.6 2711.38   136.4  2705.2
   165.6 2683.95   175.4 2678.54   204.6  2667.4   214.3 2664.48   224.1 2663.05
   233.8 2662.76   294.5 2664.84   309.5 2665.33   341.4 2669.84   380.8 2672.89
   400.6  2675.5   420.3 2679.77     440 2685.91   459.7 2694.79   469.6 2700.72
   518.8 2737.13   538.6 2750.26   558.3 2760.68   617.4 2789.36   656.8 2806.94
   686.4 2816.01   706.1 2820.72     785 2834.83   814.5 2840.94   853.9 2852.77
#Mann= 3 , 0 , 0
       0      .1       0   294.5    .045       0   309.5      .1       0
Bank Sta=294.5,309.5
XS Rating Curve= 0 ,0
Exp/Cntr=0.3,0.1

Type RM Length L Ch R = 1 ,54270.4 ,361.3,376.3,393.9
XS GIS Cut Line= 3
     1995543.173      321414.186     1995181.986      321840.468
     1994865.327      322282.365
#Sta/Elev= 30
       0 2911.53      20 2900.98    49.9 2881.52    69.8  2866.7   139.7 2811.36
   229.5  2749.7   269.4 2724.45   289.3 2713.47   309.3 2703.88   359.2 2683.49
   389.1 2673.69   409.1 2668.67     439 2665.17   518.8 2661.91   551.2 2658.57
   558.7 2657.65   566.2 2657.82   578.5 2660.37   637.8 2684.12     707 2709.77
   736.6 2722.69   766.3 2739.35   776.2 2744.05   894.8 2789.65   954.1 2811.16
   973.9 2816.86   983.8  2818.3  1033.2 2822.38  1052.9  2825.3  1102.4 2839.01
#Mann= 3 , 0 , 0
       0      .1       0   551.2    .045       0   566.2      .1       0
Bank Sta=551.2,566.2
XS Rating Curve= 0 ,0
Exp/Cntr=0.3,0.1

Type RM Length L Ch R = 1 ,53894.1 ,234.7,223.7,212.6
XS GIS Cut Line= 4
     1995091.553       321514.52     1995017.455      321563.455
     1994956.439      321575.936     1994631.814      321632.087
#Sta/Elev= 30
       0 2706.82    29.6 2686.95    39.5 2681.45    49.3  2675.1    59.2 2667.12
    69.1  2658.1    78.9 2649.45    88.8 2642.23    97.7 2638.12   106.6 2635.97
   115.5 2634.68   124.4 2633.81   133.3 2633.33   142.2 2633.26     149 2633.43
     164 2634.11     181 2635.05     191 2635.43     201 2635.55     211 2635.41
     221  2635.9   240.9 2638.97   290.8 2644.31   300.8 2645.94   310.8 2648.37
   320.8 2651.25   360.7 2663.43   450.6 2691.31   460.6 2694.26   480.5 2699.63
#Mann= 3 , 0 , 0
       0      .1       0     149    .045       0     164      .1       0
Bank Sta=149,164
XS Rating Curve= 0 ,0
Exp/Cntr=0.3,0.1

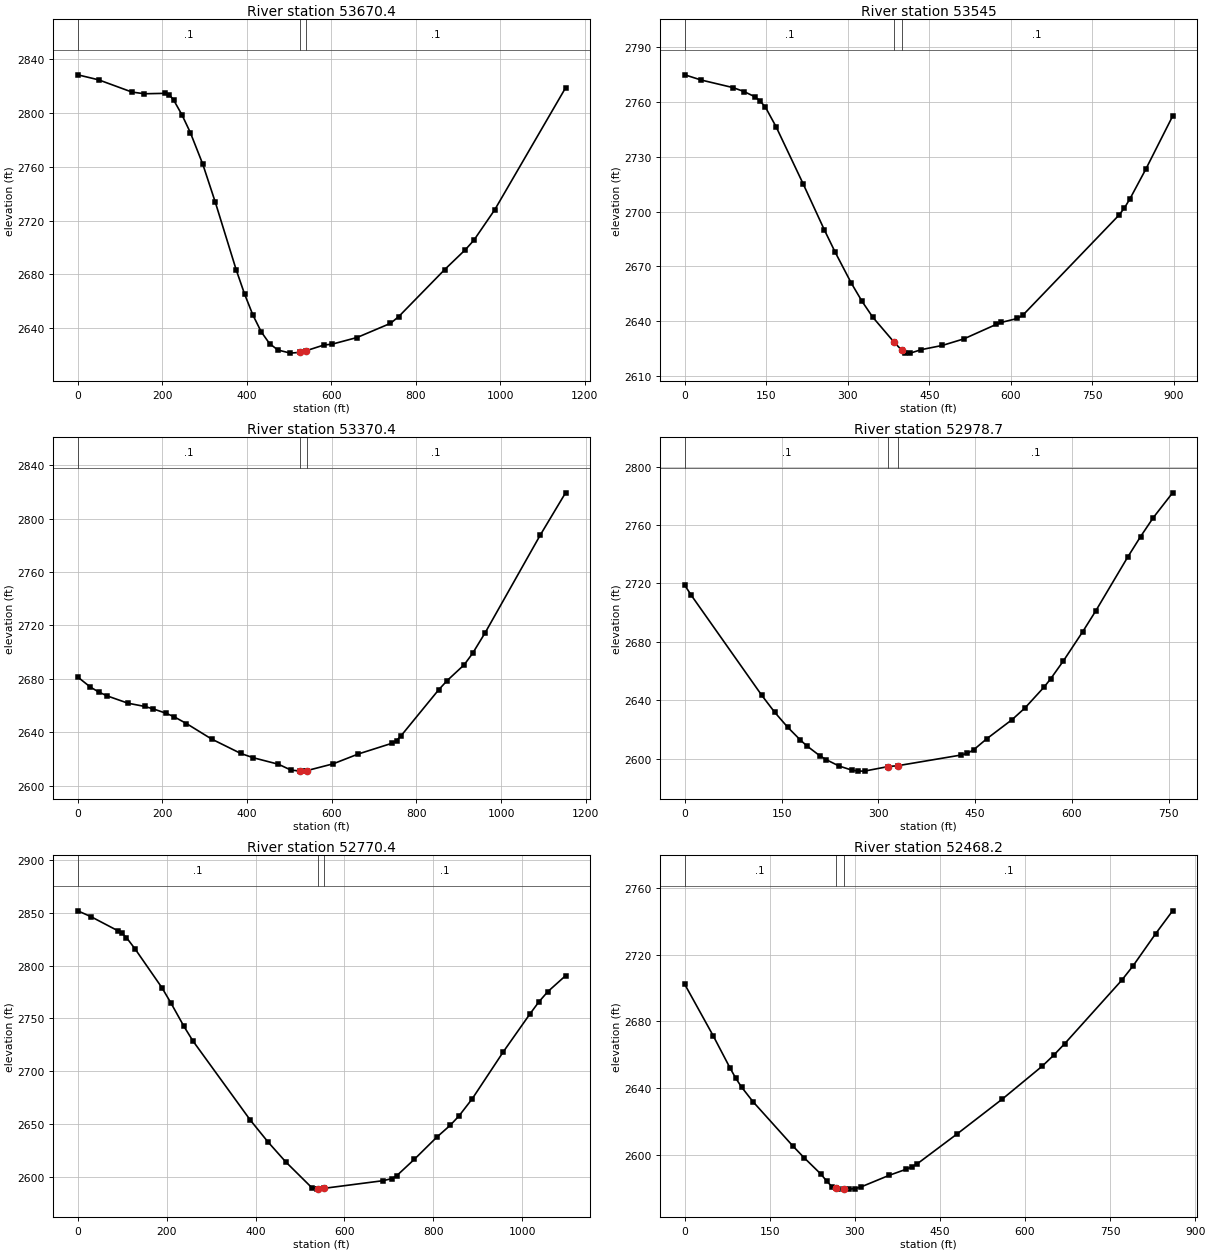
Type RM Length L Ch R = 1 ,53670.4 ,124.9,125.4,121.7
XS GIS Cut Line= 3
     1995306.636      321025.517      1994899.63      321369.122
     1994409.703      321751.738
#Sta/Elev= 30
       0 2828.29    49.3 2824.57   128.2 2815.47   157.8 2814.21   207.1 2814.54
     217 2813.31   226.9 2809.52   246.6 2798.48   266.3 2785.38   295.9 2761.75
   325.5  2733.5   374.8  2683.4   394.6 2665.39   414.3  2649.8     434  2637.3
   453.7 2628.53   473.5 2623.74   503.1 2621.42   525.2 2621.98   540.2 2623.18
     582 2627.42   601.7 2628.07   660.9 2633.03   739.9 2643.54   759.6 2648.62
   868.1 2683.49   917.5  2698.4   937.2 2705.28   986.5 2727.89  1154.3 2818.61
#Mann= 3 , 0 , 0
       0      .1       0   525.2    .045       0   540.2      .1       0
Bank Sta=525.2,540.2
XS Rating Curve= 0 ,0
Exp/Cntr=0.3,0.1

Type RM Length L Ch R = 1 ,53545   ,179.8,174.4,170.5
XS GIS Cut Line= 3
      1995131.95      321045.712      1994820.53      321272.965
     1994473.759      321650.036
#Sta/Elev= 30
       0 2774.98    29.7 2772.16      89 2767.95   108.7 2765.83   128.5 2763.02
   138.4 2760.67   148.3 2757.25     168 2746.47   217.5 2715.36     257 2689.81
   276.8 2677.66   306.4 2660.75   326.2 2650.74     346 2642.03   384.4 2628.62
   399.4 2623.91   405.2 2622.48   415.1 2622.36   434.8 2624.24   474.2  2626.6
   513.6 2630.17   572.7 2638.06   582.6 2639.21   612.1 2641.37     622 2643.12
   799.3  2698.1   809.1 2701.98     819 2706.82   848.6  2723.3   897.8  2752.3
#Mann= 3 , 0 , 0
       0      .1       0   384.4    .045       0   399.4      .1       0
Bank Sta=384.4,399.4
XS Rating Curve= 0 ,0
Exp/Cntr=0.3,0.1

Type RM Length L Ch R = 1 ,53370.4 ,405.1,391.6,379.8
XS GIS Cut Line= 3
     1995000.283      320747.767     1994677.618      321172.241
     1994346.741      321695.331
#Sta/Elev= 30
       0 2681.34    29.6 2673.84    49.4 2670.15    69.1 2667.26   118.5 2661.75
     158 2659.34   177.7 2657.53   207.4 2654.36   227.1 2651.66   256.7 2646.51
     316 2634.94   385.1 2624.12   414.7 2620.91     474 2616.05   503.6 2611.67
   525.7 2610.98   533.2 2610.91   540.7 2611.26   603.1 2616.37     663 2623.79
   742.8 2631.84   752.8 2633.79   762.8 2637.09   852.6 2671.88   872.6 2678.74
   912.6  2690.5   932.5 2699.05   962.5 2714.67  1092.2 2787.53  1152.1 2819.24
#Mann= 3 , 0 , 0
       0      .1       0   525.7    .045       0   540.7      .1       0
Bank Sta=525.7,540.7
XS Rating Curve= 0 ,0
Exp/Cntr=0.3,0.1

Type RM Length L Ch R = 1 ,52978.7 ,207.8,208.3,208.5
XS GIS Cut Line= 2
     1994328.245      320807.363     1994282.622      321561.898
#Sta/Elev= 30
       0 2718.69      10 2711.89   119.4 2643.31   139.2 2631.85   159.1 2621.72
     179 2612.84     189 2608.84   208.9 2602.15   218.8 2599.44   238.7 2595.08
   258.6 2592.24   268.6 2591.53   278.5 2591.56   315.3 2594.67   330.3 2595.26
   427.7 2602.52   437.6 2603.66   447.6 2606.12   467.5 2613.54   507.3 2626.84
   527.2 2634.81     557  2649.2   566.9 2654.71   586.8 2667.08   616.7 2687.04
   636.6 2701.06   686.3 2738.03   706.2 2752.04   726.1 2765.14   755.9 2782.04
#Mann= 3 , 0 , 0
       0      .1       0   315.3    .045       0   330.3      .1       0
Bank Sta=315.3,330.3
XS Rating Curve= 0 ,0
Exp/Cntr=0.3,0.1

Type RM Length L Ch R = 1 ,52770.4 ,299.6,302,301.5
XS GIS Cut Line= 3
     1994153.383      320547.253     1994107.635      321092.927
     1994066.973      321641.673
#Sta/Elev= 30
       0 2851.86    29.9 2846.28    89.6 2833.12    99.6 2830.48   109.5 2826.51
   129.4 2815.48   189.2 2779.17   209.1 2764.98     239 2742.37   258.9 2728.78
   388.3 2653.66   428.1 2632.99   467.9 2614.19   527.7 2589.28   537.6 2588.34
   540.1 2588.43   555.1 2589.14   687.6 2596.37   707.7 2598.39   717.7    2601
   757.7 2616.67   807.7 2637.42   837.7 2648.59   857.7 2657.51   887.7 2673.84
   957.8 2718.43  1017.8  2754.3  1037.8 2765.69  1057.8 2775.33  1097.8 2790.42
#Mann= 3 , 0 , 0
       0      .1       0   540.1    .045       0   555.1      .1       0
Bank Sta=540.1,555.1
XS Rating Curve= 0 ,0
Exp/Cntr=0.3,0.1

Type RM Length L Ch R = 1 ,52468.2 ,214.9,203.8,195.7
XS GIS Cut Line= 3
     1993928.352      320764.592     1993825.668      321003.628
     1993791.569      321602.688
#Sta/Elev= 30
       0  2702.1      50 2671.32      80 2651.78      90 2645.72   100.1 2640.47
   120.1 2631.78   190.1 2605.29   210.1 2598.19   240.2 2588.19   250.2 2584.04
   260.2 2580.42   265.9 2579.84   270.2  2579.4   280.9 2579.27   290.2 2579.25
   300.2 2579.57   310.2  2580.5   360.2 2587.52   390.2 2591.17   400.2  2592.6
   410.2 2594.54   480.2 2612.39   560.2  2633.4   630.2 2653.05   650.2 2659.52
   670.2 2666.67   770.2 2704.53   790.2 2713.15   830.2 2732.54   860.2 2746.32
#Mann= 3 , 0 , 0
       0      .1       0   265.9    .045       0   280.9      .1       0
Bank Sta=265.9,280.9
XS Rating Curve= 0 ,0
Exp/Cntr=0.3,0.1

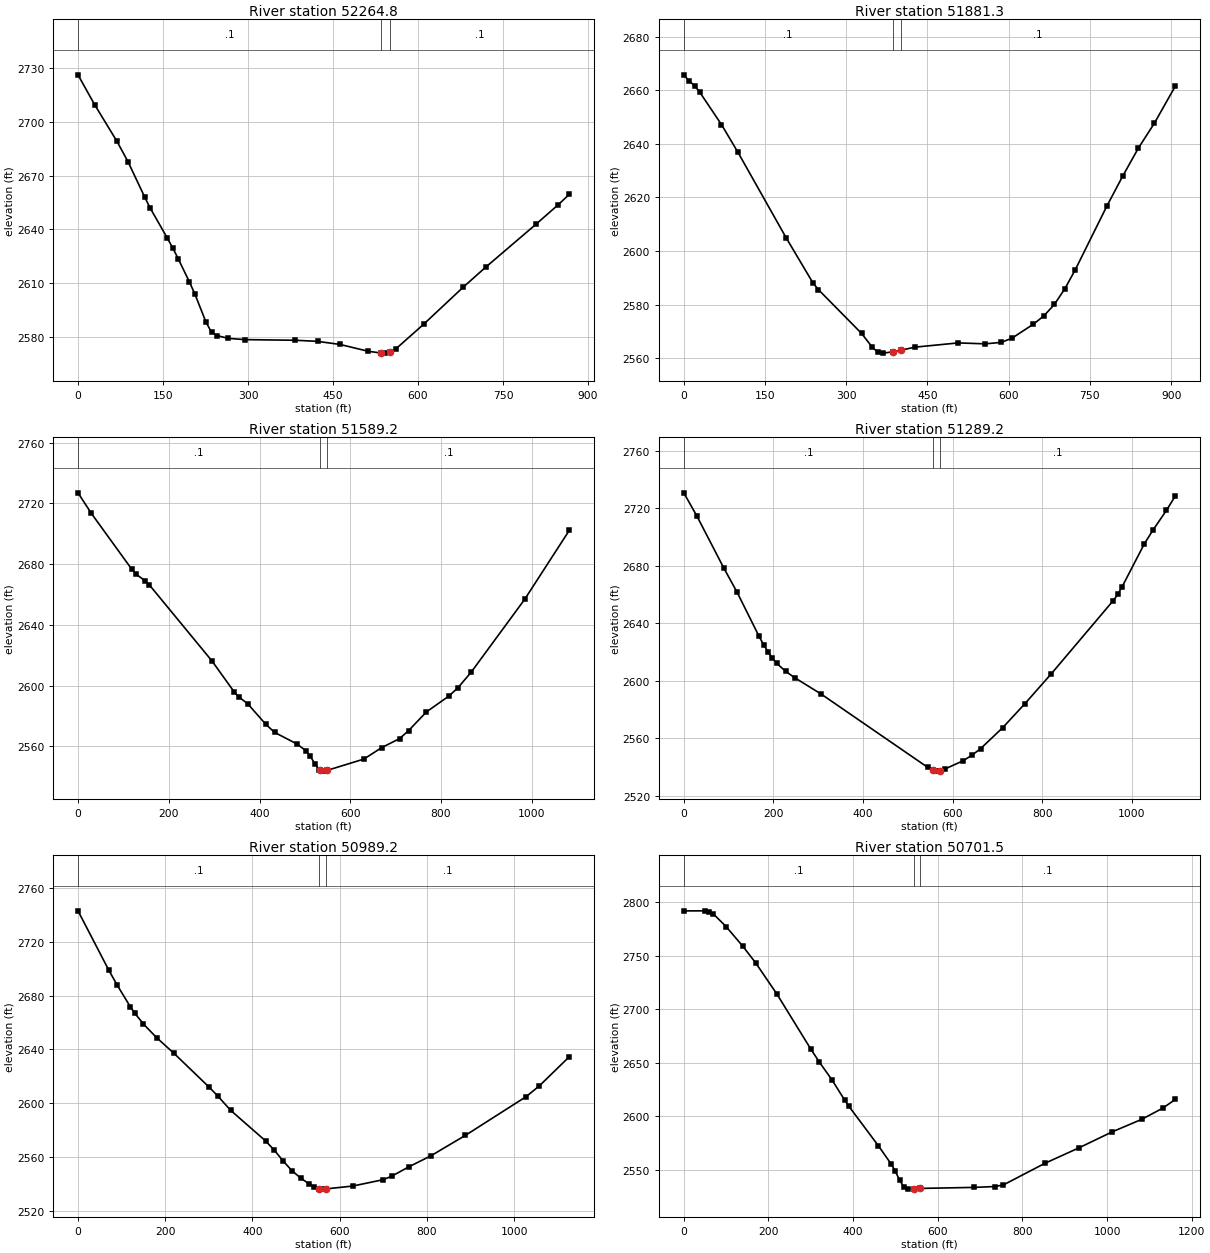
Type RM Length L Ch R = 1 ,52264.8 ,399.1,382.7,360.9
XS GIS Cut Line= 3
     1993747.055      320624.032      1993570.64      320808.528
      1993736.45      321397.533
#Sta/Elev= 30
       0 2726.24    29.4 2709.55    68.7 2689.13    88.4 2677.65   117.8 2657.89
   127.6  2651.7   157.1 2635.37   166.9 2629.73   176.7 2623.64   196.4 2610.71
   206.2 2603.88   225.8 2588.18   235.6 2582.44   245.4 2580.61   265.1 2579.06
   294.7 2578.36   383.6 2578.01     423 2577.38   462.5 2575.66   511.9 2571.87
   534.8 2570.87   541.5 2570.82   549.8 2571.29   561.2 2573.27   610.6 2587.14
   679.6 2607.61   719.1 2618.72     808 2642.75   847.4 2653.69   867.2 2659.57
#Mann= 3 , 0 , 0
       0      .1       0   534.8    .045       0   549.8      .1       0
Bank Sta=534.8,549.8
XS Rating Curve= 0 ,0
Exp/Cntr=0.3,0.1

Type RM Length L Ch R = 1 ,51881.3 ,297.1,292.1,294.7
XS GIS Cut Line= 4
     1992956.422      320879.215     1993241.373      321061.282
     1993478.663      321241.074     1993662.382        321441.3
#Sta/Elev= 30
       0 2665.73      10 2663.39    19.9  2661.7    29.8 2659.16    69.6 2647.18
    99.5 2637.02     189 2604.99   238.7  2588.1   248.6 2585.65   328.2 2569.35
   348.1 2564.19     358 2562.38   367.9 2561.98   385.8 2562.45   400.8 2563.08
   427.5 2564.22   506.8 2565.79   556.5 2565.44   586.2 2565.98   606.1 2567.55
   645.6 2572.77     665 2575.86   684.4 2580.14   703.8    2586   723.2 2593.15
   781.4 2616.84   810.6 2627.98   839.7 2638.47   868.8  2647.6   907.6 2661.46
#Mann= 3 , 0 , 0
       0      .1       0   385.8    .045       0   400.8      .1       0
Bank Sta=385.8,400.8
XS Rating Curve= 0 ,0
Exp/Cntr=0.3,0.1

Type RM Length L Ch R = 1 ,51589.2 ,293.2,300,303.1
XS GIS Cut Line= 3
     1992657.449      321107.715     1993147.866      321337.143
     1993609.683      321620.096
#Sta/Elev= 30
       0 2726.96    29.5  2713.4   118.1 2676.79     128 2673.34   147.7 2669.11
   157.5 2666.22   295.3 2616.21   344.6 2595.68   354.4 2592.53   374.1    2588
   413.5 2574.62   433.1  2569.2   482.4 2561.56     502 2557.15   511.9  2553.5
   521.7 2548.54   531.6 2544.71   533.9 2544.46   541.4 2543.66   548.9 2544.15
   630.1 2551.61   669.4 2559.18   708.8 2565.09   728.5 2570.32   767.9 2582.67
   817.2 2593.08   836.8  2598.4   866.4  2608.8   984.6 2656.91    1083 2702.38
#Mann= 3 , 0 , 0
       0      .1       0   533.9    .045       0   548.9      .1       0
Bank Sta=533.9,548.9
XS Rating Curve= 0 ,0
Exp/Cntr=0.3,0.1

Type RM Length L Ch R = 1 ,51289.2 ,292.8,300,306.1
XS GIS Cut Line= 3
     1992592.889      321223.487     1993010.999      321601.671
     1993422.512      321940.627
#Sta/Elev= 30
       0 2730.73    29.7 2714.29      89 2678.57   118.7 2661.71   168.1 2630.78
     178 2625.12   187.9 2620.12   197.8 2615.68   207.7 2611.98   227.5 2606.48
   247.3 2602.12   306.6 2590.69     544 2539.77   556.3 2537.56   563.8 2537.06
   571.3 2537.35   583.5 2538.64     623  2544.2   642.8 2548.04   662.5 2552.72
   711.9 2567.34   761.2 2583.92   820.5 2604.89   958.7  2655.8   968.6 2660.09
   978.4  2665.4  1027.8 2695.16  1047.5 2704.96  1077.2 2718.49  1096.9 2728.46
#Mann= 3 , 0 , 0
       0      .1       0   556.3    .045       0   571.3      .1       0
Bank Sta=556.3,571.3
XS Rating Curve= 0 ,0
Exp/Cntr=0.3,0.1

Type RM Length L Ch R = 1 ,50989.2 ,303.9,287.7,274.2
XS GIS Cut Line= 3
     1992528.635      321278.479     1992787.572      321775.101
     1993097.307      322249.472
#Sta/Elev= 30
       0 2742.98      70 2699.21      90 2687.63     120 2671.64     130 2666.88
     150 2658.83     180 2648.71     220    2637     300 2612.03     320  2605.4
     350 2594.58   430.1 2571.82   450.1 2564.92   470.1 2556.99   490.1 2549.82
   510.1  2544.3   530.1 2539.81   540.1 2537.64   552.6 2536.21   560.1 2535.98
   567.6 2536.12   629.6 2538.26   699.2 2542.97   719.1 2545.58   758.9 2552.65
   808.6 2560.69   888.1 2575.96  1027.2 2604.74    1057 2612.59  1126.6 2634.54
#Mann= 3 , 0 , 0
       0      .1       0   552.6    .045       0   567.6      .1       0
Bank Sta=552.6,567.6
XS Rating Curve= 0 ,0
Exp/Cntr=0.3,0.1

Type RM Length L Ch R = 1 ,50701.5 ,291.4,299.3,308.1
XS GIS Cut Line= 4
     1992056.741      321771.358     1992570.742      321935.849
     1992863.338      322048.251     1993038.099      322301.874
#Sta/Elev= 30
       0 2791.91      50 2791.99      60 2791.32      70 2789.03    99.9 2777.28
   139.9 2758.68   169.9 2743.29   219.9 2714.27   299.8 2662.95   319.8  2650.9
   349.8 2634.22   379.8 2615.28   389.8 2609.48   459.7 2572.45   489.7  2555.5
   499.7  2548.7   509.7 2540.51   519.7 2533.89   529.7 2531.92   544.1 2532.33
   559.1  2532.6   686.6 2533.54   735.6 2534.36   755.2 2535.88   853.1 2556.04
   932.6 2570.31  1012.1 2585.43  1081.6 2597.09  1131.3 2607.53  1161.1  2615.7
#Mann= 3 , 0 , 0
       0      .1       0   544.1    .045       0   559.1      .1       0
Bank Sta=544.1,559.1
XS Rating Curve= 0 ,0
Exp/Cntr=0.3,0.1

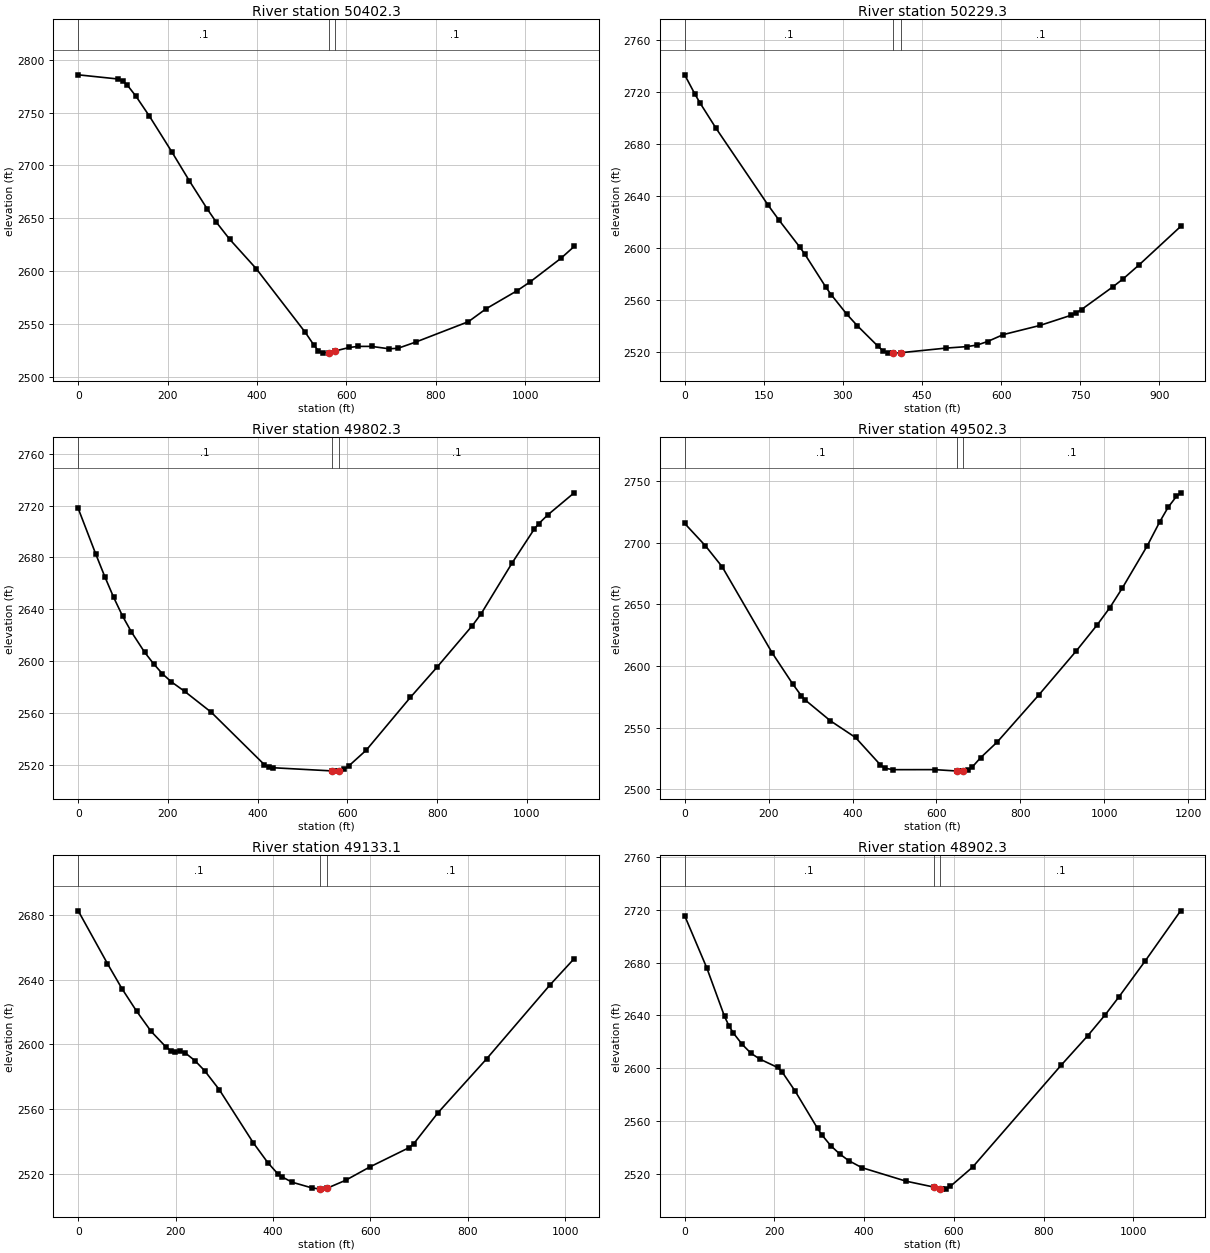
Type RM Length L Ch R = 1 ,50402.3 ,172.1,172.8,171.7
XS GIS Cut Line= 3
     1992010.636      321846.481     1992452.614      322202.427
     1992845.919      322575.577
#Sta/Elev= 30
       0 2785.72    89.6 2781.75    99.6 2779.76   109.5 2776.19   129.4 2765.34
   159.3 2746.62   209.1 2713.04   248.9 2685.25   288.7 2658.76   308.6 2646.45
   338.5 2630.28   398.2 2602.29   507.8 2542.12   527.7  2529.7   537.6 2524.43
   547.6 2522.33     560 2522.72     575 2524.38   606.9 2527.73   626.6 2528.69
   656.2 2528.71   695.6 2526.42   715.4 2526.91   754.8 2532.74   873.1 2552.12
   912.5 2564.28   981.5 2581.29  1011.1 2589.74  1080.1 2612.09  1109.6 2623.28
#Mann= 3 , 0 , 0
       0      .1       0     560    .045       0     575      .1       0
Bank Sta=560,575
XS Rating Curve= 0 ,0
Exp/Cntr=0.3,0.1

Type RM Length L Ch R = 1 ,50229.3 ,408.7,426.9,443.5
XS GIS Cut Line= 3
      1992102.19       322003.97     1992254.474      322259.408
     1992742.724      322677.635
#Sta/Elev= 30
       0 2733.07    19.8 2717.95    29.7 2711.05    59.5 2691.94   158.6 2632.65
   178.4 2621.63   218.1  2600.7     228 2595.08   267.6 2569.88   277.6 2564.16
   307.3 2549.09   327.1 2540.29   366.6 2524.37   376.5 2520.77   386.4 2519.13
   394.3 2519.14   409.3 2519.44   495.2 2522.99   534.8 2524.13   554.5 2525.34
   574.3 2528.06     604 2533.37   673.2 2540.37   732.6 2548.23   742.5  2550.1
   752.4 2552.65   811.7 2570.05   831.5 2576.28   861.2 2586.84   940.3 2616.49
#Mann= 3 , 0 , 0
       0      .1       0   394.3    .045       0   409.3      .1       0
Bank Sta=394.3,409.3
XS Rating Curve= 0 ,0
Exp/Cntr=0.3,0.1

Type RM Length L Ch R = 1 ,49802.3 ,298.2,299.8,301.3
XS GIS Cut Line= 3
     1991976.614      322031.873     1992014.174      322603.603
     1992084.237      323131.504
#Sta/Elev= 30
       0 2717.85    39.5 2682.29    59.3 2665.15      79 2649.19    98.8 2634.77
   118.5 2622.51   148.2 2606.71   167.9 2597.95   187.7 2590.15   207.4    2584
   237.1 2576.62   296.4  2560.5   414.9 2519.98   424.8 2518.06   434.7 2517.58
   565.5 2515.14     573 2514.97   580.5 2515.08   592.7 2516.28   602.6 2518.81
     642 2531.14   740.6    2572   799.8 2595.25   878.7 2627.42   898.4 2636.65
   967.4 2675.86  1016.7 2701.98  1026.6 2706.11  1046.3 2712.75  1105.5 2729.92
#Mann= 3 , 0 , 0
       0      .1       0   565.5    .045       0   580.5      .1       0
Bank Sta=565.5,580.5
XS Rating Curve= 0 ,0
Exp/Cntr=0.3,0.1

Type RM Length L Ch R = 1 ,49502.3 ,369.3,368.9,369.7
XS GIS Cut Line= 3
     1991817.701      321950.484     1991797.666      322605.454
     1991811.508      323131.895
#Sta/Elev= 30
       0 2715.74    49.6 2697.52    89.4 2680.52   208.5 2610.66   258.1 2585.12
     278 2575.87   287.9 2572.22   347.5 2555.47   407.1 2541.98   466.6 2519.69
   476.6  2517.1   496.4 2515.86   595.7  2515.9   647.8 2514.79   655.3 2514.68
   662.8 2514.68   675.2 2515.47   685.1 2517.92     705 2525.49   744.7 2538.26
   844.1 2576.57   933.5 2612.36   983.2 2633.46    1013 2647.26  1042.8 2663.19
  1102.4 2697.59  1132.2 2717.09  1152.1 2728.85    1172 2737.73  1181.9 2740.59
#Mann= 3 , 0 , 0
       0      .1       0   647.8    .045       0   662.8      .1       0
Bank Sta=647.8,662.8
XS Rating Curve= 0 ,0
Exp/Cntr=0.3,0.1

Type RM Length L Ch R = 1 ,49133.1 ,226.1,230.6,240.2
XS GIS Cut Line= 2
     1991513.365      321982.741      1991541.44      323000.485
#Sta/Elev= 30
       0  2682.5    59.9 2649.95    89.8  2634.4   119.8 2620.53   149.7    2608
   179.7 2598.52   189.6 2596.15   199.6  2595.5   209.6 2595.73   219.6 2594.72
   239.6 2589.94   259.5 2583.72   289.5 2572.05   359.3 2539.22   389.3 2526.87
   409.2 2520.19   419.2 2517.98   439.2 2514.82   479.1 2511.36     496 2510.61
   499.1 2510.55     511 2511.12     549 2516.02   598.9 2524.29   678.8 2536.11
   688.7 2538.56   738.6 2557.76   838.5 2591.08   968.2 2636.62  1018.1 2652.94
#Mann= 3 , 0 , 0
       0      .1       0     496    .045       0     511      .1       0
Bank Sta=496,511
XS Rating Curve= 0 ,0
Exp/Cntr=0.3,0.1

Type RM Length L Ch R = 1 ,48902.3 ,295.2,299.8,296.1
XS GIS Cut Line= 3
     1991410.919      321923.913     1991302.485      322476.098
     1991083.307      322972.869
#Sta/Elev= 30
       0 2715.72    49.4 2676.02    88.8 2639.33    98.7 2632.11   108.6 2626.64
   128.3 2618.02   148.1 2611.21   167.8 2606.84   207.3  2600.5   217.2 2597.17
   246.8 2582.29   296.2 2554.26     306 2549.27   325.8 2541.07   345.5 2534.89
   365.3 2529.86   394.9 2524.46   493.6 2514.17   555.2 2509.73   570.2 2508.34
   572.6 2508.14   582.5 2508.33   592.4 2510.29   641.7 2524.76   839.2 2602.18
   898.4 2624.52   937.9 2640.65   967.5  2653.8  1026.7 2681.38  1105.7 2719.45
#Mann= 3 , 0 , 0
       0      .1       0   555.2    .045       0   570.2      .1       0
Bank Sta=555.2,570.2
XS Rating Curve= 0 ,0
Exp/Cntr=0.3,0.1