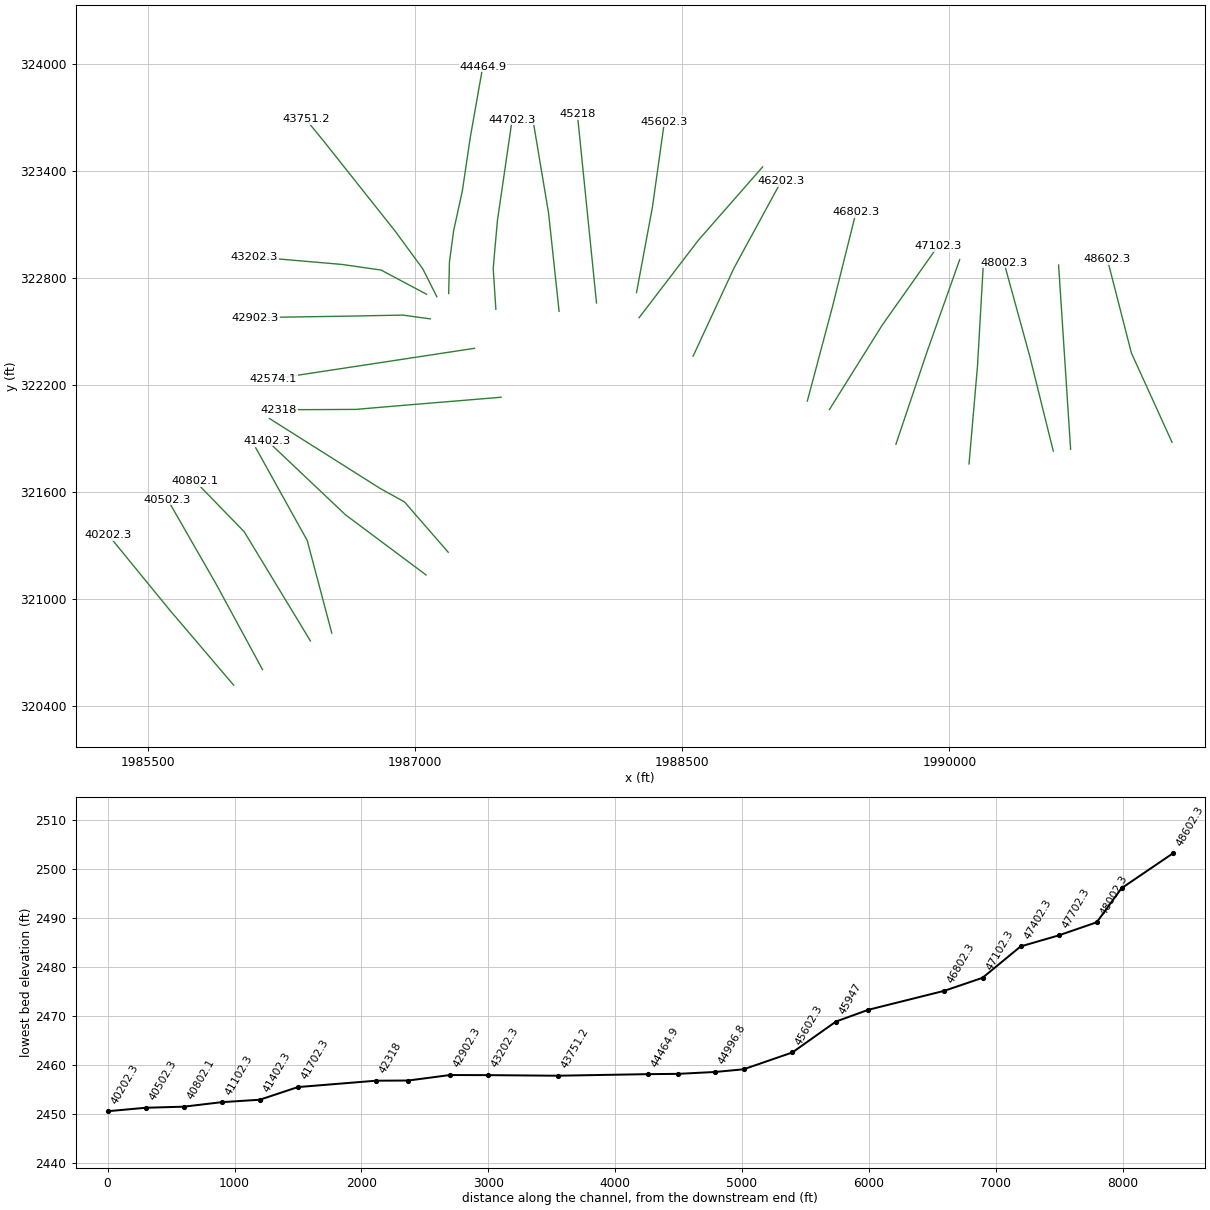
HEC-RAS study LaurelCrk.prj: LaurelCrk

--- LaurelCrk.g01 (geometry) --- (continued)

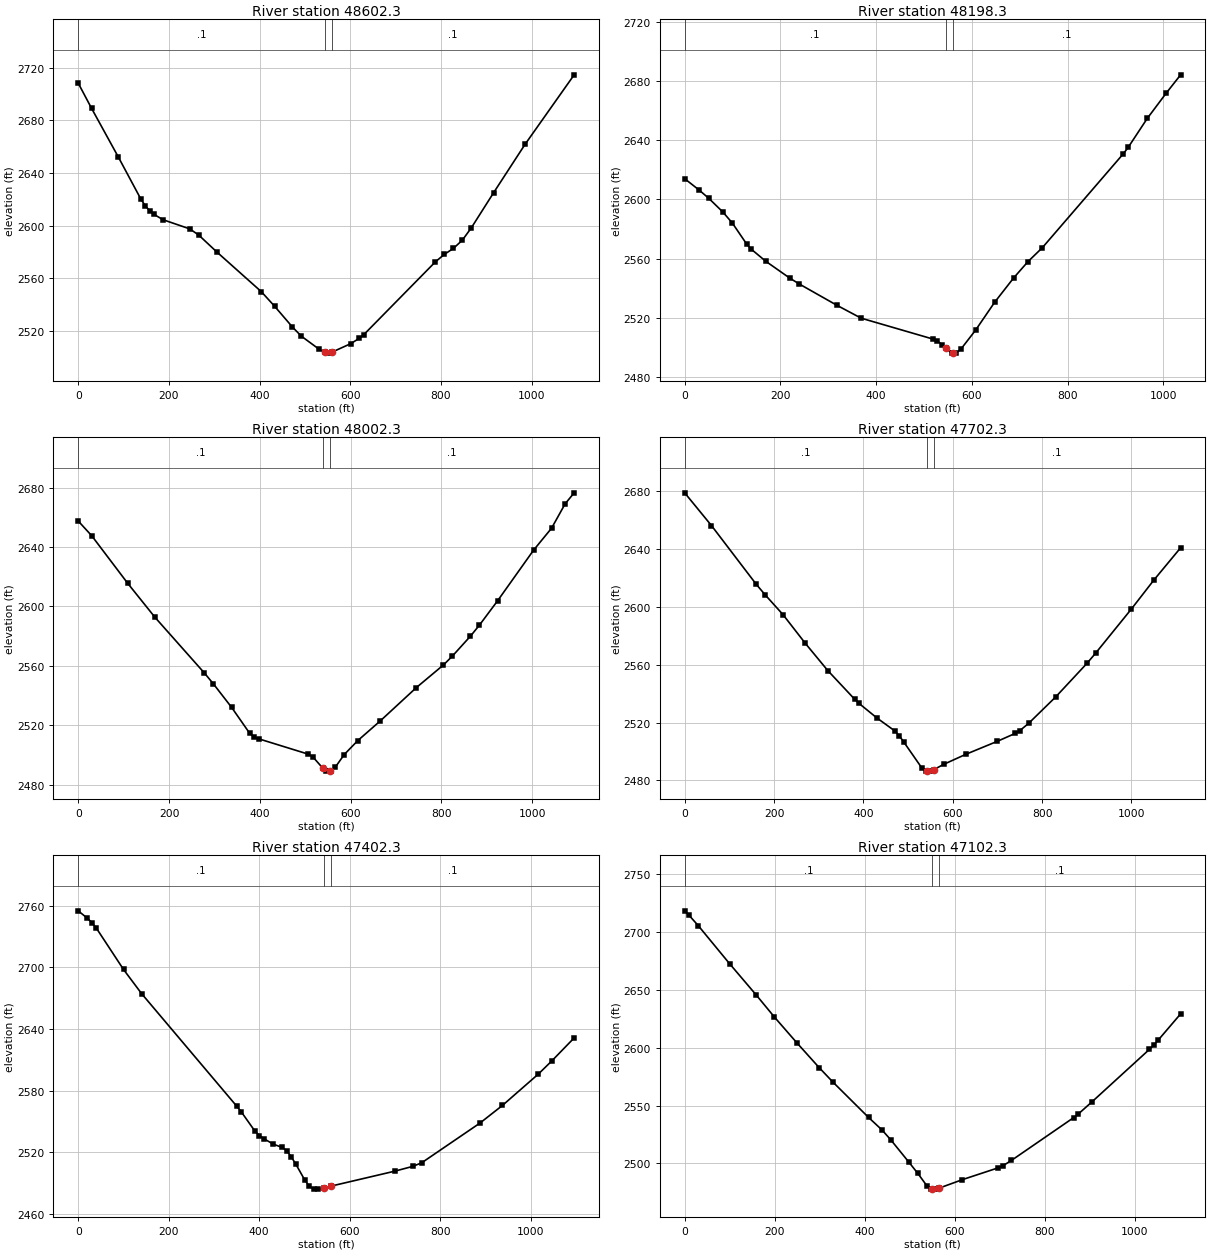
Type RM Length L Ch R = 1 ,48602.3 ,411.4,403.8,399.6
XS GIS Cut Line= 3
     1991249.662      321879.595     1991021.194       322381.23
     1990886.341      322906.899
#Sta/Elev= 30
       0 2708.34    29.5 2689.15    88.6 2652.12   137.8 2620.46   147.6 2615.25
   157.5 2611.42   167.3  2608.6     187 2604.56   246.1 2597.59   265.8  2592.9
   305.1 2580.25   403.6 2549.98   433.1 2538.85   472.5 2523.03   492.2 2516.07
   531.5 2506.12   543.7  2503.8   551.2  2503.2   558.7 2503.78   600.6 2510.31
   620.3 2514.49   630.2 2517.33     788 2572.62   807.8 2578.29   827.5 2582.74
   847.2    2589     867 2598.34   916.3 2625.11   985.4 2661.73  1093.9 2714.64
#Mann= 3 , 0 , 0
       0      .1       0   543.7    .045       0   558.7      .1       0
Bank Sta=543.7,558.7
XS Rating Curve= 0 ,0
Exp/Cntr=0.3,0.1

Type RM Length L Ch R = 1 ,48198.3 ,192,196.1,200.7
XS GIS Cut Line= 2
     1990680.109      321840.549     1990612.603      322874.144
#Sta/Elev= 30
       0 2613.89    29.9  2606.3    49.8 2600.81    79.7 2591.41    99.6 2583.93
   129.5 2569.73   139.4 2566.19   169.3 2558.15   219.1 2546.84     239 2542.85
   318.7 2528.27   368.5 2519.71   517.9 2505.66   527.9 2504.21   537.8 2501.83
   545.1 2499.48   557.7  2496.1   560.1 2496.13   567.7 2496.22   577.7 2499.13
   607.5 2511.58   647.4 2530.46   687.2 2546.93   717.1 2557.94     747  2567.3
   916.3  2630.8   926.2    2635   966.1 2654.59  1005.9 2671.76  1035.8 2684.04
#Mann= 3 , 0 , 0
       0      .1       0   545.1    .045       0   560.1      .1       0
Bank Sta=545.1,560.1
XS Rating Curve= 0 ,0
Exp/Cntr=0.3,0.1

Type RM Length L Ch R = 1 ,48002.3 ,307.3,299.9,292.6
XS GIS Cut Line= 3
     1990582.809      321830.164     1990451.157      322360.266
     1990306.392      322886.688
#Sta/Elev= 30
       0 2657.51    29.8 2647.56   109.2 2615.49   168.8 2592.76   278.1 2555.11
   297.9  2547.8   337.6 2532.15   377.4  2514.7   387.3    2512   397.2 2510.91
   506.5 2500.58   516.4 2498.85   538.7 2491.11   546.2 2489.17   553.7 2489.15
   556.1 2489.14   566.1 2491.75   585.9 2500.31   615.7 2509.69   665.3 2522.96
   744.7 2545.37   804.3 2560.59   824.2 2566.63   863.9 2580.02   883.7 2587.46
   923.4 2603.72  1002.8 2637.86  1042.5 2652.68  1072.3 2669.06  1092.2 2676.47
#Mann= 3 , 0 , 0
       0      .1       0   538.7    .045       0   553.7      .1       0
Bank Sta=538.7,553.7
XS Rating Curve= 0 ,0
Exp/Cntr=0.3,0.1

Type RM Length L Ch R = 1 ,47702.3 ,305.4,300,293.5
XS GIS Cut Line= 3
      1990109.58      321758.135     1990157.124      322306.351
     1990189.198      322865.267
#Sta/Elev= 30
       0  2678.7      60 2656.07   160.1 2615.55   180.1 2608.25   220.1 2594.56
   270.1 2574.71   320.2 2555.97   380.2 2536.21   390.2 2533.25   430.2  2523.2
   470.2 2514.27   480.2 2510.89   490.2 2506.68   530.3 2488.88   540.3 2486.49
   542.8 2486.48   550.3 2486.46   557.8 2487.52   580.3 2491.22   630.2  2498.2
   700.2  2507.1   740.2 2512.56   750.2 2514.42   770.2 2519.55   830.2 2537.63
   900.2 2560.82   920.2 2568.08  1000.1 2598.52  1050.1  2618.4  1110.1 2640.74
#Mann= 3 , 0 , 0
       0      .1       0   542.8    .045       0   557.8      .1       0
Bank Sta=542.8,557.8
XS Rating Curve= 0 ,0
Exp/Cntr=0.3,0.1

Type RM Length L Ch R = 1 ,47402.3 ,305.3,300,293.8
XS GIS Cut Line= 3
     1989699.212      321868.889     1989874.981      322390.884
     1990057.285      322904.653
#Sta/Elev= 30
       0 2755.07      20 2747.93      30 2743.64    40.1 2738.22   100.1 2698.01
   140.2 2674.42   350.5 2564.82   360.5 2559.35   390.6 2540.61   400.6 2536.33
   410.6  2533.2   430.6 2528.11   450.6 2524.76   460.7 2521.67   470.7 2515.66
   480.7 2508.68   500.7 2493.04   510.7 2486.97   520.8 2484.32   530.8 2484.21
   543.3 2485.44   558.3  2487.1   699.5 2501.68   739.1 2506.32   758.9  2509.8
   887.8 2548.48   937.4 2565.62  1016.6 2596.09  1046.4 2608.88    1096 2631.39
#Mann= 3 , 0 , 0
       0      .1       0   543.3    .045       0   558.3      .1       0
Bank Sta=543.3,558.3
XS Rating Curve= 0 ,0
Exp/Cntr=0.3,0.1

Type RM Length L Ch R = 1 ,47102.3 ,293.2,300,308.4
XS GIS Cut Line= 3
     1989325.858      322063.677     1989621.851       322536.53
     1989935.512      322980.887
#Sta/Elev= 30
       0 2718.07      10 2714.08    29.9 2705.39    99.6  2672.5   159.4  2645.2
   199.2 2626.44     249 2604.21   298.8 2582.69   328.7 2570.48   408.4 2539.73
   438.3 2528.94   458.2 2520.23   498.1  2501.1     518 2491.37   537.9 2480.78
   547.9 2478.02   550.4 2477.97   557.8 2477.81   565.4 2478.68   617.2 2486.03
   696.3 2496.17   706.2 2497.78     726 2502.61   864.4  2539.6   874.3 2542.61
     904 2552.85  1032.5 2598.47  1042.4 2602.31  1052.3  2606.6  1101.8 2629.11
#Mann= 3 , 0 , 0
       0      .1       0   550.4    .045       0   565.4      .1       0
Bank Sta=550.4,565.4
XS Rating Curve= 0 ,0
Exp/Cntr=0.3,0.1

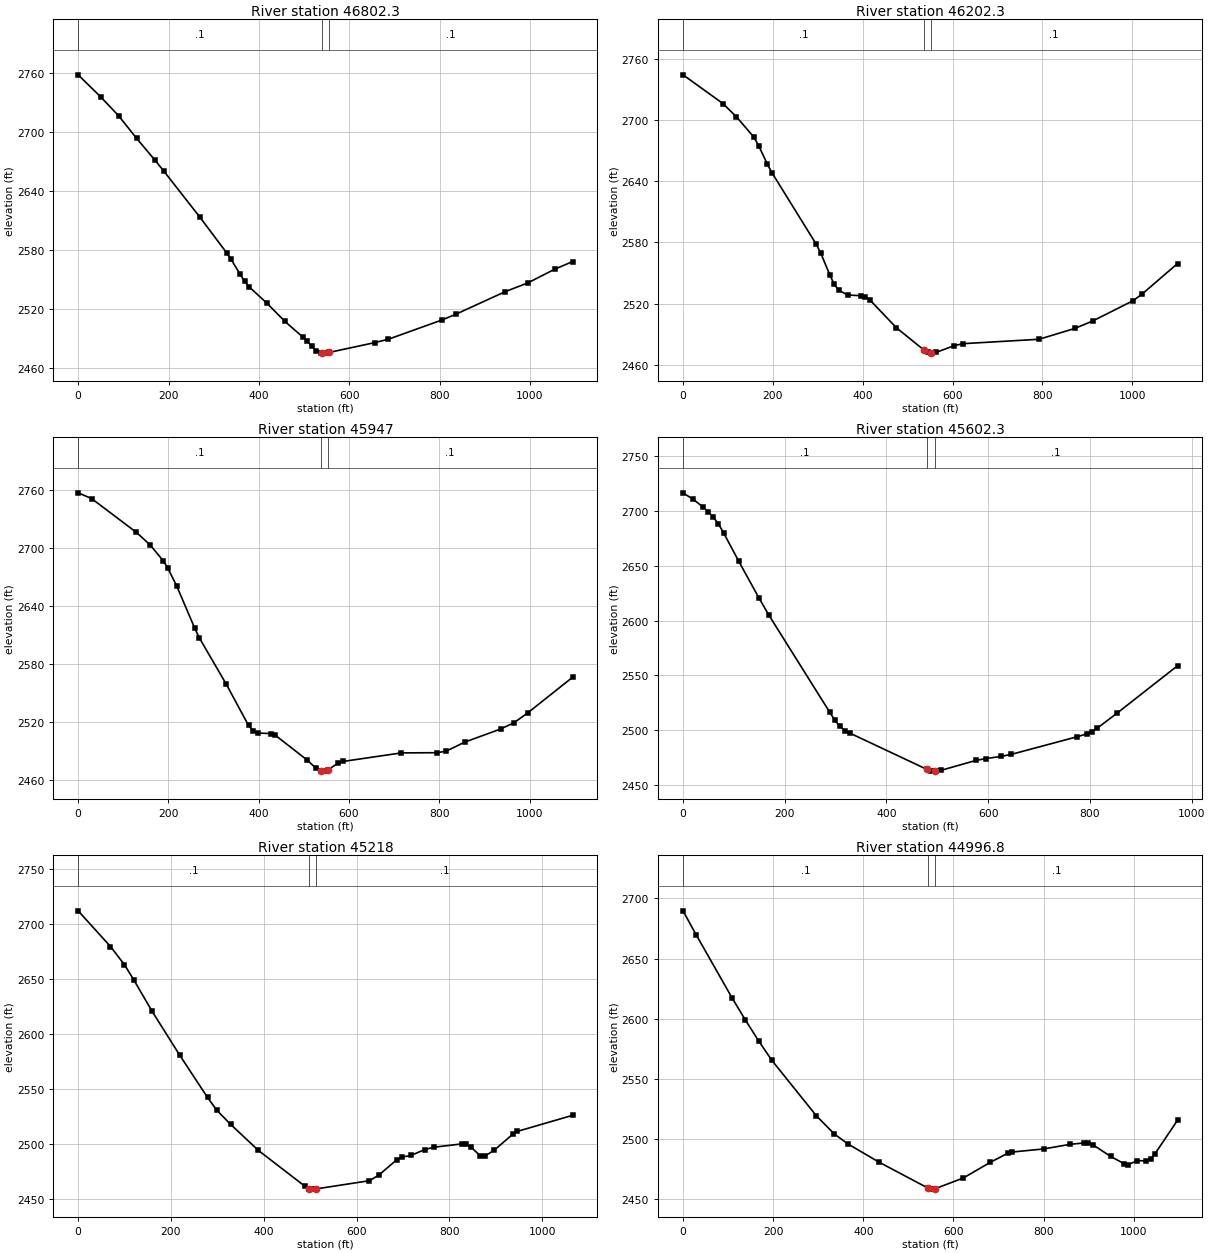
Type RM Length L Ch R = 1 ,46802.3 ,603.6,599.7,594
XS GIS Cut Line= 3
     1989201.719      322111.244     1989342.732      322640.041
     1989475.186      323170.919
#Sta/Elev= 30
       0  2758.5    49.8 2736.11    89.6 2716.79   129.4 2693.85   169.2 2672.06
   189.1 2660.79   268.7 2614.02   328.4 2577.45   338.3 2570.76   358.2 2555.62
   368.2  2548.4   378.1 2542.77   417.9 2525.96   457.7  2507.4   497.5 2491.45
   507.5 2487.12   517.4 2481.99   527.4 2477.43   537.3 2475.24   539.8 2475.22
   547.3 2475.16   554.8  2475.8   656.7 2485.88   686.6 2489.31   805.9 2509.03
   835.8 2514.74   945.2 2537.74     995 2546.61  1054.6 2560.57  1094.4 2568.37
#Mann= 3 , 0 , 0
       0      .1       0   539.8    .045       0   554.8      .1       0
Bank Sta=539.8,554.8
XS Rating Curve= 0 ,0
Exp/Cntr=0.3,0.1

Type RM Length L Ch R = 1 ,46202.3 ,260.2,255.3,250.4
XS GIS Cut Line= 3
     1988560.094      322362.488     1988789.212      322856.055
      1989055.34      323344.577
#Sta/Elev= 30
       0 2744.74      89 2716.47   118.7 2703.56   158.3  2683.2   168.2 2675.25
     188 2656.71   197.9 2648.58   296.8 2578.07   306.7 2569.42   326.5 2548.35
   336.4 2538.94   346.3  2533.3   366.1 2528.35   395.8 2527.75   405.6 2526.59
   415.5 2523.71   474.9 2496.21   536.7 2474.16   544.2    2472   551.7 2471.45
   554.1 2471.28     564 2472.09   603.8 2478.69   623.6 2480.58   792.5  2484.9
     872 2495.57   911.7 2502.84  1001.1 2522.69    1021 2529.04  1100.5 2559.27
#Mann= 3 , 0 , 0
       0      .1       0   536.7    .045       0   551.7      .1       0
Bank Sta=536.7,551.7
XS Rating Curve= 0 ,0
Exp/Cntr=0.3,0.1

Type RM Length L Ch R = 1 ,45947   ,333.9,344.6,357.6
XS GIS Cut Line= 3
     1988256.639      322578.314     1988588.813      323012.183
     1988950.639      323424.893
#Sta/Elev= 30
       0 2756.89    29.8 2750.95   129.2 2715.89     159 2703.22   188.8 2686.41
   198.7 2678.92   218.6 2660.17   258.3 2616.72   268.2 2606.96   327.9 2559.04
   377.5  2516.1   387.5 2510.68   397.4 2508.32   427.2 2507.72   437.1 2505.89
   506.7 2480.53   526.6 2472.06   537.8 2469.22   546.4 2468.88   552.8 2470.12
   576.4 2477.22   586.3 2478.87   716.1 2487.75   795.9 2487.95   815.9 2489.68
   855.8 2498.81   935.6 2512.44   965.6 2519.02   995.5 2529.03  1095.3 2566.05
#Mann= 3 , 0 , 0
       0      .1       0   537.8    .045       0   552.8      .1       0
Bank Sta=537.8,552.8
XS Rating Curve= 0 ,0
Exp/Cntr=0.3,0.1

Type RM Length L Ch R = 1 ,45602.3 ,377.9,384.3,389.8
XS GIS Cut Line= 3
     1988242.546      322719.728     1988331.793      323198.926
     1988399.302       323678.98
#Sta/Elev= 30
       0 2716.71    19.9 2710.78    39.8 2703.66    49.7 2699.43    59.7 2694.52
    69.6 2688.28    79.6 2680.38   109.4 2654.34   149.2 2620.79   169.1 2604.77
   288.5 2516.32   298.4 2509.18   308.4 2503.38   318.3 2499.63   328.3 2497.21
   479.9 2464.08   487.4 2462.88   494.9 2462.64   497.3 2462.56   507.2 2463.27
   576.5 2472.42   596.3 2474.09     626 2476.03   645.7 2477.91   774.4 2493.89
   794.1 2496.59     804 2498.62   813.9  2501.6   853.5 2515.54   972.2 2558.78
#Mann= 3 , 0 , 0
       0      .1       0   479.9    .045       0   494.9      .1       0
Bank Sta=479.9,494.9
XS Rating Curve= 0 ,0
Exp/Cntr=0.3,0.1

Type RM Length L Ch R = 1 ,45218   ,221,221.1,222.5
XS GIS Cut Line= 2
     1988017.941      322661.237     1987910.317      323721.094
#Sta/Elev= 30
       0 2712.01    69.7 2679.59    99.6 2663.13   119.5 2649.55   159.3 2620.72
     219 2580.72   278.8  2542.4   298.7 2530.81   328.6 2517.94   388.3  2494.3
   487.8 2461.99   497.8 2459.59   507.8 2459.13   512.8 2459.34   627.2 2466.76
   647.2  2471.7     687 2486.02   696.9 2488.15   716.8 2489.71   746.7 2495.09
   766.6  2497.2   826.4 2500.22   836.3 2499.79   846.3 2497.33   866.2 2489.49
   876.1 2489.15     896 2494.35   935.9 2508.85   945.8 2511.56  1065.3  2526.2
#Mann= 3 , 0 , 0
       0      .1       0   497.8    .045       0   512.8      .1       0
Bank Sta=497.8,512.8
XS Rating Curve= 0 ,0
Exp/Cntr=0.3,0.1

Type RM Length L Ch R = 1 ,44996.8 ,298.8,294.4,287.4
XS GIS Cut Line= 3
     1987807.758      322614.868     1987748.882      323164.259
     1987658.953      323701.189
#Sta/Elev= 30
       0 2689.72    29.6 2669.53   108.5 2617.63   138.1 2599.16   167.7 2581.76
   197.3 2565.43     296 2519.41   335.5 2504.44   365.1  2496.3   434.1 2481.14
   544.3 2459.28   552.5 2458.59   559.3 2458.93   621.8 2467.83   681.2 2480.75
   720.8 2488.46   730.7 2489.42     800 2491.96   859.4 2495.84   889.1 2496.92
     899  2496.8   908.9 2495.53   948.5 2485.79   978.2 2479.77   988.1 2478.99
  1007.9 2482.26  1027.7 2482.04  1037.6 2483.77  1047.4 2488.15    1097 2515.77
#Mann= 3 , 0 , 0
       0      .1       0   544.3    .045       0   559.3      .1       0
Bank Sta=544.3,559.3
XS Rating Curve= 0 ,0
Exp/Cntr=0.3,0.1

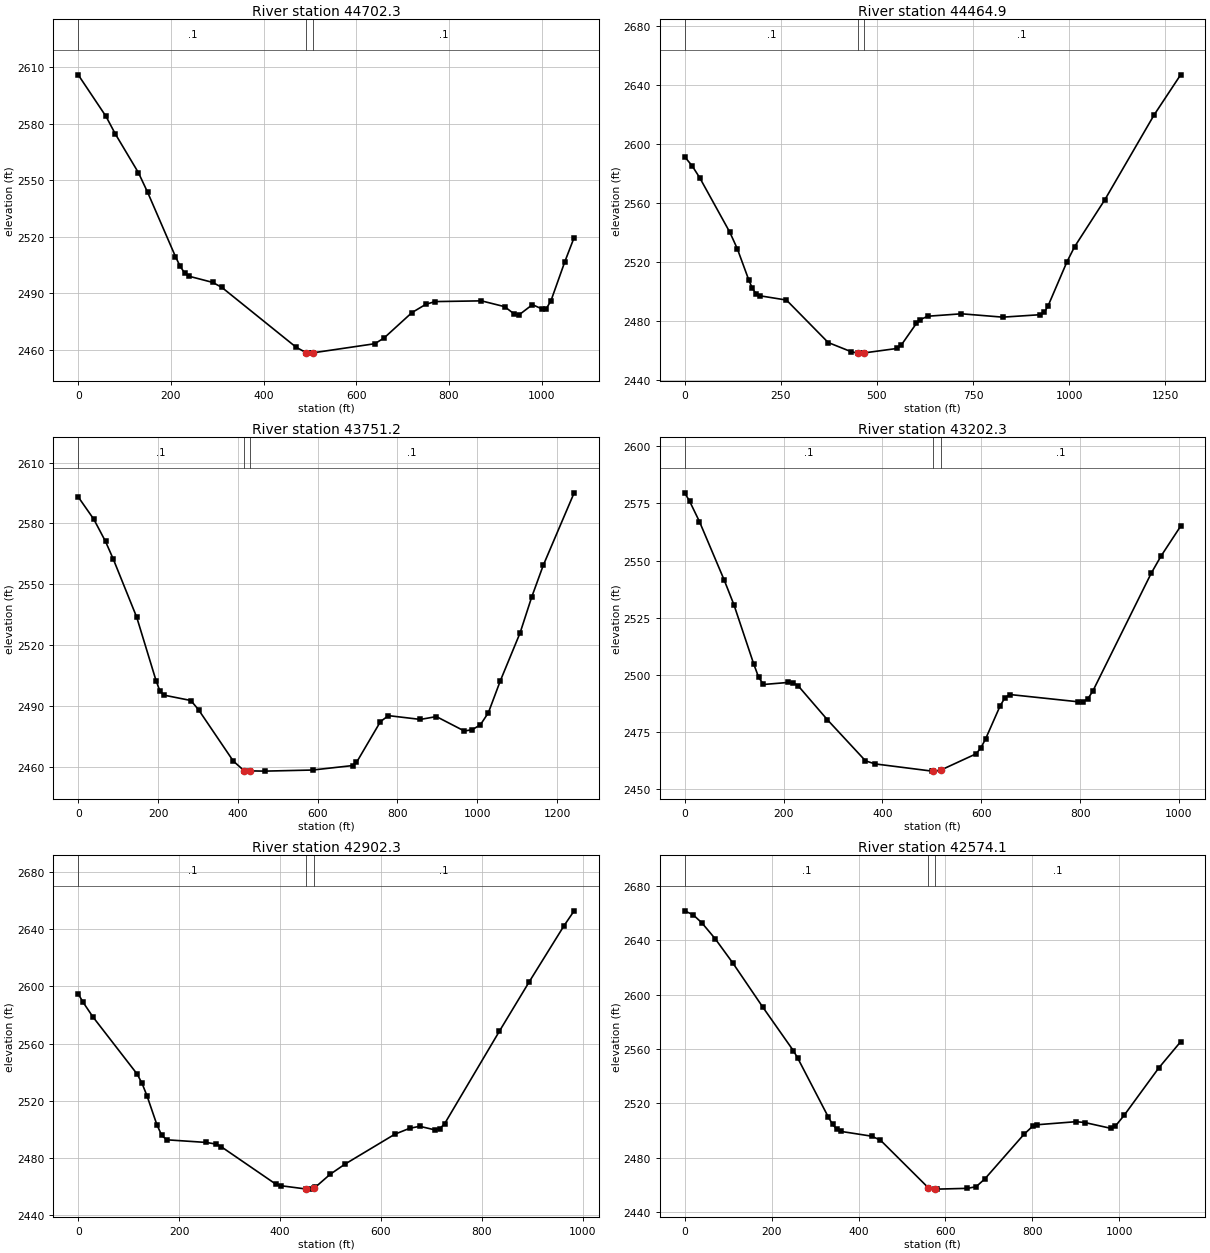
Type RM Length L Ch R = 1 ,44702.3 ,239.8,237.1,236.9
XS GIS Cut Line= 4
     1987452.799      322626.098      1987437.71      322855.427
      1987461.59       323124.62     1987543.998      323688.801
#Sta/Elev= 30
       0 2605.99      60  2583.9    79.9 2574.67   129.9 2554.03   149.9 2543.55
   209.8  2509.5   219.8 2504.38   229.8 2500.69   239.8 2498.99   289.9 2495.78
   309.9 2493.12     470 2461.38   492.6 2458.33   500.1  2458.2   507.6  2458.4
   640.1  2463.2   660.1 2466.26   720.1 2479.72   750.2 2484.13   770.2 2485.57
   870.2 2485.96   920.2 2482.87   940.2 2479.11   950.2 2478.32   980.2 2483.95
  1000.2 2481.72  1010.2 2481.88  1020.2 2486.04  1050.2 2506.84  1070.2  2519.6
#Mann= 3 , 0 , 0
       0      .1       0   492.6    .045       0   507.6      .1       0
Bank Sta=492.6,507.6
XS Rating Curve= 0 ,0
Exp/Cntr=0.3,0.1

Type RM Length L Ch R = 1 ,44464.9 ,693.5,713.2,732.2
XS GIS Cut Line= 6
      1987187.75      322714.447     1987192.048      322890.521
     1987215.444      323065.994     1987264.576        323290.6
      1987309.03      323590.074     1987379.219      323987.813
#Sta/Elev= 30
       0 2591.45    19.6 2585.19    39.1  2577.2   117.4 2540.19     137 2528.92
   166.3 2508.09   176.1 2502.03     186 2498.36   195.8 2497.05   264.6 2494.17
   373.2 2465.34   433.1 2459.09   450.3  2458.2   453.1 2458.14   465.3 2458.24
   553.1 2461.34   563.1 2463.55   602.6 2478.32   612.4 2480.83   631.9 2483.18
   719.8 2484.84   827.2 2482.56   925.2 2484.24   935.1 2485.77   944.9 2490.14
   994.2 2520.17  1013.9 2530.33  1092.7 2562.28  1220.8 2619.86  1289.7 2647.06
#Mann= 3 , 0 , 0
       0      .1       0   450.3    .045       0   465.3      .1       0
Bank Sta=450.3,465.3
XS Rating Curve= 0 ,0
Exp/Cntr=0.3,0.1

Type RM Length L Ch R = 1 ,43751.2 ,529.9,548,566.9
XS GIS Cut Line= 5
     1987121.488      322696.041     1987042.311      322853.087
     1986887.894      323063.655     1986483.037      323573.138
     1986384.871      323693.018
#Sta/Elev= 30
       0 2593.05    39.1 2582.03    68.4 2571.09    87.9 2562.37   146.6 2533.72
   195.2 2502.36   204.9 2497.21   214.6 2495.31   282.3 2492.65   301.6 2488.07
   388.6 2462.78   415.8 2458.02   430.8 2457.95     467 2457.82   587.2 2458.36
   687.3 2460.56   697.3  2462.1   757.4 2482.26   777.4 2485.19   857.5 2483.32
   897.5 2484.72   967.6 2477.59   987.6 2478.28  1007.7 2480.66  1027.7  2486.6
  1057.7 2502.37  1107.1 2525.93  1136.2 2543.59  1165.2 2559.28  1242.7 2595.07
#Mann= 3 , 0 , 0
       0      .1       0   415.8    .045       0   430.8      .1       0
Bank Sta=415.8,430.8
XS Rating Curve= 0 ,0
Exp/Cntr=0.3,0.1

Type RM Length L Ch R = 1 ,43202.3 ,295.1,300.1,303.7
XS GIS Cut Line= 4
     1987063.367      322710.369     1986808.346      322846.068
     1986589.408      322877.502     1986098.039      322919.954
#Sta/Elev= 30
       0 2579.59      10 2575.91    29.9 2567.01    79.7 2541.59    99.6 2530.69
   139.5 2504.89   149.4 2499.08   159.4 2495.81   209.2  2496.7   219.2 2496.52
   229.1 2495.35   288.9 2480.35   365.8 2462.44     385  2461.1   500.4 2457.94
   502.6 2457.94   517.6 2458.34     589 2465.45   598.8 2467.93   608.7    2472
   638.3 2486.52   648.2  2490.1     658 2491.42   796.1 2488.25     806 2488.24
   815.8 2489.59   825.7 2492.94   944.1 2544.55   963.8 2551.99  1003.3    2565
#Mann= 3 , 0 , 0
       0      .1       0   502.6    .045       0   517.6      .1       0
Bank Sta=502.6,517.6
XS Rating Curve= 0 ,0
Exp/Cntr=0.3,0.1

Type RM Length L Ch R = 1 ,42902.3 ,325.7,327.9,330.2
XS GIS Cut Line= 4
     1987084.424       322572.33     1986930.008      322593.387
     1986626.108      322587.578     1986103.108      322579.587
#Sta/Elev= 30
       0 2594.78     9.7 2588.88    29.2 2578.63   116.9 2538.54   126.6    2532
   136.4 2523.28   155.8 2503.22   165.6 2495.56   175.5 2492.53   253.9 2490.67
   273.5 2489.51   283.3 2487.71   391.2 2461.55     401 2460.38   452.3 2458.01
   459.8 2457.96   467.3 2458.93   469.7 2459.24   499.3 2468.35   528.9 2475.52
   627.6 2496.46   657.2 2500.62   676.9 2501.98   706.5 2499.51   716.4 2500.22
   726.3 2503.86   834.8 2568.67     894 2603.33   963.1  2642.7   982.9 2652.99
#Mann= 3 , 0 , 0
       0      .1       0   452.3    .045       0   467.3      .1       0
Bank Sta=452.3,467.3
XS Rating Curve= 0 ,0
Exp/Cntr=0.3,0.1

Type RM Length L Ch R = 1 ,42574.1 ,257.6,256,254.5
XS GIS Cut Line= 2
     1987332.978      322406.999     1986204.719      322235.422
#Sta/Elev= 30
       0 2661.64      20  2658.6      40 2652.62    70.1 2641.12   110.1 2623.56
   180.2 2590.56   250.3 2558.64   260.3 2553.14   330.4 2509.97   340.4 2504.44
   350.4 2500.79   360.4 2499.28   430.5 2495.79   450.5 2492.86   560.2 2457.98
   575.2 2456.85   580.6 2456.84   650.7 2457.42   670.7 2458.63   690.8  2464.4
   780.8 2497.19   800.9 2503.17   810.9 2504.22     901 2506.48     921 2505.83
   981.1 2501.54   991.1 2503.21  1011.1  2511.1  1091.2 2546.13  1141.2 2565.27
#Mann= 3 , 0 , 0
       0      .1       0   560.2    .045       0   575.2      .1       0
Bank Sta=560.2,575.2
XS Rating Curve= 0 ,0
Exp/Cntr=0.3,0.1

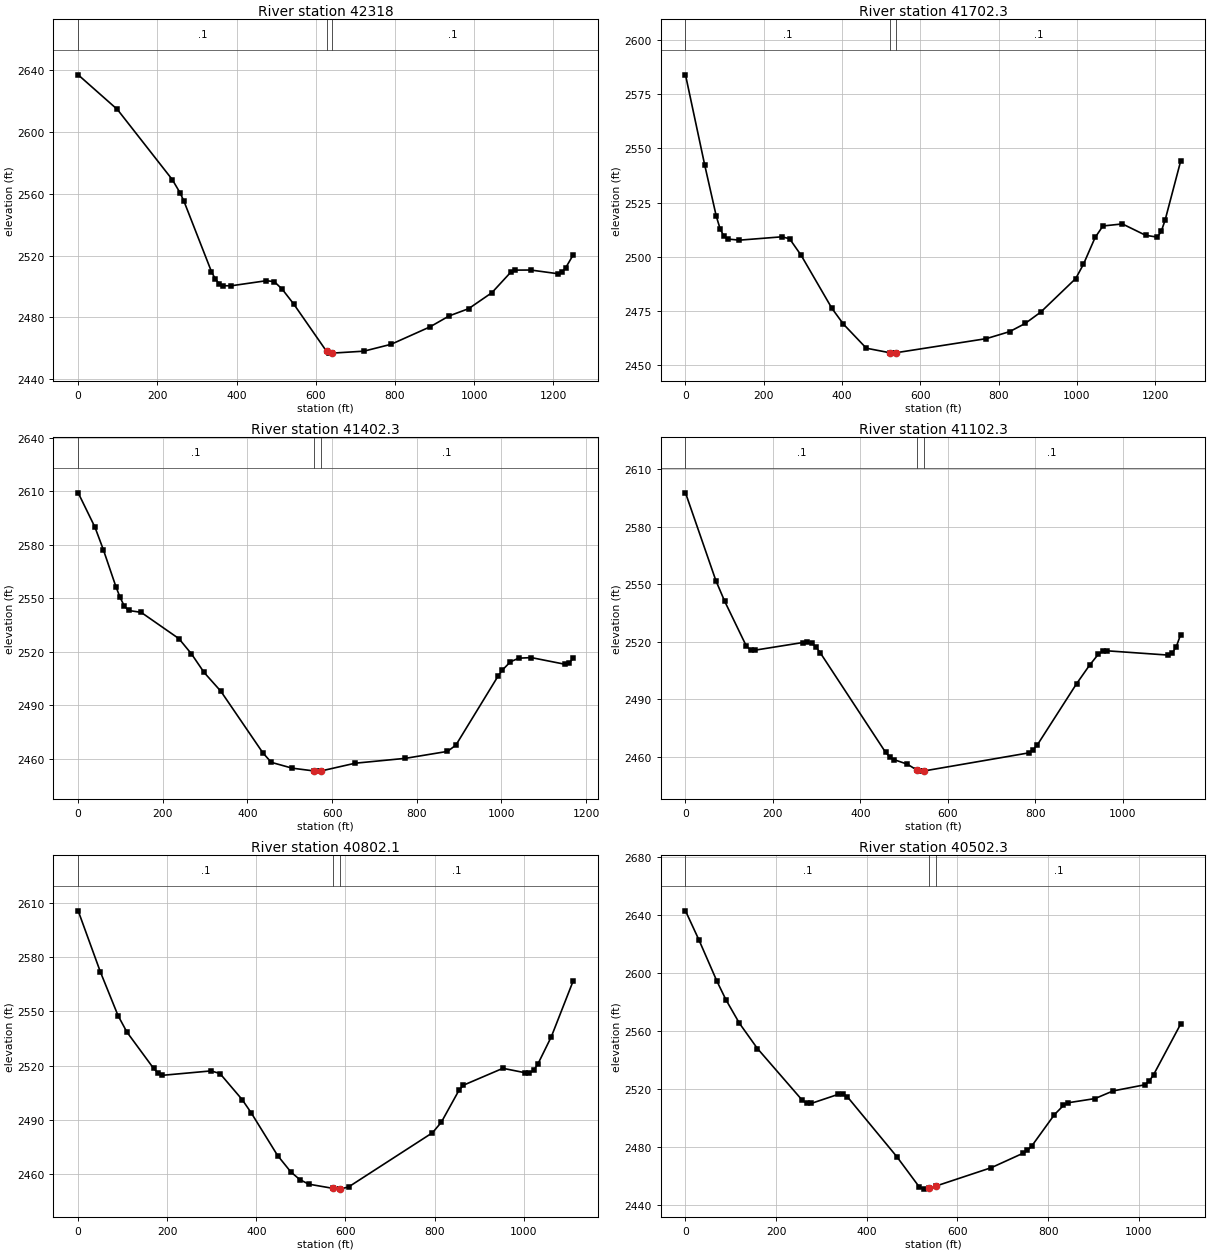
Type RM Length L Ch R = 1 ,42318   ,624.3,614.8,601.2
XS GIS Cut Line= 4
     1987482.163      322132.478     1986890.234      322083.345
     1986665.641      322064.182     1986234.859      322062.227
#Sta/Elev= 30
       0 2637.19      99 2614.73   237.6 2569.28   257.4 2560.64   267.3 2555.11
   336.6 2509.57   346.5  2504.7   356.4 2501.71   366.3 2500.48   386.1 2500.44
   475.2 2503.74     495 2503.15   514.8 2498.35   544.5 2488.52     627 2458.01
   633.2  2456.8     642 2456.81   721.4 2458.07     790 2462.52   887.9 2473.77
   936.9 2480.95   985.8 2485.61  1044.6 2495.99  1093.5  2509.6  1103.3  2510.6
  1142.5 2510.67    1211 2508.28  1220.8  2509.3  1230.6    2512  1250.2 2520.65
#Mann= 3 , 0 , 0
       0      .1       0     627    .045       0     642      .1       0
Bank Sta=627,642
XS Rating Curve= 0 ,0
Exp/Cntr=0.3,0.1

Type RM Length L Ch R = 1 ,41702.3 ,313.4,299.6,266.8
XS GIS Cut Line= 4
     1987185.056      321262.894     1986939.366      321545.228
      1986802.78      321620.935     1986181.323      322013.156
#Sta/Elev= 30
       0 2583.94    49.2 2542.24    78.8  2518.6    88.6  2512.8    98.5 2509.36
   108.3 2508.15   137.9 2507.64   246.2 2509.18   265.9  2508.3   295.5 2500.66
   374.3 2476.13   403.6 2468.87   462.1 2457.77   522.9 2455.65   530.4  2455.5
   537.9 2455.68   768.8 2462.19   828.4 2465.43   868.1  2469.2   907.8 2474.44
   997.2 2489.93    1017 2496.56  1046.8 2508.89  1066.7 2514.18  1116.4 2515.13
  1175.9 2509.87  1205.7 2509.05  1215.7 2511.67  1225.6  2516.9  1265.3 2544.12
#Mann= 3 , 0 , 0
       0      .1       0   522.9    .045       0   537.9      .1       0
Bank Sta=522.9,537.9
XS Rating Curve= 0 ,0
Exp/Cntr=0.3,0.1

Type RM Length L Ch R = 1 ,41402.3 ,304.3,300,321.7
XS GIS Cut Line= 3
     1987060.854      321135.254     1986607.889      321473.164
     1986168.537       321888.81
#Sta/Elev= 30
       0 2609.02    39.7 2589.71    59.5 2577.11    89.2 2556.36    99.1 2550.31
   109.1 2545.47     119 2543.02   148.7 2541.99     238 2527.23   267.7 2518.67
   297.4 2508.29   337.1 2497.72   436.2 2463.24   456.1 2457.86   505.6 2454.58
   557.6 2453.01   565.1 2452.92   572.6 2452.95   654.4 2457.36   773.3  2460.1
   872.5 2463.99   892.3 2467.47   991.5    2506  1001.4 2509.42  1021.2 2514.22
    1041 2516.28  1070.8 2516.59  1150.1 2512.86    1160 2513.57  1169.9 2516.35
#Mann= 3 , 0 , 0
       0      .1       0   557.6    .045       0   572.6      .1       0
Bank Sta=557.6,572.6
XS Rating Curve= 0 ,0
Exp/Cntr=0.3,0.1

Type RM Length L Ch R = 1 ,41102.3 ,293.6,299.9,300.7
XS GIS Cut Line= 3
      1986531.29      320809.156     1986393.513       321328.47
     1986104.314      321848.934
#Sta/Elev= 30
       0 2597.81    69.6  2551.9    89.6 2541.18   139.3  2517.7   149.2 2515.72
   159.2 2515.62   268.6 2519.61   278.6 2519.81   288.5 2519.23   298.5 2517.29
   308.4  2514.2   457.7 2462.24   467.6 2459.75   477.6 2458.38   507.4 2456.05
   529.8 2452.92   537.3 2452.42   544.8 2452.48   785.4 2461.96   795.3 2463.59
   805.2 2466.24   894.5 2498.05   924.3 2507.75   944.2 2513.44   954.1 2515.07
     964 2515.28  1102.9 2513.06  1112.8  2513.9  1122.8 2517.48  1132.7 2523.77
#Mann= 3 , 0 , 0
       0      .1       0   529.8    .045       0   544.8      .1       0
Bank Sta=529.8,544.8
XS Rating Curve= 0 ,0
Exp/Cntr=0.3,0.1

Type RM Length L Ch R = 1 ,40802.1 ,300.7,299.7,299.3
XS GIS Cut Line= 3
     1986411.333      320765.272     1986039.794      321377.548
     1985764.482      321661.038
#Sta/Elev= 30
       0 2605.76    49.7 2571.99    89.5 2547.67   109.4 2538.55   169.1 2518.48
     179 2515.94     189 2514.58   298.4 2517.03   318.3 2515.56     368 2501.15
   387.9 2493.97   447.6 2470.13   477.5 2460.98   497.4 2456.81   517.2 2454.27
   572.4  2451.9   586.9  2451.5   587.4 2451.51   606.8 2452.69   795.2 2482.75
     815 2488.55   854.5 2506.19   864.4 2509.08   953.3 2518.47  1002.7 2516.03
  1012.6 2515.92  1022.4 2517.29  1032.3 2521.08    1062 2535.99  1111.4 2567.13
#Mann= 3 , 0 , 0
       0      .1       0   572.4    .045       0   587.4      .1       0
Bank Sta=572.4,587.4
XS Rating Curve= 0 ,0
Exp/Cntr=0.3,0.1

Type RM Length L Ch R = 1 ,40502.3 ,295.3,300,303.7
XS GIS Cut Line= 3
     1986142.154       320604.82     1985881.773      321084.431
      1985609.51      321558.574
#Sta/Elev= 30
       0  2643.1    29.8 2622.95    69.5  2594.5    89.3 2581.76   119.1 2565.54
   158.8 2548.16     258 2512.42   267.9 2510.42   277.8  2510.4   337.4 2516.64
   347.3 2516.64   357.2 2514.91   466.4 2473.59     516  2452.7   525.9 2451.28
   538.2 2451.86   553.2 2453.47     675  2466.1   744.6 2475.99   754.5 2477.96
   764.4 2481.18   814.1 2502.67     834 2508.97     844  2510.8   903.6  2513.7
   943.4 2518.96    1013 2523.17  1022.9 2525.62  1032.8 2530.16  1092.5 2565.07
#Mann= 3 , 0 , 0
       0      .1       0   538.2    .045       0   553.2      .1       0
Bank Sta=538.2,553.2
XS Rating Curve= 0 ,0
Exp/Cntr=0.3,0.1

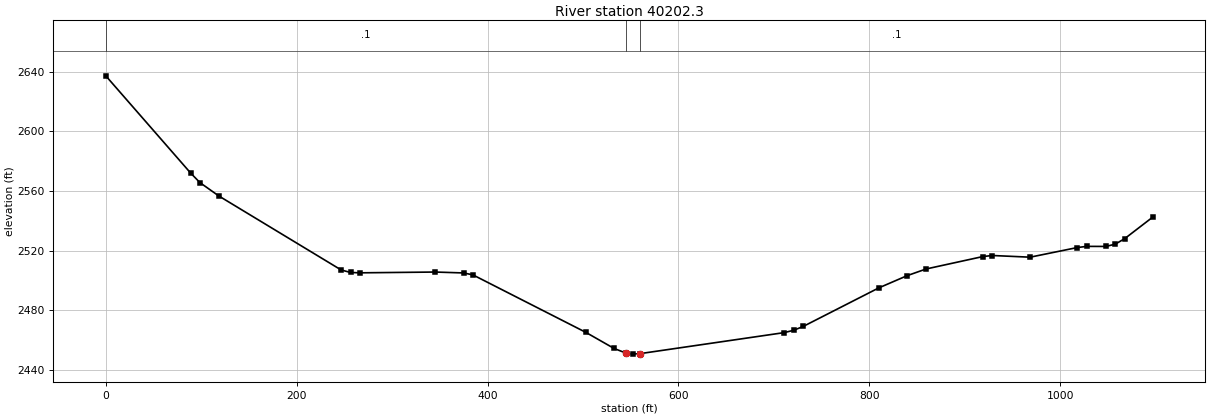
Type RM Length L Ch R = 1 ,40202.3 ,309.9,300,293.6
XS GIS Cut Line= 3
     1985980.369      320517.091       1985622.1      320937.428
     1985277.057      321359.148
#Sta/Elev= 30
       0 2637.34    88.8 2572.17    98.6  2565.7   118.4 2556.73   246.6 2507.05
   256.4 2505.38   266.3 2505.13   345.2 2505.66   374.8 2505.05   384.6 2503.77
     503 2465.16   532.6 2454.35   544.8 2451.32   552.3 2450.57   559.8 2450.91
   710.8 2465.01   720.7 2466.58   730.6 2469.13   809.9 2495.03   839.6 2503.24
   859.4 2507.71   918.9 2516.05   928.8 2516.76   968.4 2515.63  1017.9 2522.11
  1027.8 2522.88  1047.7 2522.84  1057.6 2524.37  1067.5 2528.07  1097.2 2542.68
#Mann= 3 , 0 , 0
       0      .1       0   544.8    .045       0   559.8      .1       0
Bank Sta=544.8,559.8
XS Rating Curve= 0 ,0
Exp/Cntr=0.3,0.1