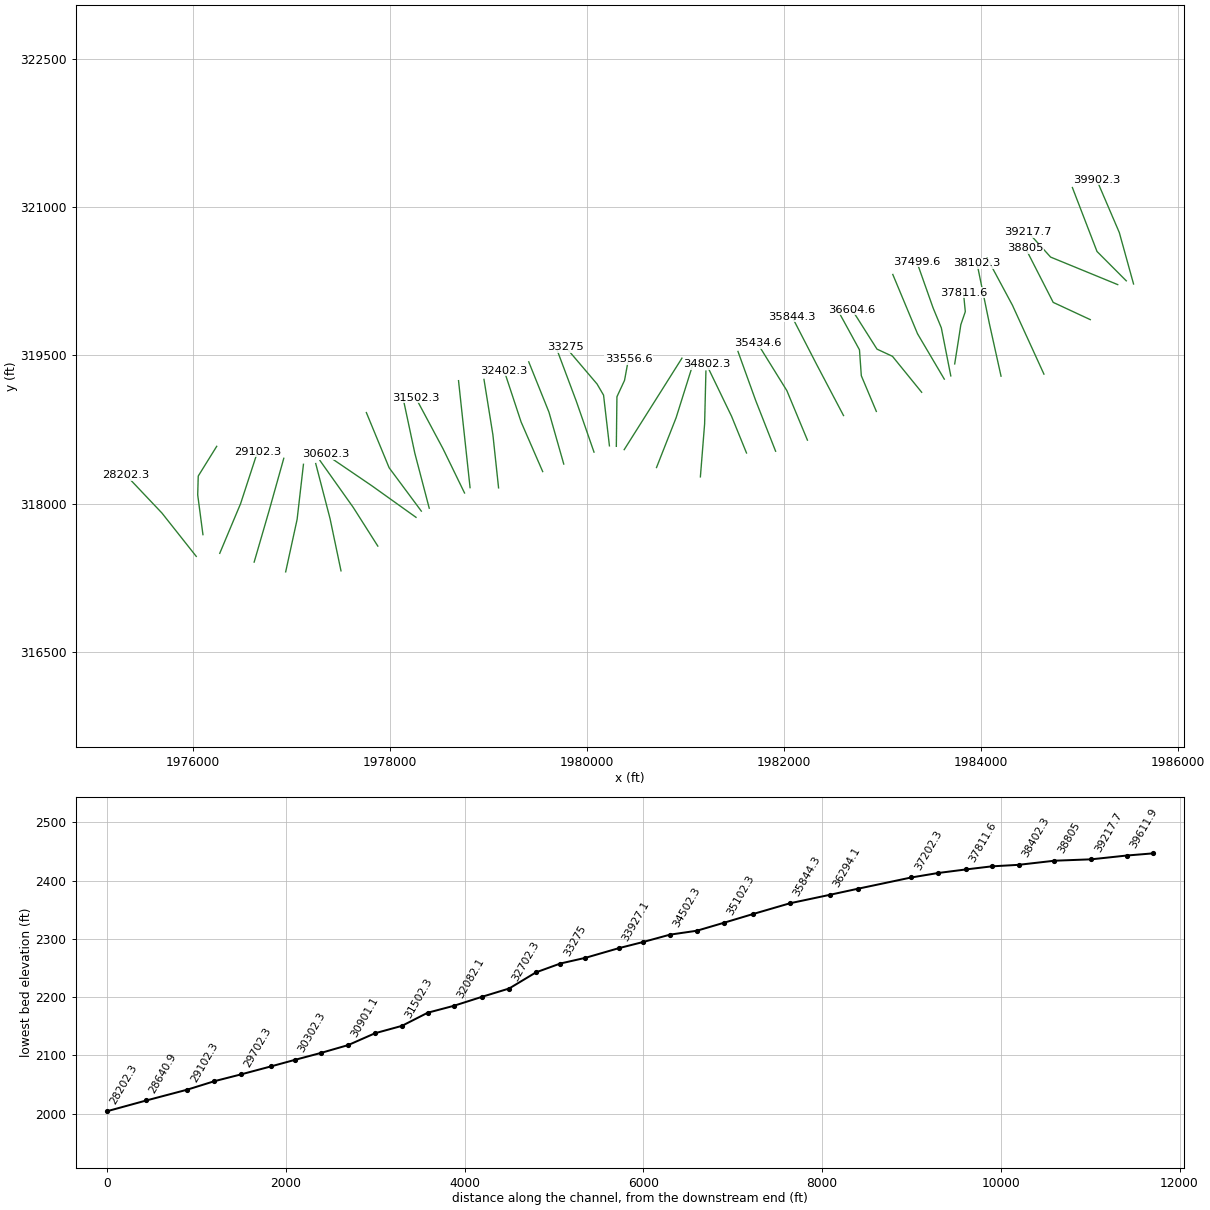
HEC-RAS study LaurelCrk.prj: LaurelCrk

--- LaurelCrk.g01 (geometry) --- (continued)

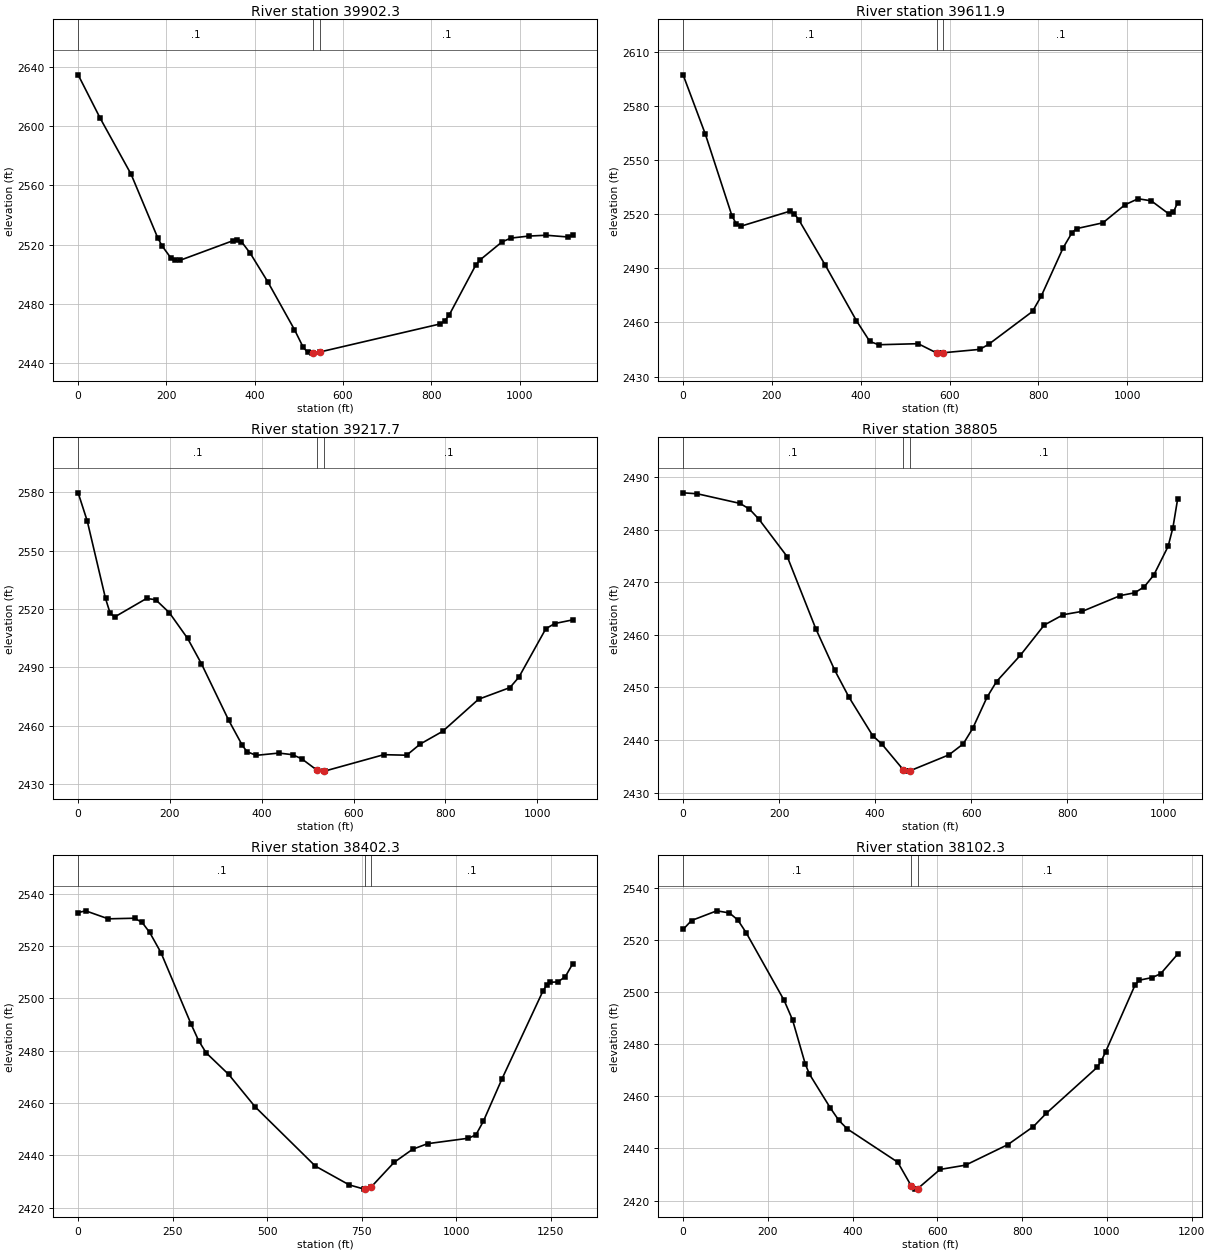
Type RM Length L Ch R = 1 ,39902.3 ,288.1,290.4,289.6
XS GIS Cut Line= 3
     1985546.665      320222.751     1985402.156       320742.98
     1985172.937      321276.213
#Sta/Elev= 30
       0 2634.69      50 2605.33     120 2567.49     180 2524.75     190 2519.16
     210 2510.96     220 2509.28     230 2509.28     350 2522.54     360 2523.13
     370 2521.95     390 2514.05   429.9 2494.67   489.9 2462.59   509.9 2450.52
   519.9 2447.24   529.9 2446.65   532.4 2446.73   547.4 2447.41   820.1 2466.38
   830.1 2468.38   840.1 2472.19   900.2 2505.87   910.2 2509.59   960.2 2521.82
   980.2 2524.37  1020.3 2525.73  1060.3  2526.3  1110.3 2525.11  1120.3  2526.4
#Mann= 3 , 0 , 0
       0      .1       0   532.4    .045       0   547.4      .1       0
Bank Sta=532.4,547.4
XS Rating Curve= 0 ,0
Exp/Cntr=0.3,0.1

Type RM Length L Ch R = 1 ,39611.9 ,375.9,394.3,412.7
XS GIS Cut Line= 3
     1985472.815      320254.493     1985175.696      320551.612
     1984926.002      321198.156
#Sta/Elev= 30
       0 2597.28      50 2564.42     110 2519.07     120 2514.51   130.1 2513.35
   240.1 2521.66   250.1 2520.33   260.1 2517.05   320.1 2491.73   390.2 2460.96
   420.2 2449.49     440 2447.64   529.1 2448.22   570.5 2443.12   578.6 2442.99
   585.5 2443.19   667.7 2445.07   687.5 2447.82   786.5  2466.1   806.3 2474.66
   855.8 2501.53   875.6 2509.81   885.6 2512.01     945 2515.24   994.5  2525.2
  1024.2 2528.58  1053.9 2527.42  1093.5 2520.14  1103.4 2520.99  1113.3 2526.47
#Mann= 3 , 0 , 0
       0      .1       0   570.5    .045       0   585.5      .1       0
Bank Sta=570.5,585.5
XS Rating Curve= 0 ,0
Exp/Cntr=0.3,0.1

Type RM Length L Ch R = 1 ,39217.7 ,428.7,412.6,396.5
XS GIS Cut Line= 3
     1985385.845      320216.312     1984705.009      320494.729
     1984475.149      320747.874
#Sta/Elev= 30
       0  2579.8    19.9 2565.22    59.6 2525.45    69.6 2517.88    79.5 2515.88
   149.1 2525.43     169 2524.76   198.8 2518.06   238.6 2504.81   268.4  2491.9
     328 2462.71   357.8 2449.74   367.8 2446.56   387.7 2444.64   437.4 2445.82
   467.2 2444.98   487.1 2442.86   520.6 2436.97   535.6 2436.53   536.8 2436.52
     666 2444.99   715.7 2444.71   745.3 2450.47   794.2 2457.02   872.3 2473.52
   940.7 2479.53   960.3 2484.92  1018.9 2509.83  1038.4 2512.51  1077.5 2514.39
#Mann= 3 , 0 , 0
       0      .1       0   520.6    .045       0   535.6      .1       0
Bank Sta=520.6,535.6
XS Rating Curve= 0 ,0
Exp/Cntr=0.3,0.1

Type RM Length L Ch R = 1 ,38805   ,403.7,402.7,403.1
XS GIS Cut Line= 3
     1985107.549      319861.969      1984731.38      320036.424
     1984450.617      320584.323
#Sta/Elev= 30
       0 2486.99    29.6 2486.81   118.5 2484.98   138.2  2483.9     158 2481.97
   217.2 2474.81   276.4 2461.17   315.9 2453.27   345.5 2448.16   394.9 2440.85
   414.6 2439.18   458.4 2434.39   464.3  2434.1   473.4 2434.19   553.7 2437.19
   583.5 2439.27   603.3 2442.22   633.1 2448.14     653 2451.13   702.6 2456.12
   752.3 2461.86     792 2463.83   831.7 2464.47   911.1 2467.47   940.9 2467.99
   960.8 2469.14   980.6 2471.37  1010.4 2476.82  1020.4 2480.38  1030.3 2485.86
#Mann= 3 , 0 , 0
       0      .1       0   458.4    .045       0   473.4      .1       0
Bank Sta=458.4,473.4
XS Rating Curve= 0 ,0
Exp/Cntr=0.3,0.1

Type RM Length L Ch R = 1 ,38402.3 ,305.1,300,293
XS GIS Cut Line= 3
     1984637.159       319310.87     1984317.594      320007.763
     1984060.859      320484.556
#Sta/Elev= 30
       0 2532.85    19.9 2533.52    79.6 2530.46   149.4 2530.69   169.3 2529.07
   189.2 2525.26     219 2517.54   298.7 2490.19   318.6 2483.86   338.5  2479.2
   398.3  2470.9     468 2458.55   627.3 2435.86   716.9 2428.66   756.7 2427.03
   759.2 2427.05   774.2 2427.71   835.6 2437.25   884.8 2442.29   924.2 2444.42
  1032.5 2446.51  1052.2 2447.81  1071.9 2453.01  1121.1 2469.21  1229.4 2502.81
  1239.3 2505.14  1249.1 2506.18  1268.8 2506.32  1288.5  2508.3  1308.2 2513.26
#Mann= 3 , 0 , 0
       0      .1       0   759.2    .045       0   774.2      .1       0
Bank Sta=759.2,774.2
XS Rating Curve= 0 ,0
Exp/Cntr=0.3,0.1

Type RM Length L Ch R = 1 ,38102.3 ,302.8,290.7,279
XS GIS Cut Line= 3
     1984201.986      319289.814     1984083.404      319822.914
      1983957.78      320430.874
#Sta/Elev= 30
       0 2523.99    19.9 2527.41    79.4 2531.12   109.2 2530.31   129.1 2527.61
   148.9  2522.7   238.3  2496.8   258.2  2489.3     288 2472.52   297.9 2468.55
   347.5  2455.5   367.4 2450.78   387.3 2447.51   506.4 2434.74   538.6 2425.55
   546.1 2424.41   553.6 2424.61   606.2 2431.96   666.3  2433.6   766.4 2441.49
   826.5  2448.4   856.5 2453.42   976.7 2471.08   986.7 2473.56   996.7 2477.02
  1066.8 2502.85  1076.8 2504.54  1106.8 2505.53  1126.9 2507.02  1166.9 2514.52
#Mann= 3 , 0 , 0
       0      .1       0   538.6    .045       0   553.6      .1       0
Bank Sta=538.6,553.6
XS Rating Curve= 0 ,0
Exp/Cntr=0.3,0.1

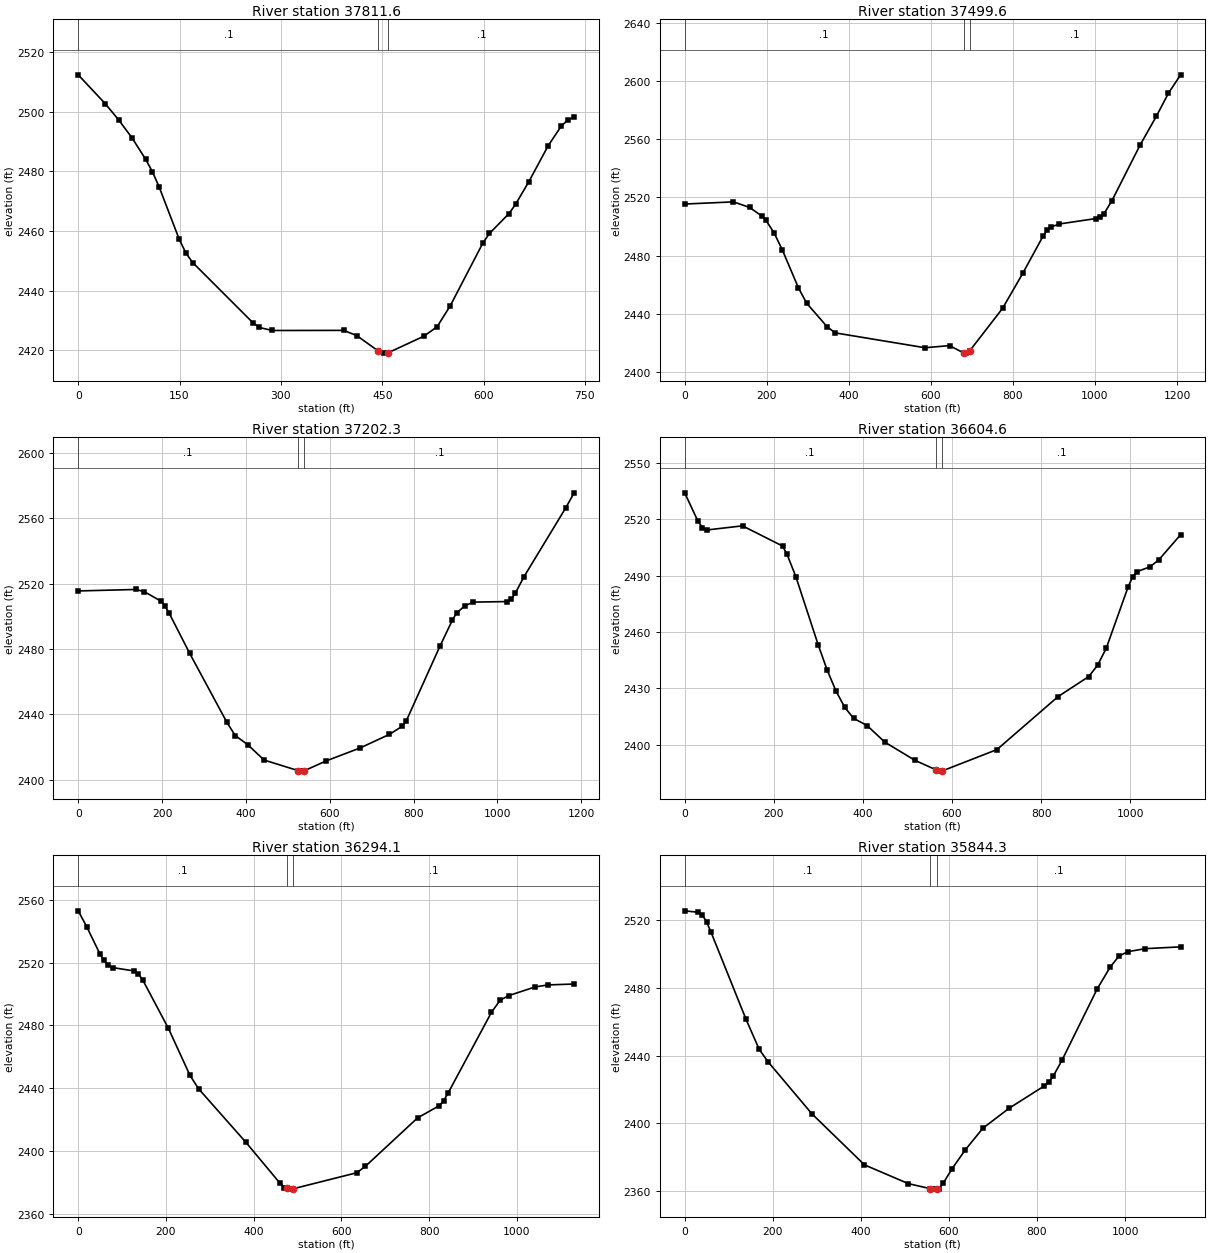
Type RM Length L Ch R = 1 ,37811.6 ,295.6,312,328.5
XS GIS Cut Line= 5
     1983731.718      319413.815     1983769.153      319650.118
     1983794.054      319811.321     1983839.342      319942.574
     1983820.625      320134.424
#Sta/Elev= 30
       0 2512.29    39.9 2502.65    59.8 2497.22    79.8 2491.12    99.7 2484.05
   109.7 2479.87   119.6 2474.84   149.5 2457.21   159.5 2452.55   169.5  2449.4
   258.4 2429.29     268 2427.68   287.2 2426.66   392.8  2426.7   412.3 2424.95
   444.2 2419.77     452 2419.08   459.2 2419.26   511.5 2424.74   531.3 2427.94
   550.8 2435.01     599    2456   608.7 2459.18   637.6 2465.82   647.2 2468.91
   666.5 2476.31   695.4 2488.49   714.7 2495.04   724.3 2497.11     734 2498.11
#Mann= 3 , 0 , 0
       0      .1       0   444.2    .045       0   459.2      .1       0
Bank Sta=444.2,459.2
XS Rating Curve= 0 ,0
Exp/Cntr=0.3,0.1

Type RM Length L Ch R = 1 ,37499.6 ,293.7,297.3,296.3
XS GIS Cut Line= 4
     1983692.171      319292.878     1983596.019      319778.799
     1983511.792      319982.347     1983347.035      320447.059
#Sta/Elev= 30
       0 2515.42   118.9 2516.92   158.5 2513.05   188.2 2507.13   198.1 2504.23
     218 2495.55   237.8 2484.01   277.4 2457.73   297.2 2447.29   346.7 2431.24
   366.6 2426.88   585.5 2416.66   645.5 2418.12   679.6 2413.12   685.6 2412.95
   694.6  2414.5   774.8 2443.74   824.1 2467.86   873.4 2493.34   883.3 2497.42
   893.1 2499.64   912.8  2501.7  1001.6 2505.43  1011.5 2506.25  1021.3 2508.51
    1041 2517.59  1110.1 2556.05  1149.5 2575.73  1179.1 2591.64  1208.7 2604.24
#Mann= 3 , 0 , 0
       0      .1       0   679.6    .045       0   694.6      .1       0
Bank Sta=679.6,694.6
XS Rating Curve= 0 ,0
Exp/Cntr=0.3,0.1

Type RM Length L Ch R = 1 ,37202.3 ,583.7,597.5,615.9
XS GIS Cut Line= 3
      1983626.01      319260.379     1983354.887      319718.341
     1983103.629      320318.945
#Sta/Elev= 30
       0 2515.49     138  2516.4   157.7 2515.02   197.1 2509.32     207 2506.28
   216.8 2501.98   266.1 2477.26   354.8 2435.12   374.5  2427.1   404.1 2421.57
   443.5 2412.11   524.7 2405.64   532.2 2405.33   539.7  2405.6   592.3 2411.66
   672.4 2419.48   742.5 2427.81   772.6 2432.68   782.6    2436   862.7 2481.55
   892.8 2497.72   902.8 2502.03   922.8 2506.49   942.9 2508.66    1023    2509
    1033 2510.48    1043 2514.22    1063 2523.96  1163.2 2566.32  1183.2 2575.48
#Mann= 3 , 0 , 0
       0      .1       0   524.7    .045       0   539.7      .1       0
Bank Sta=524.7,539.7
XS Rating Curve= 0 ,0
Exp/Cntr=0.3,0.1

Type RM Length L Ch R = 1 ,36604.6 ,334.6,310.4,286.2
XS GIS Cut Line= 4
     1983396.454      319127.261     1983100.015      319491.023
     1982943.259      319563.552     1982690.578      319961.291
#Sta/Elev= 30
       0 2533.99      30 2518.81    39.9 2515.54    49.9 2514.24   129.8 2516.43
   219.6  2505.7   229.6 2501.36   249.6 2489.38   299.5 2453.27   319.5 2439.93
   339.5 2428.65   359.4 2419.86   379.4 2414.03   409.4 2410.22   449.3 2401.38
   517.2 2391.68   563.5 2386.75   574.8 2385.98   578.5 2386.11   700.9 2397.44
   838.3 2425.65     907 2436.28   926.7 2442.26   946.3 2451.35   995.4 2483.99
  1005.2 2489.12    1015 2492.05  1044.5 2494.64  1064.1  2498.3  1113.2 2511.74
#Mann= 3 , 0 , 0
       0      .1       0   563.5    .045       0   578.5      .1       0
Bank Sta=563.5,578.5
XS Rating Curve= 0 ,0
Exp/Cntr=0.3,0.1

Type RM Length L Ch R = 1 ,36294.1 ,440.4,449.8,459.1
XS GIS Cut Line= 4
     1982936.577      318933.416     1982784.164      319294.493
     1982765.447      319556.533     1982536.274      319973.889
#Sta/Elev= 30
       0 2552.92    19.6 2542.68      49 2525.74    58.8 2521.32    68.6 2518.41
    78.4 2516.77   127.4 2514.63   137.2 2512.72     147 2508.95   205.8 2477.97
   254.8 2448.11   274.4 2439.58   382.1 2405.56     460 2379.44   469.8 2376.69
   475.4  2376.1   479.5 2375.66   490.4  2375.9   635.2  2386.1   654.6 2390.13
   773.7 2421.01   823.3 2428.82   833.2 2431.96   843.1 2436.72   942.3 2488.29
   962.1 2496.02     982 2498.95  1041.5 2504.42  1071.2 2505.73  1130.8  2506.3
#Mann= 3 , 0 , 0
       0      .1       0   475.4    .045       0   490.4      .1       0
Bank Sta=475.4,490.4
XS Rating Curve= 0 ,0
Exp/Cntr=0.3,0.1

Type RM Length L Ch R = 1 ,35844.3 ,411.3,409.7,411.3
XS GIS Cut Line= 3
     1982603.496      318891.694      1982329.27       319411.18
     1982081.783      319889.653
#Sta/Elev= 30
       0 2525.58    29.9 2524.74    39.8  2523.2    49.8 2519.04    59.7 2513.02
   139.4 2461.38   169.3 2443.63   189.2 2436.36   288.7 2405.62   408.2 2375.39
   507.8 2364.29   557.9 2361.31   567.5 2361.04   572.9 2361.24   577.5 2361.41
   587.4 2364.69   607.4  2373.2   637.3 2384.31   677.2 2397.07   737.1 2408.94
   816.9  2422.1   826.8 2424.34   836.8  2427.8   856.8 2437.27   936.6 2479.37
   966.5 2492.45   986.4 2498.87  1006.4 2501.45  1046.3 2503.22  1126.1 2504.28
#Mann= 3 , 0 , 0
       0      .1       0   557.9    .045       0   572.9      .1       0
Bank Sta=557.9,572.9
XS Rating Curve= 0 ,0
Exp/Cntr=0.3,0.1

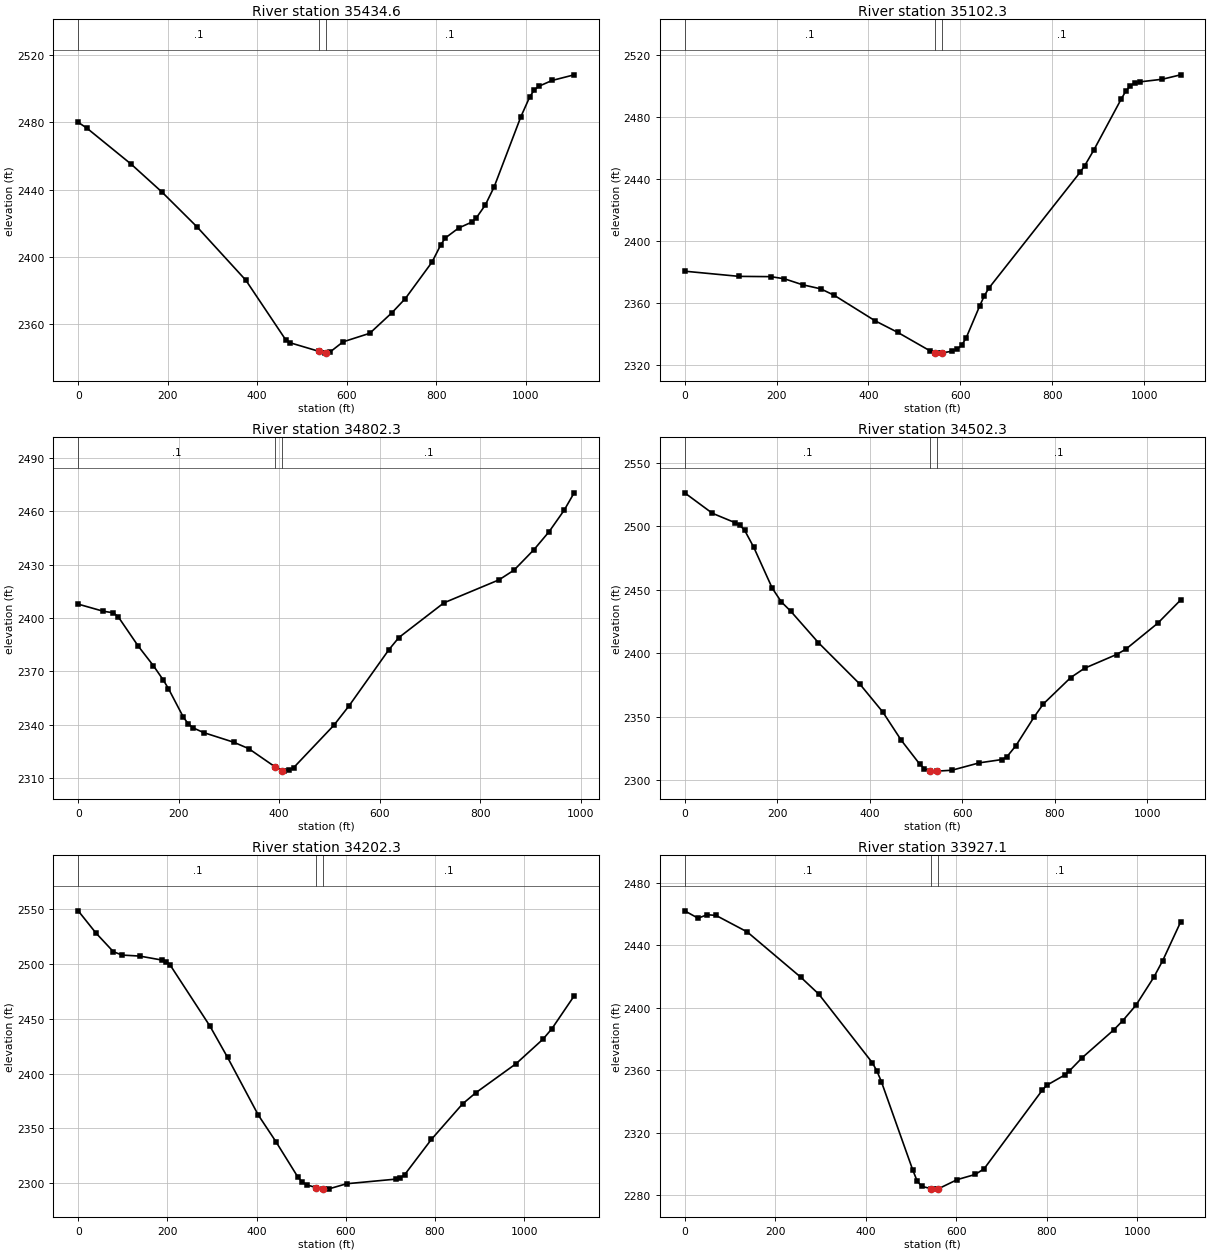
Type RM Length L Ch R = 1 ,35434.6 ,333.2,332.2,327.5
XS GIS Cut Line= 3
     1982237.206       318642.92     1982028.577      319143.631
     1981729.522      319624.401
#Sta/Elev= 30
       0 2479.98    19.7 2476.45   118.4 2455.09   187.4 2438.46   266.3  2417.6
   374.8 2386.04   463.5 2350.78   473.4  2348.9   538.6 2343.74   552.4 2342.72
   553.6 2342.79   562.3 2343.26   592.1 2349.44   651.7 2354.51   701.4 2366.78
   731.2 2375.16   790.8 2396.82   810.6 2407.19   820.6  2411.2   850.4 2417.12
   880.2 2420.68   890.1 2423.23     910 2430.79   929.8 2441.61   989.4 2483.24
  1009.3 2495.09  1019.2 2499.15  1029.2 2501.36    1059 2504.85  1108.6 2508.22
#Mann= 3 , 0 , 0
       0      .1       0   538.6    .045       0   553.6      .1       0
Bank Sta=538.6,553.6
XS Rating Curve= 0 ,0
Exp/Cntr=0.3,0.1

Type RM Length L Ch R = 1 ,35102.3 ,299.7,299.7,301.9
XS GIS Cut Line= 3
     1981914.396       318530.91      1981711.69       319045.09
     1981532.456      319540.155
#Sta/Elev= 30
       0 2380.27   118.4 2376.93   187.5 2376.75   217.1 2375.36   256.6 2371.52
   296.1 2368.88   325.7 2364.67   414.5 2348.25   463.9 2340.76     533 2329.04
   545.2 2327.72   552.7 2327.42   560.2  2327.6   582.5 2328.67   592.4 2329.81
   602.4 2332.36   612.3 2337.09   642.1 2357.96     652 2364.37     662 2369.38
   860.6 2444.12   870.6 2448.38   890.5 2458.51   950.1  2491.4     960 2496.43
   969.9 2499.95   979.9  2501.7   989.8 2502.36  1039.5 2504.09  1079.2 2506.93
#Mann= 3 , 0 , 0
       0      .1       0   545.2    .045       0   560.2      .1       0
Bank Sta=545.2,560.2
XS Rating Curve= 0 ,0
Exp/Cntr=0.3,0.1

Type RM Length L Ch R = 1 ,34802.3 ,310.4,300,289.3
XS GIS Cut Line= 3
     1981619.022      318513.053     1981468.241      318882.278
     1981211.925      319411.475
#Sta/Elev= 30
       0 2407.78    49.8 2403.79    69.8 2402.92    79.8 2400.59   119.6 2384.12
   149.6 2373.17   169.5 2365.02   179.5  2360.3   209.4 2344.14   219.4 2340.35
   229.3 2338.13   249.3 2335.58   309.1 2330.17     339 2326.58   391.3 2316.37
   406.3 2314.15   408.8 2313.89   418.8 2314.28   428.7 2315.86   508.4 2339.59
   538.4 2350.41   618.1 2382.14     638    2389   727.7 2408.52   837.3 2421.45
   867.2 2426.91   907.1  2438.5     937 2448.55   966.9 2460.58   986.8 2470.37
#Mann= 3 , 0 , 0
       0      .1       0   391.3    .045       0   406.3      .1       0
Bank Sta=391.3,406.3
XS Rating Curve= 0 ,0
Exp/Cntr=0.3,0.1

Type RM Length L Ch R = 1 ,34502.3 ,306.6,300,293.7
XS GIS Cut Line= 3
      1981151.08      318271.402     1981193.968      318807.473
     1981207.246      319341.286
#Sta/Elev= 30
       0 2526.35    59.8 2510.26   109.6 2502.74   119.5 2500.71   129.5  2496.9
   149.4  2483.4   189.2 2451.29   209.1 2440.38   229.1 2433.18   288.8 2408.44
   378.4  2375.8   428.2 2353.74   468.1 2331.49   507.9 2312.74   517.9 2309.18
   530.3 2307.49   545.3  2307.2   577.3 2307.89   636.7 2313.72   686.1 2316.34
     696 2318.36   715.8 2327.21   755.3  2349.9   775.1  2360.1   834.4 2380.92
   864.1  2388.2   933.3 2399.03   953.1 2403.14  1022.3 2423.64  1071.8 2441.94
#Mann= 3 , 0 , 0
       0      .1       0   530.3    .045       0   545.3      .1       0
Bank Sta=530.3,545.3
XS Rating Curve= 0 ,0
Exp/Cntr=0.3,0.1

Type RM Length L Ch R = 1 ,34202.3 ,279.3,275,269.2
XS GIS Cut Line= 3
     1980705.823       318365.77     1980904.714       318869.63
     1981076.121      319413.669
#Sta/Elev= 30
       0 2548.67    39.4 2528.57    78.8 2511.36    98.5 2508.27   137.9 2507.36
   187.1 2503.76     197 2502.19   206.8 2498.78   295.5 2443.35   334.9 2414.84
   403.8 2362.22   443.2    2338   492.4 2305.71   502.3 2301.01   512.2 2298.55
   534.2 2295.87   549.2 2294.71   551.7 2294.58   561.7 2294.76   601.7 2299.49
   711.8  2303.7   721.8 2304.73   731.8 2307.65   791.9 2339.95   861.9 2372.42
   891.9 2382.67     982 2409.16    1042 2431.38  1062.1 2440.99  1112.1    2471
#Mann= 3 , 0 , 0
       0      .1       0   534.2    .045       0   549.2      .1       0
Bank Sta=534.2,549.2
XS Rating Curve= 0 ,0
Exp/Cntr=0.3,0.1

Type RM Length L Ch R = 1 ,33927.1 ,367.8,370.7,373.6
XS GIS Cut Line= 3
     1980377.868      318546.751     1980673.807      319013.736
     1980963.923      319472.306
#Sta/Elev= 30
       0 2462.16    29.6 2457.44    49.4 2459.65    69.1 2459.24   138.2 2448.64
   256.7 2419.57   296.2 2408.82   414.6 2364.83   424.5 2359.64   434.4 2352.82
   503.5  2296.4   513.4 2289.18   523.2 2285.72   544.9 2284.14   552.9  2283.9
   559.9 2284.06   602.2 2290.01   641.7 2293.29   661.4 2296.91   789.6 2347.16
   799.5 2350.37     839 2356.92   848.8 2359.33   878.4 2368.17   947.5 2385.81
   967.2 2391.65   996.8 2401.67  1036.3 2419.62    1056  2430.3  1095.5    2455
#Mann= 3 , 0 , 0
       0      .1       0   544.9    .045       0   559.9      .1       0
Bank Sta=544.9,559.9
XS Rating Curve= 0 ,0
Exp/Cntr=0.3,0.1

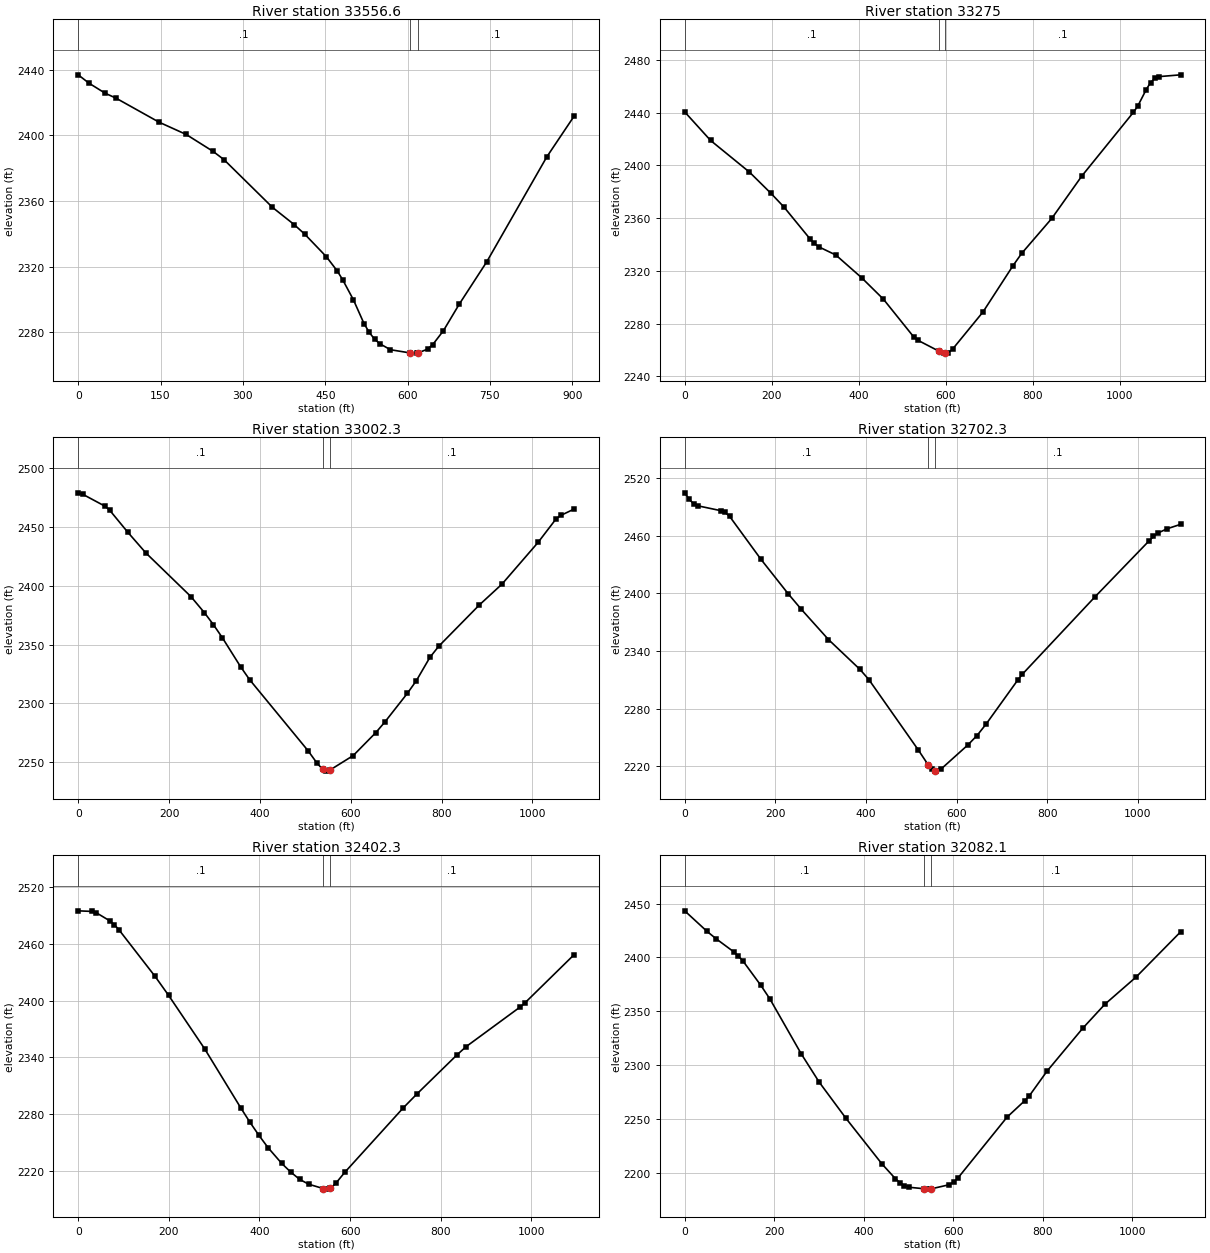
Type RM Length L Ch R = 1 ,33556.6 ,259.5,281.6,303.6
XS GIS Cut Line= 4
     1980298.051      318580.341     1980304.144      319081.586
     1980381.352        319247.7     1980421.126      319462.947
#Sta/Elev= 30
       0 2436.79    19.7 2431.69    49.2 2425.57    68.8 2422.61   147.4 2407.95
   196.6 2400.52   245.7 2390.19   265.4 2385.22   353.8 2356.15   393.2  2345.7
   412.8 2339.77   452.1 2326.08   471.8 2317.46   481.6 2312.17   501.3 2299.89
   520.6 2285.43   530.2 2280.01   539.8 2275.96   549.5 2273.12   568.8  2269.5
   603.9 2267.59     617 2267.43   618.9 2267.57   636.3 2269.84   645.9 2272.66
   665.2 2281.05   694.4 2297.39   744.2 2323.01   853.6 2386.87   903.4 2411.69
#Mann= 3 , 0 , 0
       0      .1       0   603.9    .045       0   618.9      .1       0
Bank Sta=603.9,618.9
XS Rating Curve= 0 ,0
Exp/Cntr=0.3,0.1

Type RM Length L Ch R = 1 ,33275   ,276.9,272.7,268.9
XS GIS Cut Line= 4
     1980228.006      318585.306     1980168.445      319097.963
     1980102.935      319210.266     1979782.521      319585.664
#Sta/Elev= 30
       0 2440.69    59.6 2418.98   148.9 2394.97   198.5  2378.8   228.3 2368.42
   287.8 2344.41   297.8 2340.98   307.7 2338.36   347.4 2332.06   406.9 2314.76
   456.6 2298.59   526.1 2270.01   536.1 2267.34   583.3 2259.28   596.1 2257.62
   598.3 2257.69   606.1 2257.96   616.1 2260.83   685.6 2288.88   754.7 2324.07
   774.4 2333.28   843.5 2359.78   912.6 2391.99  1031.1 2440.31    1041 2444.95
  1060.7 2457.65  1070.6 2462.94  1080.4 2466.09  1090.3 2467.45  1139.7  2468.8
#Mann= 3 , 0 , 0
       0      .1       0   583.3    .045       0   598.3      .1       0
Bank Sta=583.3,598.3
XS Rating Curve= 0 ,0
Exp/Cntr=0.3,0.1

Type RM Length L Ch R = 1 ,33002.3 ,301.3,300,300.5
XS GIS Cut Line= 3
     1980071.463      318521.773     1979891.636      319037.278
     1979699.368      319548.487
#Sta/Elev= 30
       0 2479.27     9.9 2478.06    59.6 2467.76    69.5 2464.38   109.2 2445.72
   148.9 2428.16   248.2 2390.96     278 2377.22   297.8 2367.04   317.7 2355.78
   357.4 2331.38   377.2 2320.37   506.3  2259.7   526.1 2249.09   538.5  2243.9
     546 2242.42   553.5 2243.13   605.6 2255.67   655.2 2275.14   675.1 2284.14
   724.7 2308.56   744.6 2319.39   774.4 2339.21   794.2 2348.82   883.6 2383.94
   933.2 2401.58  1012.7  2437.1  1052.4 2457.15  1062.4 2459.99  1092.1 2465.48
#Mann= 3 , 0 , 0
       0      .1       0   538.5    .045       0   553.5      .1       0
Bank Sta=538.5,553.5
XS Rating Curve= 0 ,0
Exp/Cntr=0.3,0.1

Type RM Length L Ch R = 1 ,32702.3 ,296.9,299.9,298.5
XS GIS Cut Line= 3
     1979764.477      318400.976      1979614.64      318925.407
     1979409.203      319434.849
#Sta/Elev= 30
       0 2504.84     9.9 2498.22    19.8 2493.28    29.8 2491.23    79.3 2486.29
    89.2 2484.44    99.2  2480.3   168.6 2435.38   228.1 2399.82   257.8 2383.22
   317.3 2351.94   386.8 2320.82   406.6 2310.11   515.7 2236.78   537.9 2220.96
   545.4 2216.66   552.9 2215.21   555.4 2214.73   565.4 2216.68   625.3 2242.11
   645.3 2251.85   665.3 2263.74   735.2 2309.67   745.2 2315.66     905 2396.08
  1024.8 2454.63  1034.8 2459.32  1044.8 2462.97  1064.8 2467.37  1094.7 2471.98
#Mann= 3 , 0 , 0
       0      .1       0   537.9    .045       0   552.9      .1       0
Bank Sta=537.9,552.9
XS Rating Curve= 0 ,0
Exp/Cntr=0.3,0.1

Type RM Length L Ch R = 1 ,32402.3 ,326.9,320.1,316.6
XS GIS Cut Line= 3
     1979550.746      318324.887     1979331.375      318827.613
     1979159.761      319345.945
#Sta/Elev= 30
       0 2495.14    29.9 2494.52    39.9 2493.11    69.8 2484.52    79.8 2480.47
    89.8 2475.15   169.5 2425.86   199.5 2405.67   279.2    2349     359 2286.44
     379 2271.42   398.9 2257.53   418.9 2244.56   448.8 2228.04   468.7 2218.82
   488.7 2210.98   508.6 2205.87     541 2201.23   548.5 2200.66     556 2201.82
   558.4 2202.19   568.4 2206.79   588.2 2218.38   717.3 2286.62     747 2301.11
   836.4 2342.94   856.2 2351.47   975.4  2393.4   985.3 2397.45  1094.5 2448.79
#Mann= 3 , 0 , 0
       0      .1       0     541    .045       0     556      .1       0
Bank Sta=541,556
XS Rating Curve= 0 ,0
Exp/Cntr=0.3,0.1

Type RM Length L Ch R = 1 ,32082.1 ,291.7,291.6,290.3
XS GIS Cut Line= 3
     1979103.072      318160.044     1979045.417      318697.884
     1978955.031      319257.576
#Sta/Elev= 30
       0 2443.27    50.1 2424.13    70.1 2417.38   110.2 2405.04   120.2 2401.27
   130.2 2396.71   170.3 2374.01   190.3 2361.55   260.4 2310.51   300.5 2284.27
   360.6 2250.54   440.8 2208.31   470.8 2194.65   480.8 2190.92   490.8 2188.26
   500.8 2186.74   535.1 2185.32   540.9 2184.98   550.1 2185.19   590.6 2189.04
   600.6 2191.47   610.6 2195.39     720 2251.71   759.7 2267.07   769.7 2271.45
   809.5 2294.48     889 2334.16   938.8  2356.6  1008.4  2381.8  1107.9 2423.77
#Mann= 3 , 0 , 0
       0      .1       0   535.1    .045       0   550.1      .1       0
Bank Sta=535.1,550.1
XS Rating Curve= 0 ,0
Exp/Cntr=0.3,0.1

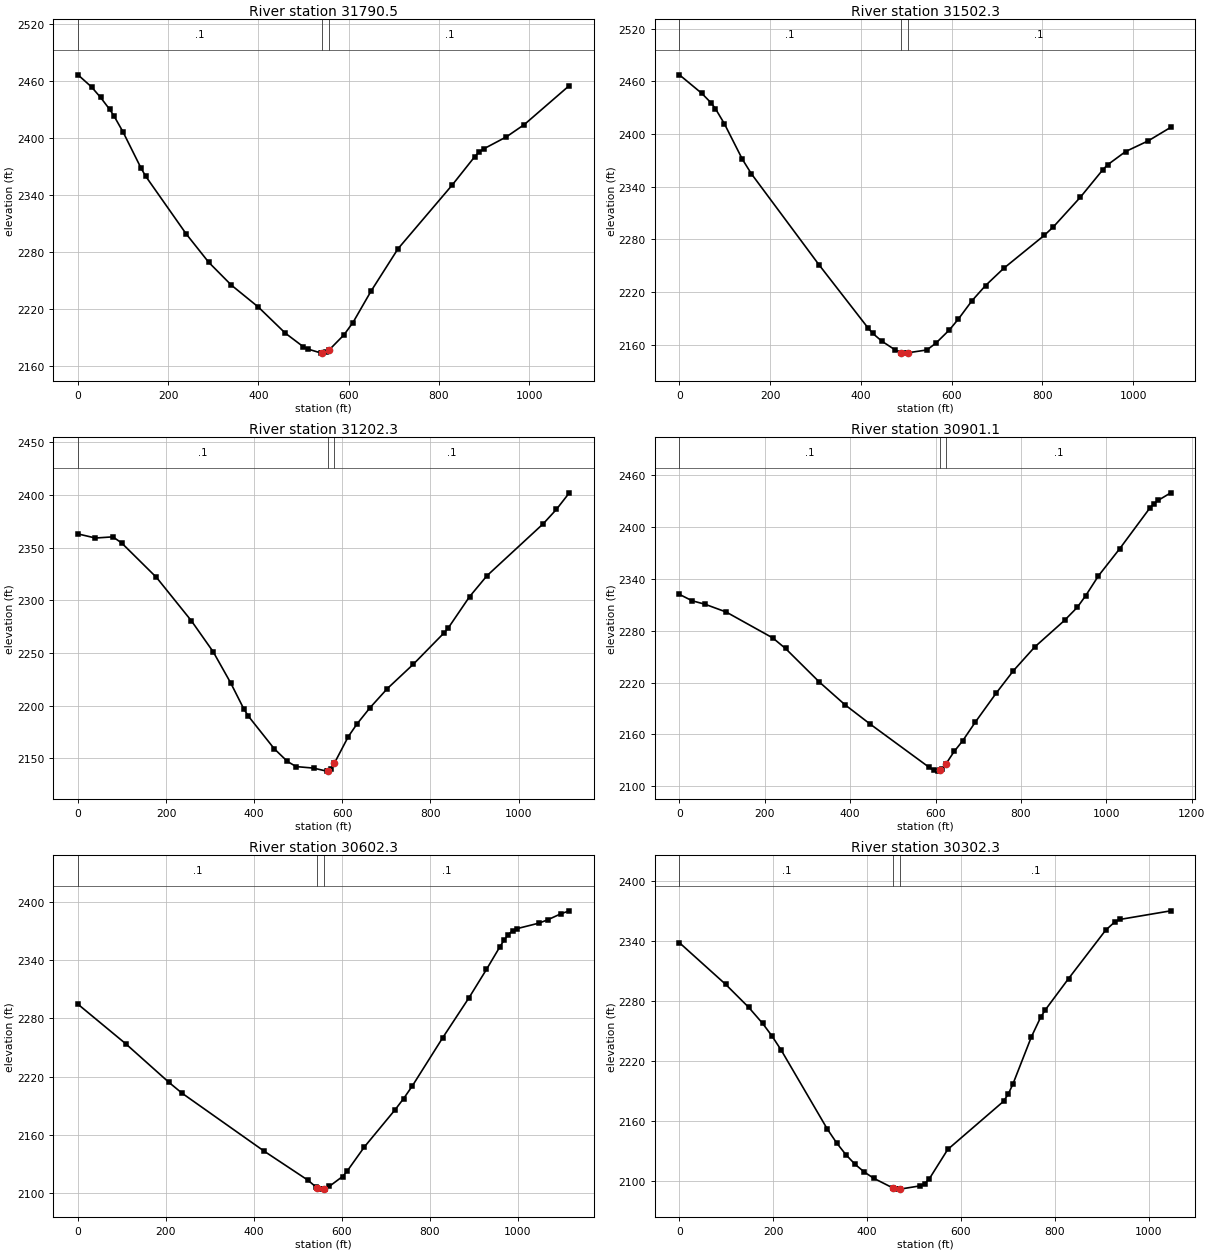
Type RM Length L Ch R = 1 ,31790.5 ,280.9,288.1,296.2
XS GIS Cut Line= 2
     1978813.793      318162.107     1978696.693      319244.599
#Sta/Elev= 30
       0 2466.66      30 2453.88      50 2442.86    69.9 2430.41    79.9 2423.21
    99.9 2406.34   139.8  2368.2   149.8 2359.86   239.7 2298.91   289.7 2268.93
   339.6 2244.97   399.6 2221.75   459.5 2194.17   499.4 2179.84   509.4 2177.44
   539.4 2173.14   541.7 2173.35   549.4 2174.07   556.7 2176.56   589.4 2192.41
   609.3 2205.39   649.3 2238.47   709.2 2283.25   829.1 2350.35     879 2380.25
     889  2385.2     899 2388.56     949 2401.15   988.9 2414.16  1088.8 2455.33
#Mann= 3 , 0 , 0
       0      .1       0   541.7    .045       0   556.7      .1       0
Bank Sta=541.7,556.7
XS Rating Curve= 0 ,0
Exp/Cntr=0.3,0.1

Type RM Length L Ch R = 1 ,31502.3 ,304.7,300,293.4
XS GIS Cut Line= 3
     1978757.641      318108.295      1978540.34      318553.817
     1978262.793      319071.351
#Sta/Elev= 30
       0 2467.53    49.6 2446.31    69.4  2435.8    79.3 2429.06    99.1 2411.85
   138.8 2371.34   158.6 2354.87   307.3 2251.46   416.4 2178.84   426.3 2173.02
   446.1 2164.25   475.9 2154.14   488.2 2151.31   495.7  2150.6   503.2 2150.95
   545.5 2154.22   565.4    2162   595.2 2177.11   615.1 2189.55     645 2210.35
   674.8  2227.6   714.7 2247.13   804.2 2284.72   824.2 2294.35   883.9 2328.24
   933.6 2359.66   943.6 2364.99   983.4 2380.14  1033.2  2392.3    1083 2407.76
#Mann= 3 , 0 , 0
       0      .1       0   488.2    .045       0   503.2      .1       0
Bank Sta=488.2,503.2
XS Rating Curve= 0 ,0
Exp/Cntr=0.3,0.1

Type RM Length L Ch R = 1 ,31202.3 ,298.2,301.2,305.3
XS GIS Cut Line= 3
     1978399.432      317954.319       1978253.5      318509.707
      1978140.14      319038.714
#Sta/Elev= 30
       0 2363.17    39.6 2359.27    79.2 2360.38      99 2354.62   178.2 2321.86
   257.4 2280.69   306.9 2251.27   346.5 2221.83   376.2  2197.2   386.1 2190.52
   445.5 2159.21   475.2 2147.24     495  2142.3   534.6 2140.85   564.3 2137.98
   566.7 2138.46   574.2 2139.94   581.7 2145.26   613.6 2170.76   633.3 2182.76
   662.8 2198.15   702.1 2216.31   761.1 2239.43     830 2268.81   839.8 2273.47
     889 2303.71   928.4  2323.5  1056.2 2372.88  1085.8 2386.38  1115.3 2402.18
#Mann= 3 , 0 , 0
       0      .1       0   566.7    .045       0   581.7      .1       0
Bank Sta=566.7,581.7
XS Rating Curve= 0 ,0
Exp/Cntr=0.3,0.1

Type RM Length L Ch R = 1 ,30901.1 ,286,298.7,311.8
XS GIS Cut Line= 4
     1978319.122       317924.93     1977992.579      318363.316
     1977944.324      318480.005     1977761.471      318921.676
#Sta/Elev= 30
       0 2321.99    29.8 2314.57    59.6 2310.63   109.3 2301.64   218.7 2271.61
   248.5 2259.42     328 2220.52   387.6 2194.45   447.2 2171.86   585.5 2121.82
   595.2 2118.61   604.9 2117.62   609.6 2118.69   614.6 2119.82   624.6  2126.2
   643.8  2140.5   663.2 2152.47   692.8 2174.06   742.6 2208.21   782.5  2233.8
   832.2 2261.12     902 2291.88   931.8 2306.91   951.8 2320.58   981.6 2343.46
  1031.4 2374.82  1101.1 2421.27  1111.1 2426.74  1121.1  2430.6  1150.9 2439.38
#Mann= 3 , 0 , 0
       0      .1       0   609.6    .045       0   624.6      .1       0
Bank Sta=609.6,624.6
XS Rating Curve= 0 ,0
Exp/Cntr=0.3,0.1

Type RM Length L Ch R = 1 ,30602.3 ,308.7,300,292
XS GIS Cut Line= 3
      1978265.26      317861.995     1977815.847      318182.074
     1977348.354      318499.228
#Sta/Elev= 30
       0 2294.57   108.4 2253.98   206.9 2214.16   236.5 2203.08   423.7 2143.27
   522.2 2113.72   541.9 2106.23   544.2  2105.8   551.7 2104.41   559.2 2104.78
   561.7 2104.91   571.6  2107.4   601.3 2117.39   611.2  2122.6   650.8 2147.78
   720.2 2185.78     740  2197.5   759.9 2210.58   829.2 2260.34   888.7 2301.29
   928.4 2330.43   958.1  2353.1     968 2360.29   977.9 2366.23   987.8 2370.28
   997.7 2372.34  1047.3 2377.98  1067.1 2381.33  1096.8  2387.5  1116.7 2390.67
#Mann= 3 , 0 , 0
       0      .1       0   544.2    .045       0   559.2      .1       0
Bank Sta=544.2,559.2
XS Rating Curve= 0 ,0
Exp/Cntr=0.3,0.1

Type RM Length L Ch R = 1 ,30302.3 ,271.4,263.4,255.1
XS GIS Cut Line= 3
     1977877.644      317571.055     1977628.897      317961.412
     1977290.218      318437.097
#Sta/Elev= 30
       0 2338.32    98.5 2296.71   147.7  2273.7   177.3 2257.68     197 2245.26
   216.7 2231.11   315.2 2152.07   334.8  2138.4   354.5 2126.64   374.2 2116.92
   393.9 2109.22   413.6 2103.06   455.4 2093.14   462.9 2092.12   470.4 2092.16
   512.4 2095.35   522.3 2097.43   532.2 2102.28   571.7 2131.79   690.5 2179.83
   700.4 2186.98   710.3 2196.83   749.9 2244.29   769.7 2263.92   779.6 2271.26
   829.1 2302.49   908.2 2350.89     928 2359.25   937.9 2361.52  1046.8 2370.17
#Mann= 3 , 0 , 0
       0      .1       0   455.4    .045       0   470.4      .1       0
Bank Sta=455.4,470.4
XS Rating Curve= 0 ,0
Exp/Cntr=0.3,0.1

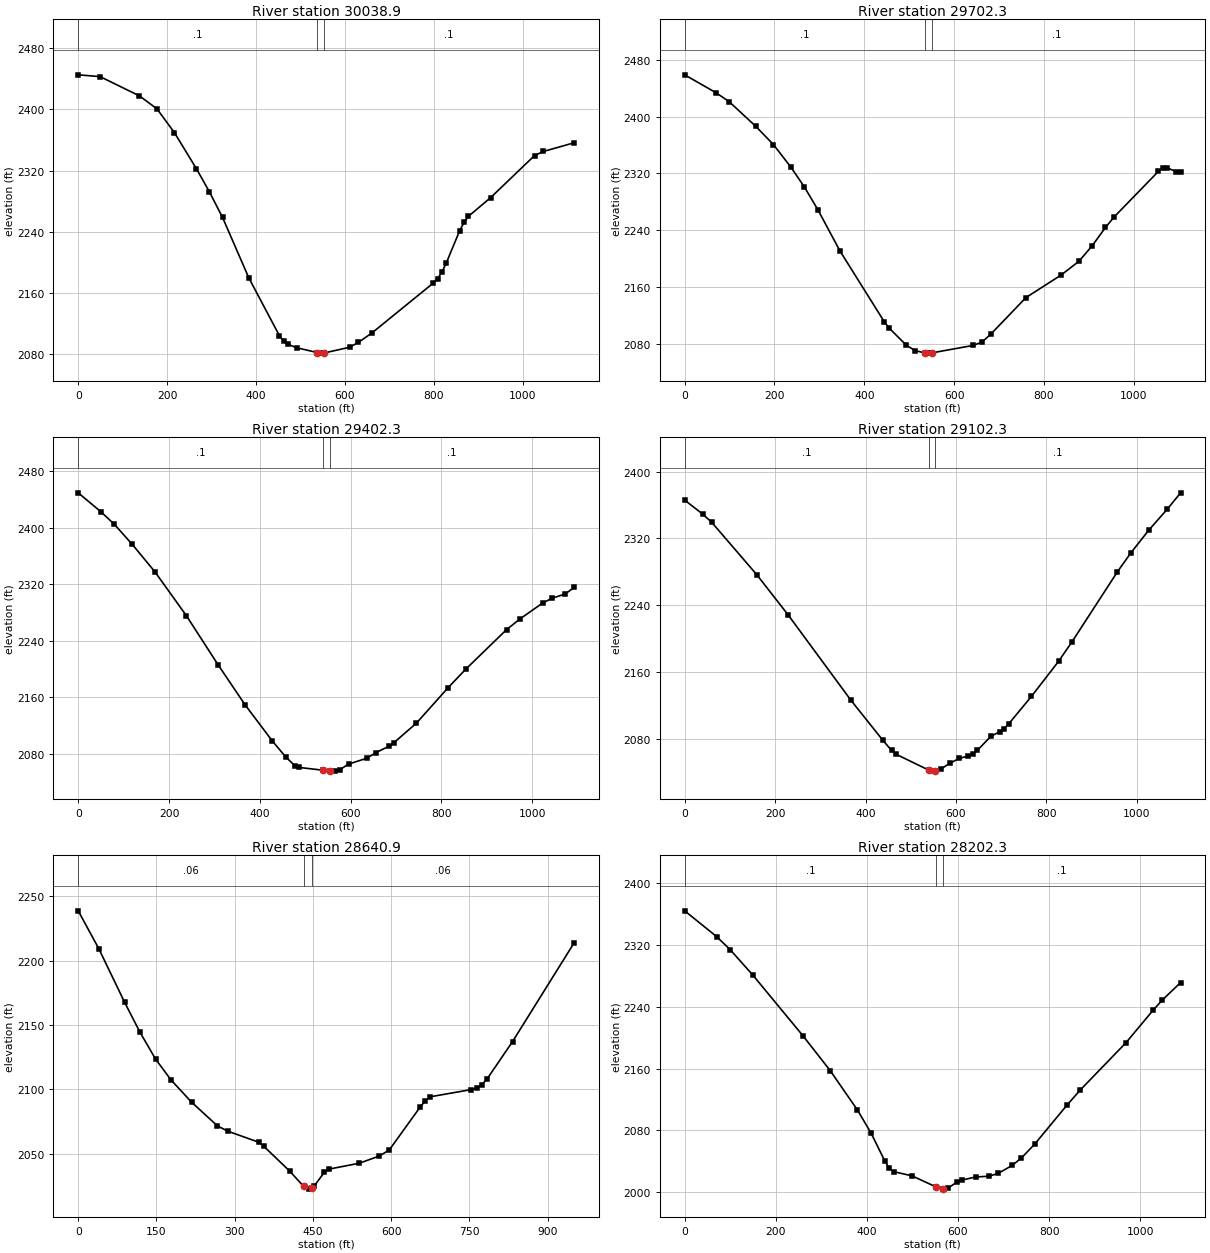
Type RM Length L Ch R = 1 ,30038.9 ,346.3,336.5,328.2
XS GIS Cut Line= 3
       1977504.1      317320.839     1977392.645      317850.254
     1977247.566      318405.848
#Sta/Elev= 30
       0 2445.27    49.2 2442.92   137.7 2417.72   177.1 2400.74   216.4 2369.55
   265.6 2322.61   295.1 2292.11   324.6  2258.6   383.6 2179.62   452.5 2103.87
   462.3 2096.45   472.2 2092.42   491.8 2088.06   537.7 2081.82   550.9  2081.1
   552.7 2081.23   610.3 2088.81   630.1 2095.18   659.8 2107.18   798.4 2172.77
   808.3 2178.68   818.2 2187.49   828.1 2199.67   857.8 2241.38   867.7 2252.12
   877.6 2260.21   927.1 2284.42  1026.1 2339.62  1045.9 2344.98  1115.2 2356.34
#Mann= 3 , 0 , 0
       0      .1       0   537.7    .045       0   552.7      .1       0
Bank Sta=537.7,552.7
XS Rating Curve= 0 ,0
Exp/Cntr=0.3,0.1

Type RM Length L Ch R = 1 ,29702.3 ,301.5,300,296.4
XS GIS Cut Line= 3
     1976942.593      317310.262     1977058.739      317841.045
     1977123.164      318398.459
#Sta/Elev= 30
       0 2458.72    69.2 2433.76    98.8 2421.12   158.1 2386.42   197.6  2360.7
   237.1  2328.4   266.7 2300.87   296.4 2269.23   345.8 2211.05   444.6 2111.36
   454.4 2103.15     494 2078.22   513.7 2070.77   535.8 2067.51   543.3 2067.32
   550.8 2067.71   641.8 2078.08   661.5 2082.64   681.2 2093.61   759.9 2145.36
   838.7 2177.29     878 2196.47   907.6 2218.32   937.1 2244.05   956.8 2259.08
  1055.2 2323.04  1065.1 2327.29  1074.9 2327.84  1094.6 2322.51  1104.5 2321.62
#Mann= 3 , 0 , 0
       0      .1       0   535.8    .045       0   550.8      .1       0
Bank Sta=535.8,550.8
XS Rating Curve= 0 ,0
Exp/Cntr=0.3,0.1

Type RM Length L Ch R = 1 ,29402.3 ,302.6,300,299
XS GIS Cut Line= 3
     1976622.859      317409.155     1976775.729      317933.518
     1976923.477      318459.189
#Sta/Elev= 30
       0 2449.69    49.6 2423.06    79.4 2405.23   119.2 2376.56   168.8 2337.96
   238.3  2275.6   307.8 2206.38   367.4 2149.53     427 2098.67   456.8 2075.79
   476.7 2063.46   486.6 2060.78   538.7 2056.89   553.7 2055.77     566 2055.56
     576 2057.54   595.8 2065.65   635.5 2073.73   655.4 2081.74   685.2 2091.09
   695.1 2095.74   744.8 2123.52   814.2 2173.43     854 2200.27   943.3 2255.95
   973.1 2271.17  1022.7 2293.58  1042.6 2300.14  1072.4 2306.45  1092.2 2315.63
#Mann= 3 , 0 , 0
       0      .1       0   538.7    .045       0   553.7      .1       0
Bank Sta=538.7,553.7
XS Rating Curve= 0 ,0
Exp/Cntr=0.3,0.1

Type RM Length L Ch R = 1 ,29102.3 ,453.1,461.3,467.7
XS GIS Cut Line= 3
     1976273.707      317497.976     1976485.846      318002.272
     1976656.958      318524.795
#Sta/Elev= 30
       0 2365.82    39.8 2349.09    59.7  2339.3   159.2 2276.65   228.8 2228.35
     368 2125.85   437.7 2078.55   457.6 2065.94   467.5  2061.4   539.6 2042.44
   547.1 2041.17   554.6  2041.4   567.1 2043.85   587.1 2050.74   607.1 2056.38
   627.1 2059.27   637.1 2061.63   647.1 2065.92   677.1 2082.82     697 2088.43
     707 2092.22     717    2098     767 2130.72     827 2172.73     857 2196.37
     957 2279.85     987 2302.76    1027 2330.17  1066.9 2354.67  1096.9 2374.56
#Mann= 3 , 0 , 0
       0      .1       0   539.6    .045       0   554.6      .1       0
Bank Sta=539.6,554.6
XS Rating Curve= 0 ,0
Exp/Cntr=0.3,0.1

Type RM Length L Ch R = 1 ,28640.9 ,422.6,438.4,456.4
XS GIS Cut Line= 4
     1976103.125      317686.837     1976050.041      318088.506
     1976055.349      318279.609     1976242.913      318580.419
#Sta/Elev= 30
       0 2238.75    39.5  2209.3    88.9  2167.7   118.6 2144.26   148.2  2123.6
   177.9 2107.35   217.4 2090.03   266.8 2071.66   286.6 2067.54   345.9 2058.96
   355.8 2055.79   405.2 2036.57   432.3 2024.56   443.4 2022.48   447.3  2023.6
     453 2025.23   472.1 2035.67   481.6 2038.09     539 2042.62   577.2  2048.2
   596.3 2052.87   655.4 2086.15   665.3 2091.09   675.1 2094.25   753.9 2099.87
   763.7 2100.89   773.6 2103.63   783.4 2107.81   832.7 2137.16   950.8 2213.91
#Mann= 3 , 0 , 0
       0     .06       0   432.3    .045       0   447.3     .06       0
Bank Sta=432.3,447.3
XS Rating Curve= 0 ,0
Exp/Cntr=0.3,0.1

Type RM Length L Ch R = 1 ,28202.3 ,304.1,300,294.9
XS GIS Cut Line= 3
     1976035.221      317466.857     1975687.673       317904.52
     1975322.756       318288.74
#Sta/Elev= 30
       0 2364.36    69.9  2331.1    99.8 2314.14   149.7 2281.12   259.5  2202.7
   319.4 2157.56   379.2 2106.54   409.2 2076.59   439.1 2040.81   449.1 2031.04
   459.1 2026.62     499 2021.26   551.4 2007.02   566.4  2004.3   568.9 2004.05
   578.9 2005.65   598.9 2013.71   608.9 2015.78   638.9 2019.78   668.8 2020.78
   688.8  2024.6   718.8 2034.69   738.8 2044.11   768.8 2062.58   838.8 2112.46
   868.8  2132.6   968.8 2193.59  1028.8 2235.98  1048.8 2248.94  1088.8 2271.52
#Mann= 3 , 0 , 0
       0      .1       0   551.4    .045       0   566.4      .1       0
Bank Sta=551.4,566.4
XS Rating Curve= 0 ,0
Exp/Cntr=0.3,0.1