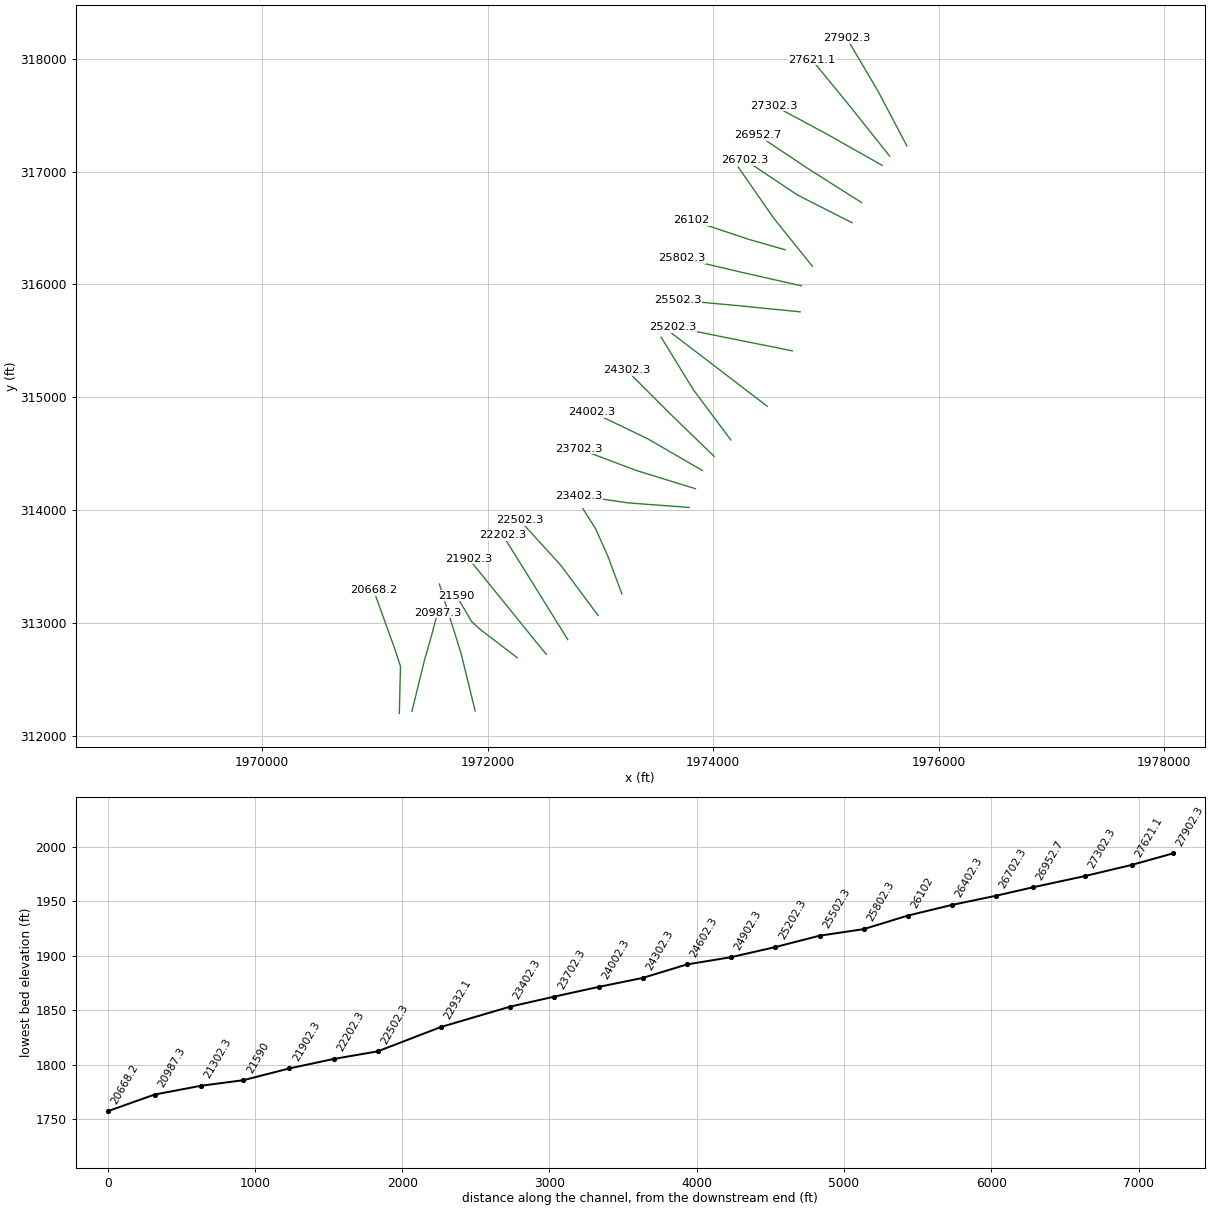
HEC-RAS study LaurelCrk.prj: LaurelCrk

--- LaurelCrk.g01 (geometry) --- (continued)

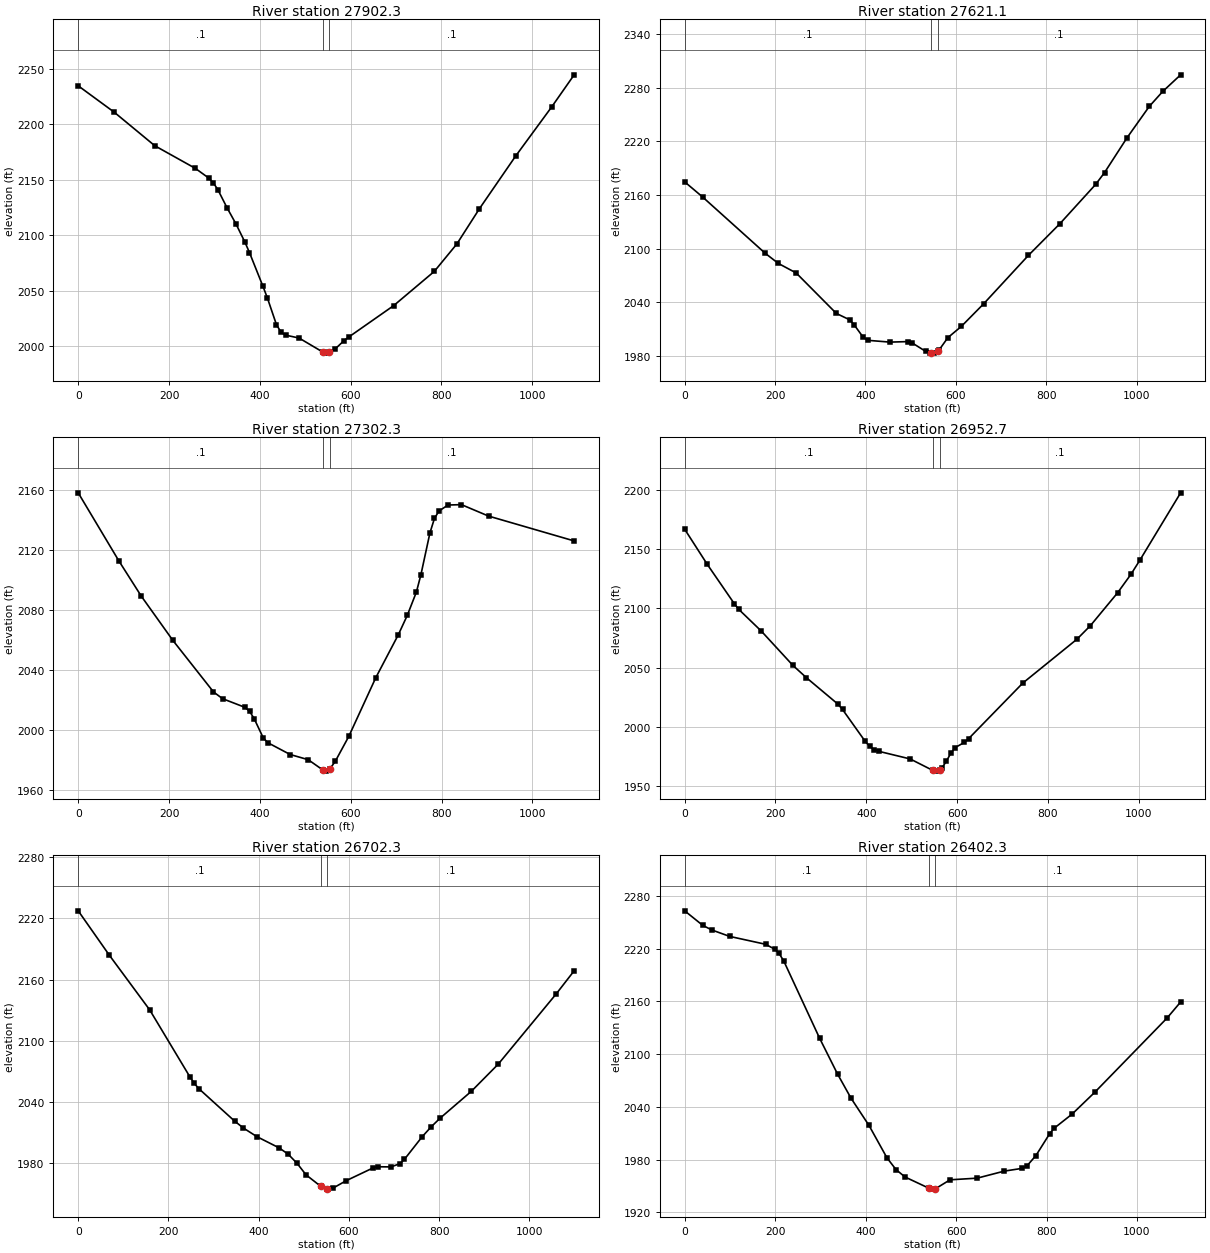
Type RM Length L Ch R = 1 ,27902.3 ,277,281.2,284.7
XS GIS Cut Line= 3
     1975718.711      317228.192     1975464.095      317711.084
     1975186.161      318181.667
#Sta/Elev= 30
       0 2234.57    79.4 2210.76   168.7 2180.56   258.1 2160.16   287.8 2151.37
   297.8 2147.04   307.7  2140.9   327.5 2124.92   347.4  2110.2   367.2 2093.73
   377.2 2084.34     407 2053.82   416.9 2043.18   436.7  2019.3   446.6  2012.7
   456.6 2009.94   486.4 2007.33   538.4 1994.77   545.9 1993.72   553.4 1994.31
   565.8 1997.42   585.6    2005   595.6 2008.13     695 2036.56   784.4 2067.37
   834.1 2092.11   883.8 2123.86   963.3 2171.14  1042.8 2215.48  1092.4 2244.46
#Mann= 3 , 0 , 0
       0      .1       0   538.4    .045       0   553.4      .1       0
Bank Sta=538.4,553.4
XS Rating Curve= 0 ,0
Exp/Cntr=0.3,0.1

Type RM Length L Ch R = 1 ,27621.1 ,310.1,318.8,327.6
XS GIS Cut Line= 3
     1975565.055      317138.401     1975220.981      317571.055
     1974875.743      317992.519
#Sta/Elev= 30
       0 2174.66    39.5 2157.82   177.7 2095.01   207.3 2083.43   246.8 2072.76
   335.6 2027.54   365.2 2020.37   375.1 2014.74   394.8 2001.08   404.7 1997.47
   454.1 1995.44   493.6 1996.01   503.4 1994.55     533  1985.2   542.9 1983.12
   545.1 1983.14   552.8  1983.2   560.1 1985.56   562.7  1986.4   582.5 2000.44
   612.2 2012.96   661.8 2038.34   760.8 2092.47   830.2 2127.74   909.4 2171.72
   929.2 2185.01   978.7 2223.74  1028.3 2259.07    1058 2275.75  1097.6 2294.36
#Mann= 3 , 0 , 0
       0      .1       0   545.1    .045       0   560.1      .1       0
Bank Sta=545.1,560.1
XS Rating Curve= 0 ,0
Exp/Cntr=0.3,0.1

Type RM Length L Ch R = 1 ,27302.3 ,350.9,349.6,347.5
XS GIS Cut Line= 3
     1975498.094      317056.443      1975022.67      317325.222
     1974541.954      317584.068
#Sta/Elev= 30
       0 2158.07    89.4 2112.83     139 2089.26   208.5 2059.84   297.9 2025.57
   317.8 2021.09   367.4 2015.29   377.3 2012.68   387.3 2007.89   407.1 1995.24
     417 1991.87   466.7 1983.93   506.4 1980.49   538.6 1973.67   546.1 1972.87
   553.6 1974.12     566 1979.36   595.8 1995.96   655.3 2035.06     705 2063.68
   724.8 2076.64   744.7 2092.05   754.6 2103.52   774.5 2131.38   784.4 2140.99
   794.3 2145.91   814.2 2149.96     844  2150.2   903.5 2142.61  1092.1 2126.06
#Mann= 3 , 0 , 0
       0      .1       0   538.6    .045       0   553.6      .1       0
Bank Sta=538.6,553.6
XS Rating Curve= 0 ,0
Exp/Cntr=0.3,0.1

Type RM Length L Ch R = 1 ,26952.7 ,248.1,250.4,250.3
XS GIS Cut Line= 3
     1975316.698      316726.318     1974855.012      317018.166
     1974400.742      317321.014
#Sta/Elev= 30
       0 2166.73    49.6 2137.17   109.2 2103.96   119.2 2099.09   168.8 2080.78
   238.3 2051.87   268.1 2041.48   337.6 2019.15   347.6 2014.68   397.2 1987.97
   407.2 1983.67   417.1 1980.89     427 1979.42   496.5 1972.96   546.5 1963.27
   556.1 1962.67   561.5 1963.96     566 1965.04     576 1970.85   585.9  1977.6
   595.8 1982.57   615.7 1986.83   625.6 1990.16   744.7 2036.97   863.8 2073.92
   893.6 2085.42   953.2 2113.01     983  2128.8  1002.8 2140.82  1092.2 2197.43
#Mann= 3 , 0 , 0
       0      .1       0   546.5    .045       0   561.5      .1       0
Bank Sta=546.5,561.5
XS Rating Curve= 0 ,0
Exp/Cntr=0.3,0.1

Type RM Length L Ch R = 1 ,26702.3 ,309.5,300,291.5
XS GIS Cut Line= 3
     1975232.186      316547.168     1974746.854      316793.947
     1974285.468      317101.818
#Sta/Elev= 30
       0 2227.44    69.3 2183.78   158.4 2130.45   247.5 2064.86   257.4 2058.36
   267.3 2053.29   346.5 2021.56   366.3 2014.67     396 2006.29   445.5 1995.24
   465.3 1989.12   485.1 1980.15   504.9 1968.89     537 1957.83     552 1955.13
   554.4  1954.9   564.3 1955.79     594 1963.19   653.4 1975.67   663.3  1976.8
     693 1976.67   712.8 1979.77   722.8    1984   762.4 2006.27   782.2  2015.9
     802 2024.38   871.3 2050.72   930.8 2077.27  1059.5 2146.18  1099.1 2168.71
#Mann= 3 , 0 , 0
       0      .1       0     537    .045       0     552      .1       0
Bank Sta=537,552
XS Rating Curve= 0 ,0
Exp/Cntr=0.3,0.1

Type RM Length L Ch R = 1 ,26402.3 ,286.4,300.3,314.9
XS GIS Cut Line= 3
     1974880.017      316162.207     1974537.233       316588.05
     1974223.588      317039.583
#Sta/Elev= 30
       0 2263.16    39.8 2246.68    59.6 2241.45    99.4 2234.06   178.9 2225.09
   198.8 2219.57   208.7  2214.6   218.7 2206.46   298.2 2118.28   337.9 2077.47
   367.8 2049.89   407.5 2018.92   447.3 1981.98   467.2 1968.72     487 1960.31
   539.2 1947.68   546.7 1946.46   554.2 1946.84   586.6 1957.06   646.6 1958.95
   706.6 1966.97   746.6 1970.13   756.6 1972.87   776.6 1984.72   806.6 2009.26
   816.6 2015.66   856.5 2031.85   906.5 2056.62  1066.5 2141.21  1096.4 2159.39
#Mann= 3 , 0 , 0
       0      .1       0   539.2    .045       0   554.2      .1       0
Bank Sta=539.2,554.2
XS Rating Curve= 0 ,0
Exp/Cntr=0.3,0.1

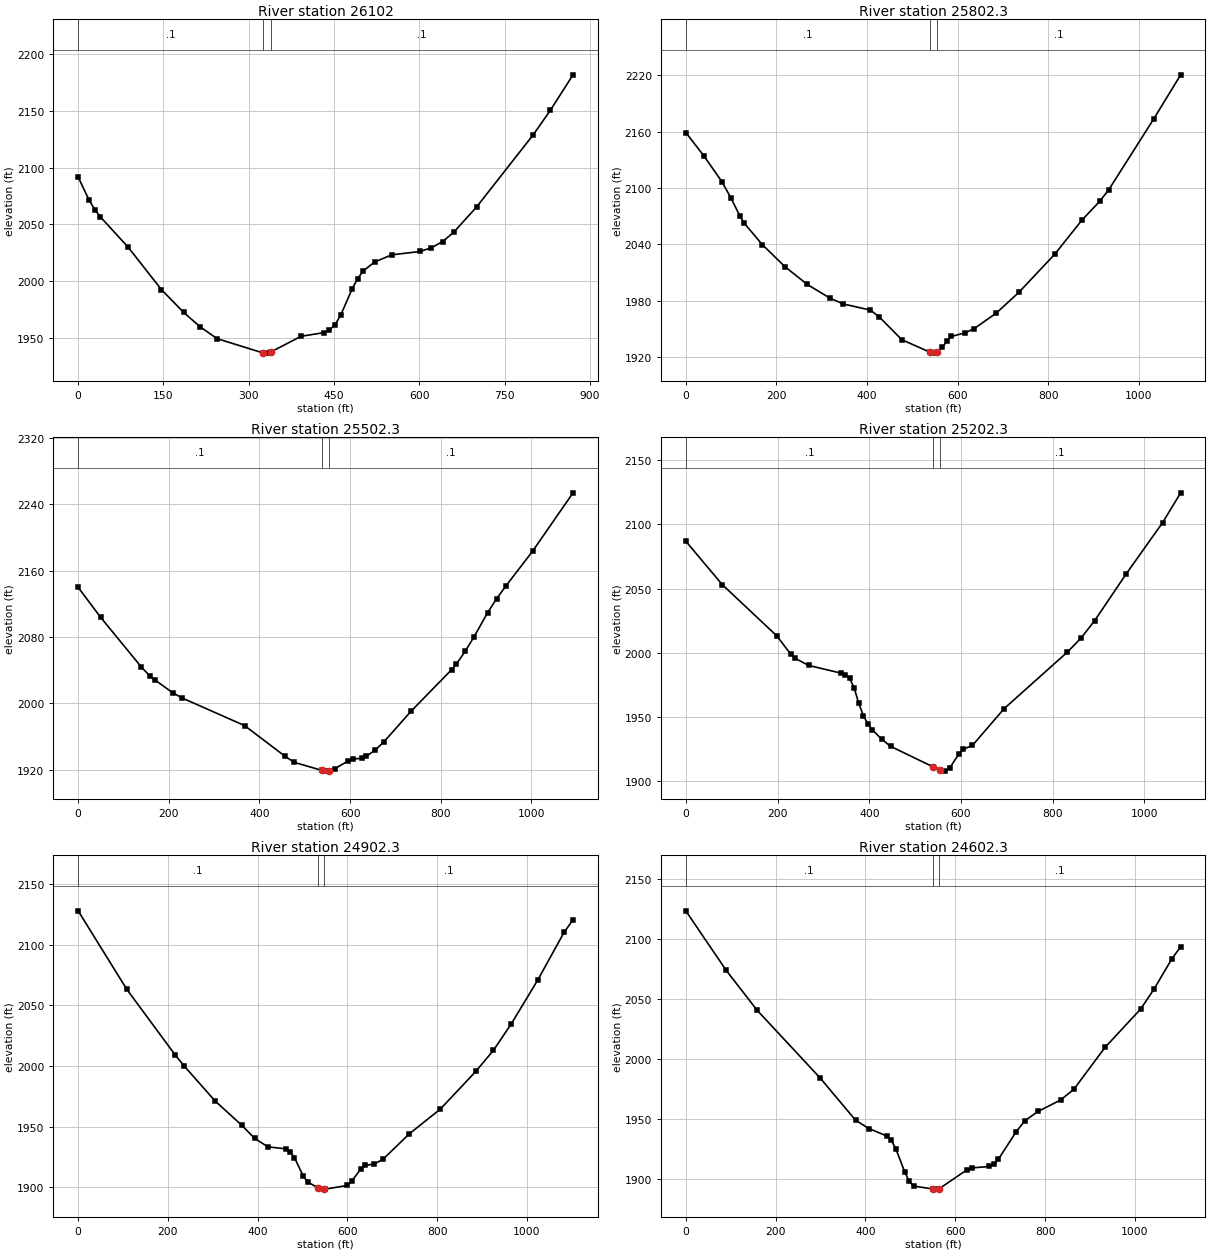
Type RM Length L Ch R = 1 ,26102   ,298.3,299.6,301.7
XS GIS Cut Line= 3
     1974638.411      316307.649      1974319.05      316398.895
     1973808.423      316569.104
#Sta/Elev= 30
       0 2091.65    19.5 2071.14    29.3 2063.05    39.1 2056.61    87.9 2029.94
   146.5 1992.58   185.6 1972.48   214.9 1959.75   244.2 1949.44   324.9 1936.89
   332.1 1936.67   339.9 1937.96     392 1951.49   431.8 1954.66   441.8 1956.93
   451.8 1961.67   461.7 1970.09   481.6 1992.83   491.6 2002.33   501.6 2009.11
   521.5 2016.91   551.4 2023.18   601.3 2026.15   621.2 2029.39   641.1 2034.89
   661.1 2043.36   700.9 2065.43   800.6 2129.02   830.5 2150.45   870.4 2181.67
#Mann= 3 , 0 , 0
       0      .1       0   324.9    .045       0   339.9      .1       0
Bank Sta=324.9,339.9
XS Rating Curve= 0 ,0
Exp/Cntr=0.3,0.1

Type RM Length L Ch R = 1 ,25802.3 ,297.1,299.9,303.1
XS GIS Cut Line= 3
     1974783.566      315987.737     1974250.683      316108.396
     1973719.113      316232.805
#Sta/Elev= 30
       0 2158.95    39.7 2134.22    79.5 2106.78    99.3 2089.62   119.2 2070.32
   129.1 2062.37   168.9 2039.68   218.6 2016.29   268.2 1997.29   317.9 1982.79
   347.7 1976.52   407.3 1970.06   427.2 1962.65   476.8 1938.53   538.9 1925.22
   546.4 1924.23   553.9 1925.01   566.2 1930.31   576.2 1937.03   586.1 1941.94
   615.8 1945.78   635.7 1950.02   685.3 1966.84     735 1988.81   814.4 2029.48
   873.9 2065.48   913.6 2085.77   933.5    2098  1032.8 2173.39  1092.3 2220.32
#Mann= 3 , 0 , 0
       0      .1       0   538.9    .045       0   553.9      .1       0
Bank Sta=538.9,553.9
XS Rating Curve= 0 ,0
Exp/Cntr=0.3,0.1

Type RM Length L Ch R = 1 ,25502.3 ,302.2,300,297.6
XS GIS Cut Line= 3
     1974772.456      315757.118      1974229.17      315811.447
     1973685.443      315861.453
#Sta/Elev= 30
       0 2139.74    49.6 2103.62     139 2044.03   158.8 2032.56   168.8 2028.29
   208.5 2012.78   228.3 2006.64   367.3 1973.07   456.6 1936.09   476.5 1928.85
   538.5 1918.97     546  1918.2   553.5 1918.53   565.8 1920.95   595.6 1930.44
   605.6 1932.56   625.4 1933.79   635.4 1936.04   655.2 1943.36   675.1 1953.77
   734.6 1990.42     824 2040.48   833.9 2046.82   853.8 2062.47   873.6 2080.15
   903.4 2109.17   923.2 2125.98   943.1 2140.91  1002.7 2183.33    1092 2253.73
#Mann= 3 , 0 , 0
       0      .1       0   538.5    .045       0   553.5      .1       0
Bank Sta=538.5,553.5
XS Rating Curve= 0 ,0
Exp/Cntr=0.3,0.1

Type RM Length L Ch R = 1 ,25202.3 ,310.3,300,289.7
XS GIS Cut Line= 3
     1974703.137      315411.657     1974167.788      315518.625
     1973645.233      315623.304
#Sta/Elev= 30
       0 2086.86    79.4 2053.09   198.5 2013.07   228.3 1999.09   238.2 1995.66
     268 1990.09   337.5 1984.18   347.4 1982.92   357.3 1980.06   367.3 1972.21
   377.2 1960.47   387.1 1951.07     397 1944.58     407 1939.84   426.8  1932.7
   446.7 1927.03   538.4 1911.22   553.4 1908.44   565.7 1907.78   575.5 1910.26
   595.3 1921.18   605.2 1924.89   624.9 1927.78     694 1956.44   832.1 2000.56
   861.8 2011.46   891.4    2025   960.4 2061.53  1039.4 2101.29  1078.9 2124.54
#Mann= 3 , 0 , 0
       0      .1       0   538.4    .045       0   553.4      .1       0
Bank Sta=538.4,553.4
XS Rating Curve= 0 ,0
Exp/Cntr=0.3,0.1

Type RM Length L Ch R = 1 ,24902.3 ,306.5,299.9,291.4
XS GIS Cut Line= 3
     1974480.485      314919.657     1974050.873      315248.471
     1973604.285      315589.275
#Sta/Elev= 30
       0 2128.09   108.2 2063.42   216.4 2009.09   236.1 2000.17   304.9 1971.32
     364 1951.41   393.5 1940.28     423 1933.38   462.3 1931.78   472.2 1929.44
     482 1924.53   501.7 1909.21   511.5 1904.47   533.5 1899.69   548.5 1898.56
   550.9 1898.51   600.1 1901.59     610 1905.24   629.7 1915.07   639.6 1918.03
   659.3 1919.19     679 1923.03   738.1 1944.17   807.1 1964.55     886 1995.56
   925.4 2013.01   964.8 2034.61  1023.9 2070.82  1083.1 2110.52  1102.8 2120.75
#Mann= 3 , 0 , 0
       0      .1       0   533.5    .045       0   548.5      .1       0
Bank Sta=533.5,548.5
XS Rating Curve= 0 ,0
Exp/Cntr=0.3,0.1

Type RM Length L Ch R = 1 ,24602.3 ,296,299.8,305.1
XS GIS Cut Line= 3
     1974157.565       314620.92     1973824.466      315067.571
     1973539.563      315531.708
#Sta/Elev= 30
       0 2123.71    89.6 2074.28   159.2 2040.69   298.5 1984.71   378.1 1949.21
   407.9 1942.28   447.7 1936.09   457.7 1932.43   467.6 1925.47   487.5 1906.16
   497.5 1898.28   507.4 1894.37   549.7 1892.03   557.2 1891.85   564.7 1892.34
   626.5 1908.08   636.4  1909.5     676 1910.72   685.9 1912.65   695.8 1916.64
   735.4 1939.58   755.2 1948.97   784.9 1956.71   834.4  1966.1   864.1 1975.06
   933.4 2009.94  1012.7 2041.87  1042.4 2058.49    1082 2083.59  1101.8 2093.79
#Mann= 3 , 0 , 0
       0      .1       0   549.7    .045       0   564.7      .1       0
Bank Sta=549.7,564.7
XS Rating Curve= 0 ,0
Exp/Cntr=0.3,0.1

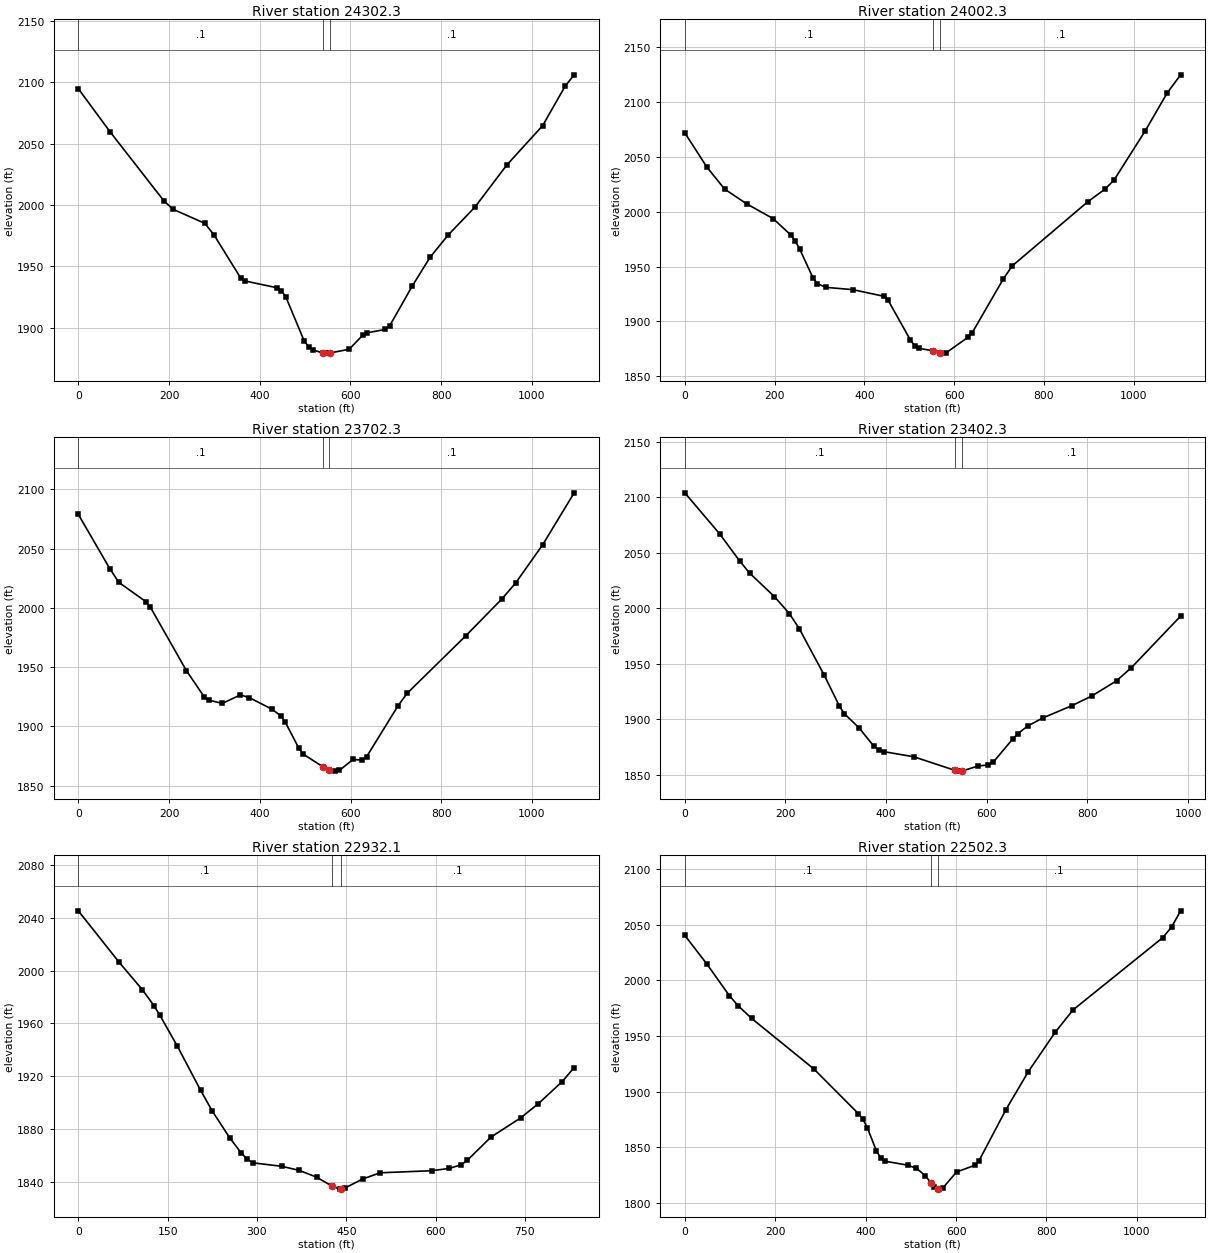
Type RM Length L Ch R = 1 ,24302.3 ,294.5,300,307.6
XS GIS Cut Line= 3
     1974010.558      314474.867     1973617.082      314855.376
     1973231.171      315241.284
#Sta/Elev= 30
       0 2094.59    69.7 2059.65   189.1 2003.13     209 1996.48   278.7 1985.08
   298.6 1975.93   358.3 1940.37   368.2 1938.12   437.9 1932.68   447.8 1930.43
   457.8 1924.92   497.6 1889.65   507.6 1884.71   517.5 1882.02   539.9 1879.54
   547.4 1879.49   554.9 1879.67     597 1882.58   626.8 1893.99   636.7 1896.01
   676.4 1898.75   686.3 1901.62   735.9 1933.89   775.6 1957.53   815.3 1975.51
   874.8 1998.49   944.3  2032.4  1023.7 2064.57  1073.3  2096.7  1093.1 2105.87
#Mann= 3 , 0 , 0
       0      .1       0   539.9    .045       0   554.9      .1       0
Bank Sta=539.9,554.9
XS Rating Curve= 0 ,0
Exp/Cntr=0.3,0.1

Type RM Length L Ch R = 1 ,24002.3 ,294.9,300,302
XS GIS Cut Line= 3
     1973903.222      314351.693     1973417.496      314633.484
     1972927.738      314868.567
#Sta/Elev= 30
       0 2071.75    49.3 2040.44    88.7 2020.51   137.9 2007.06     197  1993.6
   236.4 1978.64   246.3 1973.19   256.1 1965.86   285.7 1939.67   295.6 1934.34
   315.2 1931.05   374.4 1928.98   443.3 1922.98   453.2 1919.22   502.4 1883.34
   512.3 1877.83   522.1 1875.52     554 1873.31     569 1871.65   581.3 1871.21
   630.7 1885.56   640.6 1889.92   709.7  1938.7   729.5 1950.58   897.4  2008.8
   936.9  2020.7   956.6 2028.83  1025.8 2073.42  1075.2 2108.21  1104.8 2124.51
#Mann= 3 , 0 , 0
       0      .1       0     554    .045       0     569      .1       0
Bank Sta=554,569
XS Rating Curve= 0 ,0
Exp/Cntr=0.3,0.1

Type RM Length L Ch R = 1 ,23702.3 ,294.8,299.9,304.7
XS GIS Cut Line= 3
     1973843.732      314189.297     1973322.088      314349.802
     1972809.911      314542.578
#Sta/Elev= 30
       0 2078.88    69.5 2033.09    89.3 2021.56   148.8 2005.34   158.8 2000.65
   238.2 1947.14   277.8 1924.83   287.8  1922.2   317.5 1919.47   357.2 1926.66
   377.1  1924.3   426.7  1914.6   446.6 1908.94   456.5  1903.4   486.2  1881.6
   496.2 1876.56   538.3  1866.2   553.3  1863.6   565.7 1862.33   575.6 1863.01
   605.5 1872.15   625.4 1871.67   635.3 1874.36     705 1917.61   724.9 1928.02
   854.2 1976.53   933.8 2007.64   963.7  2020.9  1023.4 2053.19    1093 2097.12
#Mann= 3 , 0 , 0
       0      .1       0   538.3    .045       0   553.3      .1       0
Bank Sta=538.3,553.3
XS Rating Curve= 0 ,0
Exp/Cntr=0.3,0.1

Type RM Length L Ch R = 1 ,23402.3 ,494.8,470.2,447.4
XS GIS Cut Line= 3
     1973787.222      314023.409     1973244.576      314063.939
     1972808.226      314128.273
#Sta/Elev= 30
       0  2103.9    69.3  2066.9   108.8 2042.62   128.6 2031.65   178.1 2010.38
   207.8 1995.06   227.6  1981.4     277 1939.62   306.7 1912.24   316.6 1905.03
   346.3 1892.12     376 1875.36   385.9 1872.18   395.8 1870.66   455.1 1866.04
   536.7 1853.83   544.2 1853.13   551.7 1853.31   583.4 1857.86     603 1858.62
   612.8 1861.14     652 1882.32   661.8 1886.92   681.4 1893.79   710.8 1900.95
   769.6  1912.2   808.8 1920.87   857.8 1934.51   887.2 1946.28   985.2 1992.84
#Mann= 3 , 0 , 0
       0      .1       0   536.7    .045       0   551.7      .1       0
Bank Sta=536.7,551.7
XS Rating Curve= 0 ,0
Exp/Cntr=0.3,0.1

Type RM Length L Ch R = 1 ,22932.1 ,424.9,429.8,436.9
XS GIS Cut Line= 4
     1973190.758      313257.926     1973064.417      313596.589
     1972957.379      313835.233     1972845.076      314012.461
#Sta/Elev= 30
       0 2045.32    68.4 2006.41   107.5 1985.58     127 1973.49   136.8 1966.33
   166.1 1942.98   205.2 1909.51   224.7 1893.82     254 1873.49   273.5  1861.9
   283.3  1857.3   293.1 1854.39   341.9 1851.74   371.2 1848.62   400.2 1843.51
   425.8 1836.82     439 1834.46   440.8 1834.65   448.6 1835.48   477.7 1842.16
   506.8 1846.83     594 1848.42     623 1850.16     643 1852.92     653 1856.17
     693 1873.86   742.9 1888.42   772.9 1899.32   812.8 1915.98   832.8 1926.58
#Mann= 3 , 0 , 0
       0      .1       0   425.8    .045       0   440.8      .1       0
Bank Sta=425.8,440.8
XS Rating Curve= 0 ,0
Exp/Cntr=0.3,0.1

Type RM Length L Ch R = 1 ,22502.3 ,301.7,299.9,295.8
XS GIS Cut Line= 3
     1972979.094      313066.719     1972650.117      313509.592
     1972282.924       313912.32
#Sta/Elev= 30
       0 2040.59    49.3 2014.53    98.5 1986.36   118.2 1977.12   147.8 1965.83
   285.7 1920.22   384.2 1879.97   394.1 1875.02   403.9 1867.22   423.6 1846.78
   433.5 1840.07   443.3 1837.23   492.6  1833.7   512.3 1830.84     532 1824.26
   544.2  1817.8   551.7    1814   559.2 1812.56   561.6  1812.1   571.5 1813.52
   601.2 1827.55   640.9 1833.48   650.8  1837.7   710.2 1883.62   759.8 1917.87
   819.2 1953.33   858.9 1973.54    1057 2038.51  1076.9 2048.22  1096.7  2062.7
#Mann= 3 , 0 , 0
       0      .1       0   544.2    .045       0   559.2      .1       0
Bank Sta=544.2,559.2
XS Rating Curve= 0 ,0
Exp/Cntr=0.3,0.1

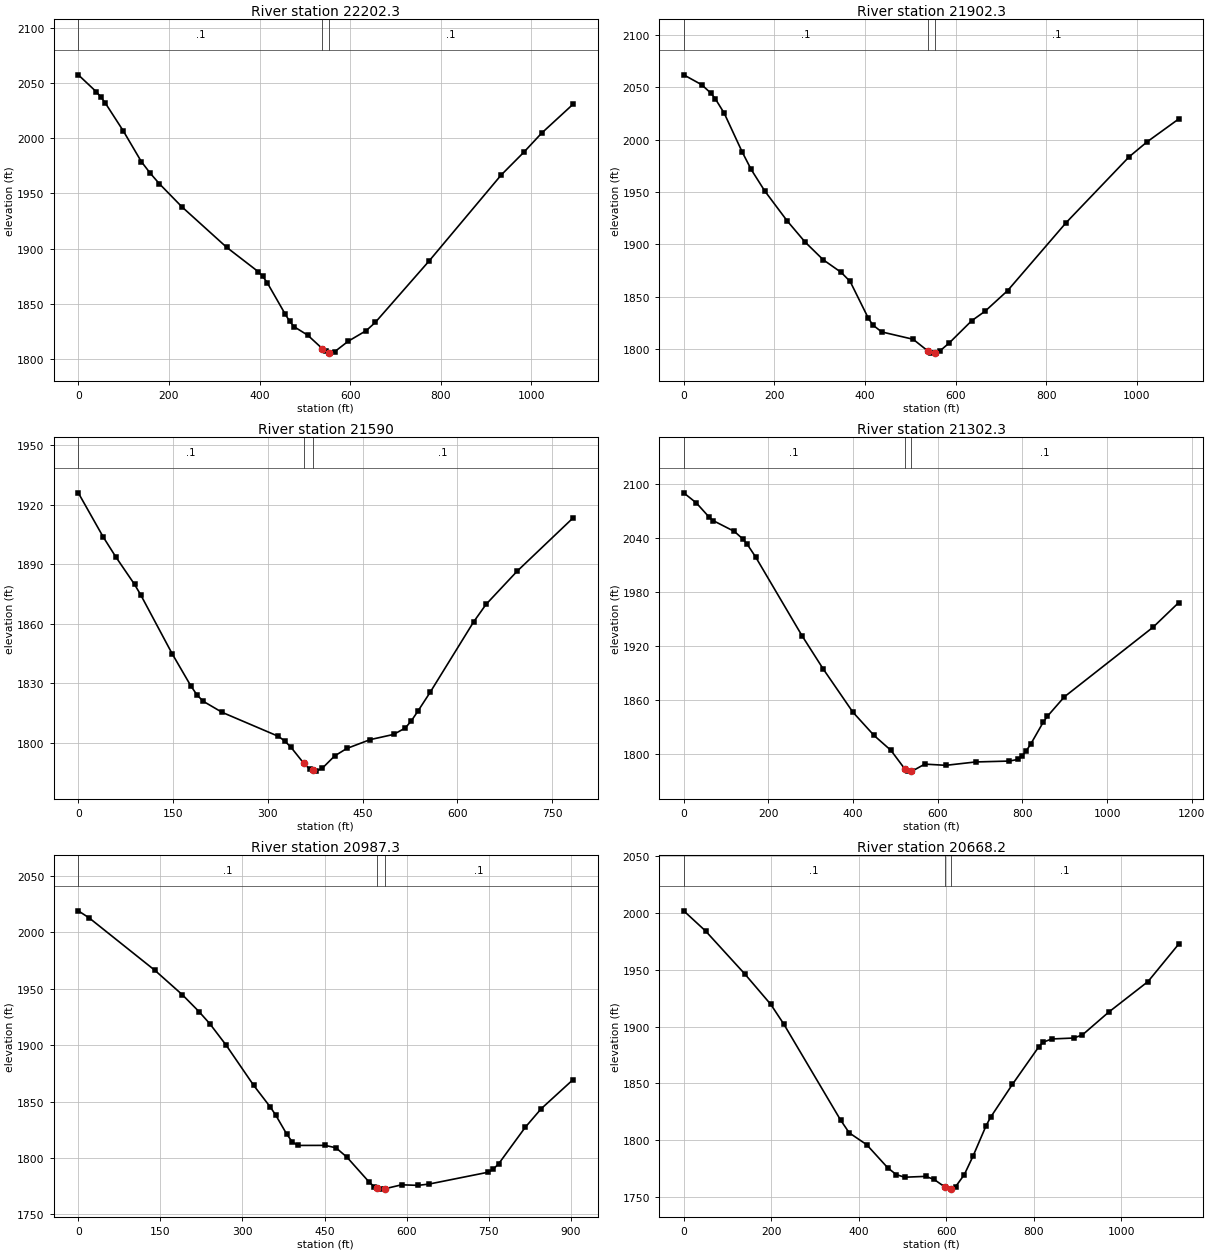
Type RM Length L Ch R = 1 ,22202.3 ,297.1,300,302.7
XS GIS Cut Line= 3
     1972711.477      312850.979     1972423.226      313314.689
     1972134.364       313778.02
#Sta/Elev= 30
       0 2057.61    39.7 2042.25    49.6 2037.57    59.6 2032.02    99.3 2006.72
     139 1978.93   158.8  1968.3   178.7 1958.86   228.3 1937.95   327.6 1901.02
   397.1 1878.99     407 1874.78     417 1868.92   456.6 1840.46   466.6  1833.8
   476.5 1828.96   506.3 1821.35   538.5 1809.16     546 1806.55   553.5 1805.43
   555.9 1805.07   565.8 1806.38   595.6 1815.85   635.4  1825.5   655.2 1832.87
   774.3 1888.78   933.2 1966.72   982.8 1987.22  1022.5 2004.73    1092    2031
#Mann= 3 , 0 , 0
       0      .1       0   538.5    .045       0   553.5      .1       0
Bank Sta=538.5,553.5
XS Rating Curve= 0 ,0
Exp/Cntr=0.3,0.1

Type RM Length L Ch R = 1 ,21902.3 ,307,312.3,317.6
XS GIS Cut Line= 3
     1972519.833      312721.314     1972175.961      313145.423
      1971832.09      313569.531
#Sta/Elev= 30
       0 2061.65    39.7 2052.21    59.6 2044.32    69.5 2038.98    89.4 2025.07
     129 1988.18   148.9 1971.43   178.7 1951.06   228.3 1922.46     268 1902.22
   307.8 1885.41   347.4 1873.43   367.3  1864.7     407 1830.06     417 1823.35
   436.8 1816.65   506.3 1809.63   538.5 1798.57     546 1796.62   553.5 1796.48
   555.9 1796.43   565.8 1798.69   585.7 1806.02   635.4 1827.26   665.1  1836.4
   714.8 1856.01   843.8 1920.74   982.8 1983.49  1022.5 1997.76    1092 2019.48
#Mann= 3 , 0 , 0
       0      .1       0   538.5    .045       0   553.5      .1       0
Bank Sta=538.5,553.5
XS Rating Curve= 0 ,0
Exp/Cntr=0.3,0.1

Type RM Length L Ch R = 1 ,21590   ,303,287.7,273.8
XS GIS Cut Line= 4
     1972262.505      312691.148     1971932.616       312943.83
      1971857.39      313012.514     1971723.803      313242.134
#Sta/Elev= 30
       0 1925.99    39.6 1903.64    59.4 1893.66      89 1879.82    98.9 1874.46
   148.4  1844.9   178.1 1828.61     188 1823.97   197.9 1820.81   227.6 1815.27
   316.6 1803.17   326.5 1800.85   336.4  1797.7   356.4 1789.73   366.1 1786.63
   371.4 1786.08     376 1785.61   385.9    1787   405.6 1793.25   424.8 1797.03
   461.8 1801.49   498.9 1804.12   517.4 1807.34   527.2 1811.05   537.1 1815.71
   556.8 1825.37   625.6 1860.89   645.3 1869.75   694.5 1886.48   783.1 1913.37
#Mann= 3 , 0 , 0
       0      .1       0   356.4    .045       0   371.4      .1       0
Bank Sta=356.4,371.4
XS Rating Curve= 0 ,0
Exp/Cntr=0.3,0.1

Type RM Length L Ch R = 1 ,21302.3 ,326.1,314.6,301.6
XS GIS Cut Line= 3
     1971889.693      312219.499     1971763.554      312733.757
     1971572.091       313343.91
#Sta/Elev= 30
       0 2090.34      30 2079.03    59.9 2063.36    69.9 2059.34   119.9 2047.29
   139.9 2038.85   149.9 2033.17   169.8 2018.98   279.7 1931.09   329.7 1894.13
   399.6 1846.19   449.6 1820.23   489.5 1803.65     522 1783.14   529.5 1780.53
     537 1780.52   539.5 1780.51   569.5 1788.32   619.4 1786.97   689.4 1790.71
   769.3 1791.72   789.3 1793.55   799.3 1797.36   809.3 1803.27   819.3 1810.24
   849.2  1834.9   859.2 1841.62   899.2 1863.21    1109 1940.83    1169 1967.97
#Mann= 3 , 0 , 0
       0      .1       0     522    .045       0     537      .1       0
Bank Sta=522,537
XS Rating Curve= 0 ,0
Exp/Cntr=0.3,0.1

Type RM Length L Ch R = 1 ,20987.3 ,305.8,319.4,333.3
XS GIS Cut Line= 4
     1971328.962      312216.413     1971441.291      312673.601
     1971499.197      312875.395     1971557.103      313091.227
#Sta/Elev= 30
       0 2018.97      20 2012.65   140.2 1966.16   190.3 1944.56   220.4 1929.78
   240.4 1918.91   270.4 1899.81   320.5 1864.34   350.6 1845.33   360.6 1838.14
   380.6 1821.38   390.6  1814.5   400.7 1811.15   450.8  1811.2   470.8 1809.08
   490.8 1800.79   530.8 1779.06   540.8 1774.47   545.5 1773.52   550.8 1772.45
   560.5 1772.82   590.8 1776.28   620.7 1775.79   640.7 1776.91   748.7 1787.41
   758.4 1790.21   768.2 1794.98   816.7 1827.22   845.9 1843.71   904.2 1869.53
#Mann= 3 , 0 , 0
       0      .1       0   545.5    .045       0   560.5      .1       0
Bank Sta=545.5,560.5
XS Rating Curve= 0 ,0
Exp/Cntr=0.3,0.1

Type RM Length L Ch R = 1 ,20668.2 ,263.3,265.8,270.3
XS GIS Cut Line= 4
     1971217.039      312197.862     1971227.214      312615.695
     1971172.868      312780.004     1970989.773      313287.505
#Sta/Elev= 30
       0 2001.64    49.8 1983.98   139.3 1946.28     199  1919.4   228.9 1901.96
   358.2 1817.93   378.2 1806.56     418 1796.19     466  1775.9   485.3 1769.97
   504.5 1767.59   552.6 1768.33   571.8  1765.7   596.3 1759.11     611 1757.13
   611.3 1757.19     621 1759.22     641 1769.85     661 1786.18   690.9 1812.94
   700.9 1820.18   750.9 1849.17   810.8 1881.96   820.8 1886.19   840.8 1889.06
   890.8 1889.88   910.7 1892.59   970.7 1912.58  1060.6 1939.48  1130.5 1972.28
#Mann= 3 , 0 , 0
       0      .1       0   596.3    .045       0   611.3      .1       0
Bank Sta=596.3,611.3
XS Rating Curve= 0 ,0
Exp/Cntr=0.3,0.1