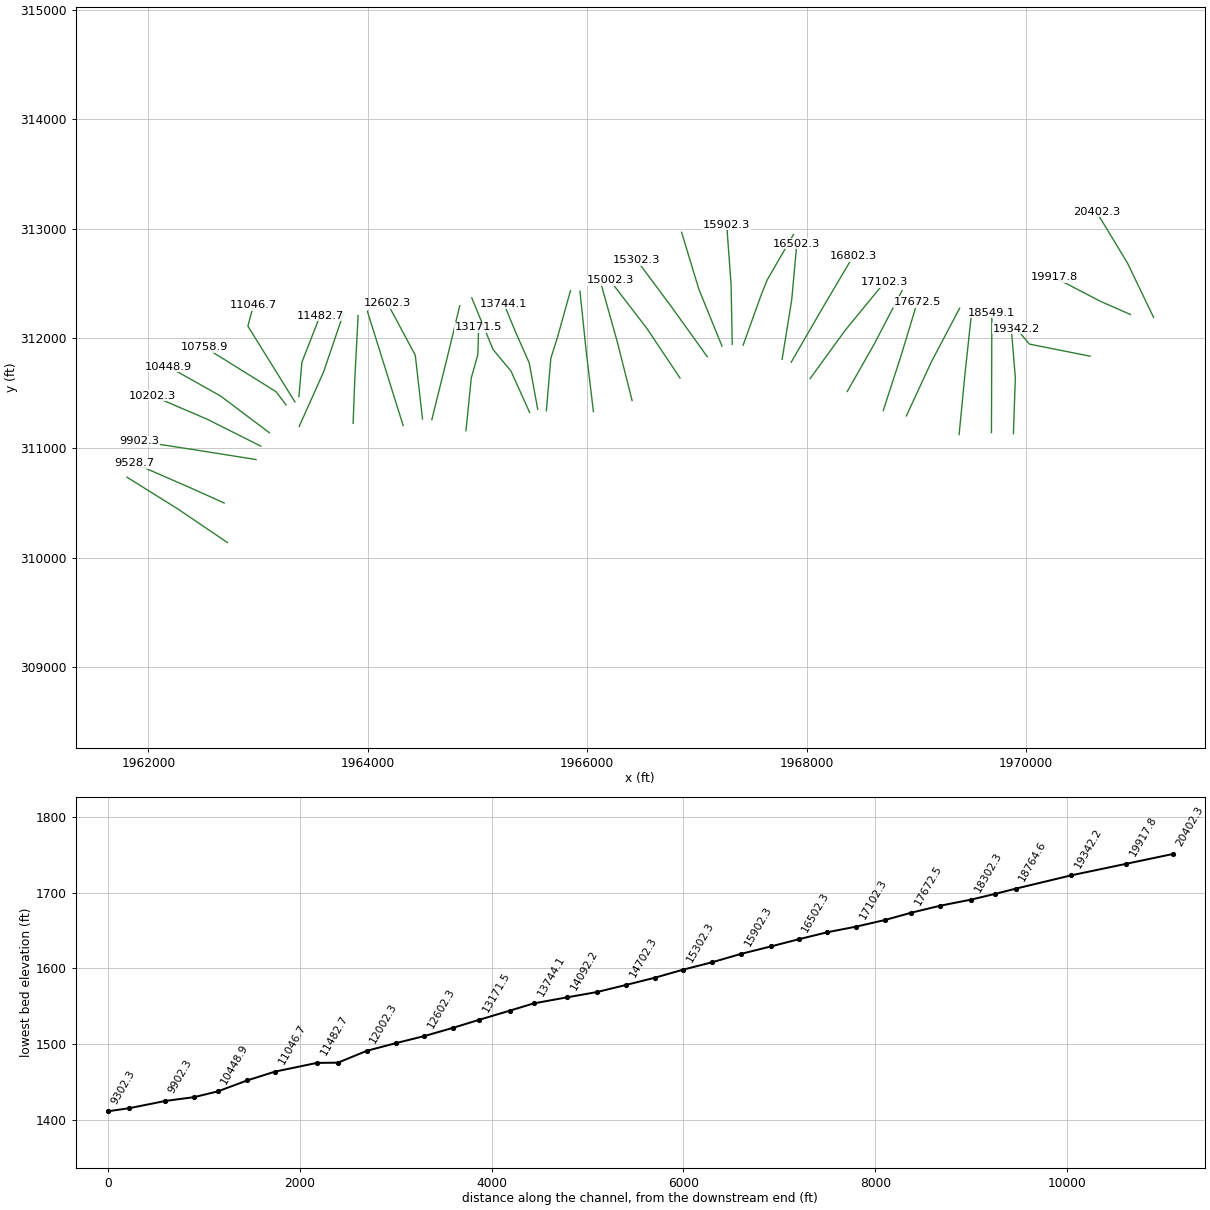
HEC-RAS study LaurelCrk.prj: LaurelCrk

--- LaurelCrk.g01 (geometry) --- (continued)

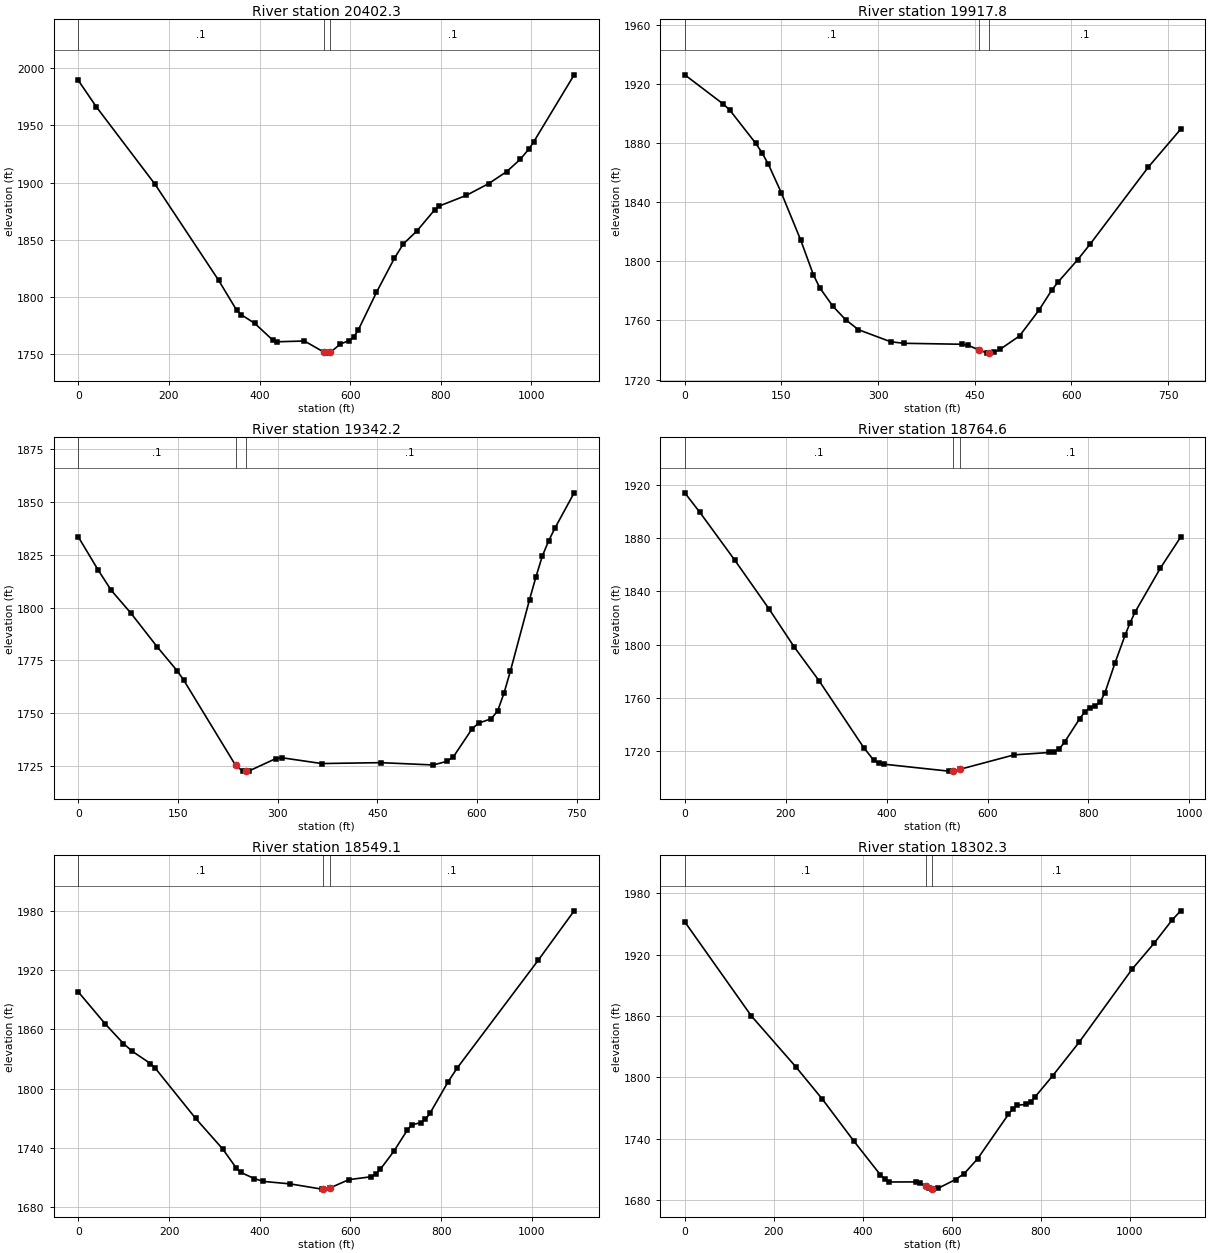
Type RM Length L Ch R = 1 ,20402.3 ,469.8,484.5,497.1
XS GIS Cut Line= 3
     1971161.973      312192.115     1970924.756      312687.046
     1970642.296       313153.72
#Sta/Elev= 30
       0 1989.41    39.9 1966.21   169.6 1898.37   309.4 1814.65   349.3 1788.42
   359.2  1784.5   389.2 1776.88   429.1  1762.2   439.1 1760.72     499 1761.41
   541.3 1751.81   548.8 1750.79   556.3 1751.49   578.6 1758.83   598.4  1761.8
   608.4 1765.06   618.3 1771.41   657.9  1803.9   697.6 1833.85   717.4 1846.42
   747.2 1857.67   786.9  1876.4   796.8 1879.54   856.3 1888.83   905.9 1899.19
   945.6 1909.68   975.3 1920.38   995.2 1929.79  1005.1 1935.74  1094.3 1994.32
#Mann= 3 , 0 , 0
       0      .1       0   541.3    .045       0   556.3      .1       0
Bank Sta=541.3,556.3
XS Rating Curve= 0 ,0
Exp/Cntr=0.3,0.1

Type RM Length L Ch R = 1 ,19917.8 ,569.3,575.5,581.7
XS GIS Cut Line= 3
     1970950.968      312217.983     1970677.004      312338.596
     1970260.029      312555.699
#Sta/Elev= 30
       0 1926.16    59.9 1906.32    69.8 1902.32   109.8 1879.98   119.7 1873.57
   129.7 1865.64   149.7 1846.44   179.6 1814.66   199.6 1790.83   209.5 1782.09
   229.5 1769.78   249.4  1760.6   269.4 1753.78   319.3 1745.63   339.4 1744.58
   429.4 1743.92   439.4  1743.3   456.8 1739.97   469.4 1737.92   471.8 1738.03
   479.4 1738.36   489.4 1740.54   519.4 1749.54   549.4 1766.86   569.4  1780.5
   579.4  1786.1   609.4 1800.96   629.4 1811.88   719.4 1863.82   769.4 1889.32
#Mann= 3 , 0 , 0
       0      .1       0   456.8    .045       0   471.8      .1       0
Bank Sta=456.8,471.8
XS Rating Curve= 0 ,0
Exp/Cntr=0.3,0.1

Type RM Length L Ch R = 1 ,19342.2 ,606.6,577.6,548.6
XS GIS Cut Line= 3
      1970583.96      311837.191     1970030.864      311947.466
     1969913.697      312087.032
#Sta/Elev= 30
       0 1833.42    29.7 1817.83    49.5 1808.18    79.2 1797.34   118.7 1781.42
   148.4 1770.23   158.3 1765.84   236.7 1725.36   247.4 1722.64   251.7  1722.7
   257.2 1722.77   296.8 1728.52   306.7 1728.95   366.1 1726.23   455.1 1726.65
   534.3 1725.55   554.1 1727.23     564 1729.21   592.8 1742.74   602.4 1745.35
   621.5 1747.41   631.1  1751.2   640.7 1759.61   650.3 1770.05   679.1 1803.82
   688.7 1814.53   698.2 1824.31   707.8 1831.57   717.4 1837.67   746.2 1854.29
#Mann= 3 , 0 , 0
       0      .1       0   236.7    .045       0   251.7      .1       0
Bank Sta=236.7,251.7
XS Rating Curve= 0 ,0
Exp/Cntr=0.3,0.1

Type RM Length L Ch R = 1 ,18764.6 ,217.8,215.5,213.2
XS GIS Cut Line= 3
     1969884.845      311129.438     1969902.392      311641.819
     1969863.788      312110.332
#Sta/Elev= 30
       0 1914.06    29.6 1899.53    98.6 1863.75   167.6 1826.53   216.9 1798.31
   266.2 1772.93   354.9 1722.63   374.6 1713.27   384.5 1711.02   394.4 1710.32
   522.7  1705.1   530.7  1705.2   545.7  1706.5   652.7 1717.31   722.7  1719.1
   732.7 1719.71   742.7 1721.97   752.7 1726.86   782.7 1744.47   792.7 1749.53
   802.7  1752.7   812.8 1754.11   822.8 1756.65   832.8 1763.96   852.8 1786.43
   872.8 1807.22   882.8 1816.64   892.8 1824.72   942.8 1857.62   982.8 1880.76
#Mann= 3 , 0 , 0
       0      .1       0   530.7    .045       0   545.7      .1       0
Bank Sta=530.7,545.7
XS Rating Curve= 0 ,0
Exp/Cntr=0.3,0.1

Type RM Length L Ch R = 1 ,18549.1 ,248.8,246.7,244.4
XS GIS Cut Line= 3
     1969684.705      311139.991      1969686.56      311676.914
     1969688.421      312233.349
#Sta/Elev= 30
       0 1897.92    59.7 1865.33    99.4 1845.66   119.3 1837.68   159.1 1825.38
     169 1821.05   258.5 1769.92   318.2 1738.94     348 1719.74     358 1715.14
   387.8 1708.92   407.7 1706.01   467.3 1703.46   536.9 1698.17   540.2 1698.19
   555.2 1699.44   596.5 1707.76   646.2 1710.75   656.2 1713.25   666.1 1718.35
   695.9  1736.6   725.7 1758.14   735.6 1763.28   755.5 1765.56   765.5 1768.86
   775.4 1774.98   815.2 1806.72     835 1820.57  1013.9  1929.9  1093.4  1980.1
#Mann= 3 , 0 , 0
       0      .1       0   540.2    .045       0   555.2      .1       0
Bank Sta=540.2,555.2
XS Rating Curve= 0 ,0
Exp/Cntr=0.3,0.1

Type RM Length L Ch R = 1 ,18302.3 ,336.7,329.2,320.8
XS GIS Cut Line= 3
     1969390.011      311122.419       1969442.7      311668.845
     1969503.123      312231.123
#Sta/Elev= 30
       0 1952.23   149.7 1860.12   249.5 1810.44   309.4 1778.68   379.3 1738.17
   439.2 1704.99   449.2  1700.5   459.1 1697.76     519 1697.83     529 1696.63
   541.5 1693.54     549 1691.58   556.5 1690.97   558.9 1690.77   568.8 1691.44
   608.5 1700.18   628.3 1706.03   658.1 1720.44   727.5 1763.98   737.5  1769.6
   747.4  1772.9   767.2 1773.64   777.2  1776.4   787.1 1780.86   826.8 1801.61
   886.3 1834.42  1005.3 1905.87    1055 1931.39  1094.6 1953.63  1114.5 1963.02
#Mann= 3 , 0 , 0
       0      .1       0   541.5    .045       0   556.5      .1       0
Bank Sta=541.5,556.5
XS Rating Curve= 0 ,0
Exp/Cntr=0.3,0.1

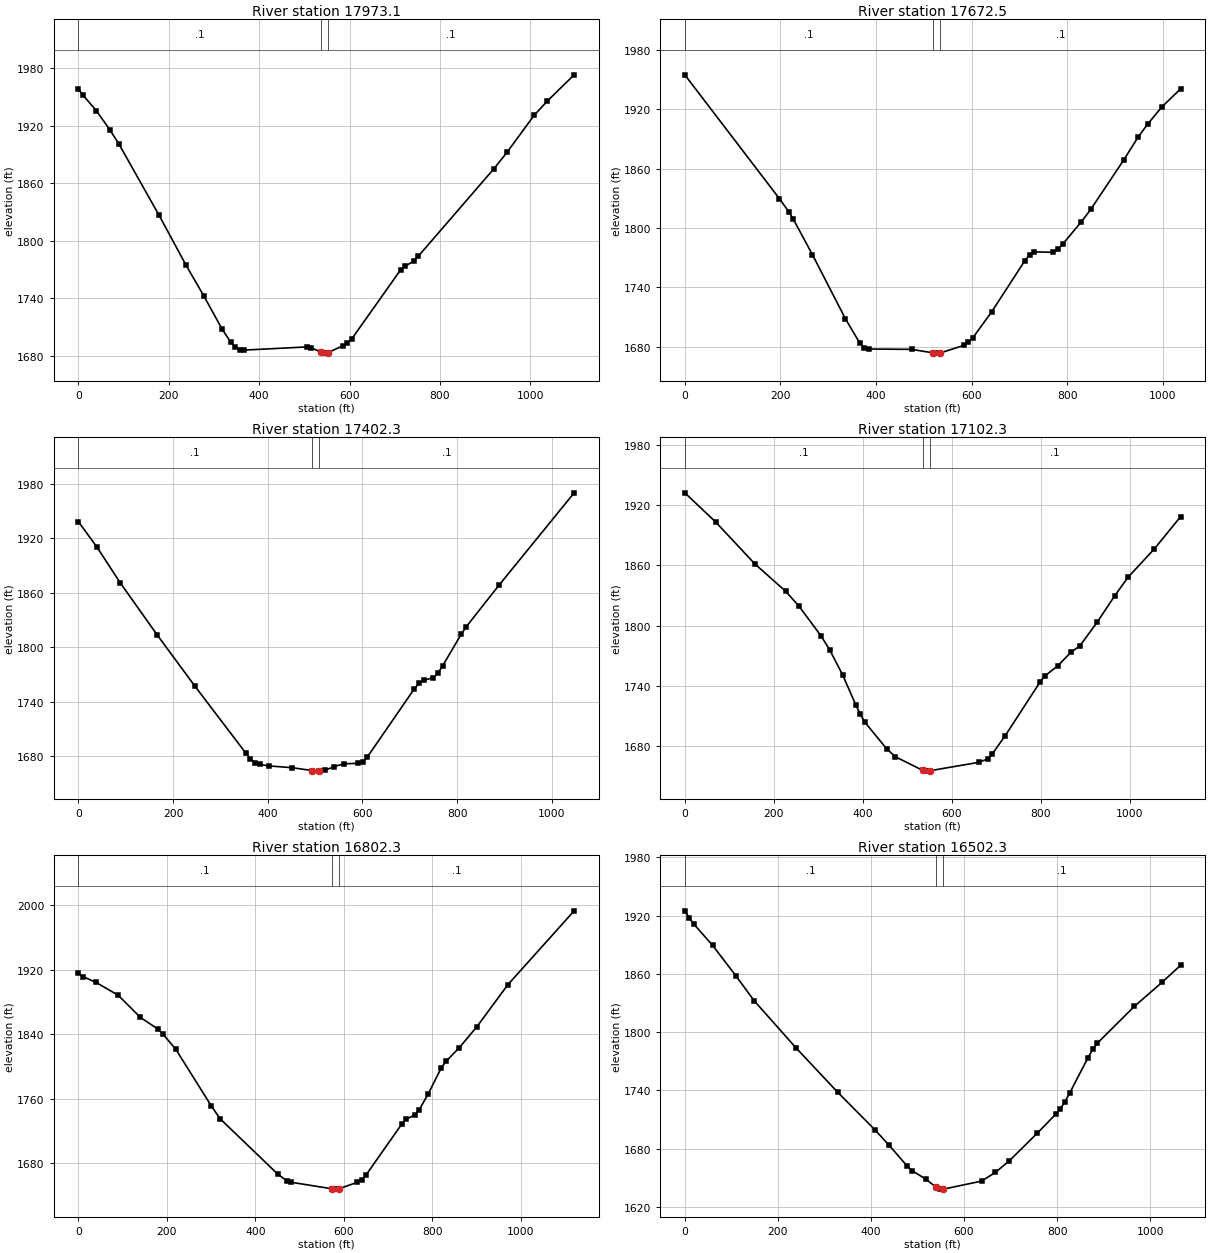
Type RM Length L Ch R = 1 ,17973.1 ,298,300.7,304.9
XS GIS Cut Line= 3
     1968908.988      311292.103     1969137.846      311787.139
     1969394.506      312274.972
#Sta/Elev= 30
       0 1958.63     9.9 1952.31    39.7 1935.95    69.4  1916.1    89.2 1901.48
   178.5 1826.63     238 1774.57   277.6 1742.24   317.3 1708.13   337.1 1693.84
   347.1 1688.59     357 1686.19   366.9 1685.67   505.7    1689   515.6 1688.25
   536.8 1683.24   545.4  1682.5   551.8 1682.92   584.8 1690.19   594.6 1692.86
   604.4 1697.13   712.7  1769.5   722.6 1773.31   742.2 1778.84   752.1  1783.9
   919.4 1875.36     949 1892.92    1008    1931  1037.6 1946.15  1096.6 1973.36
#Mann= 3 , 0 , 0
       0      .1       0   536.8    .045       0   551.8      .1       0
Bank Sta=536.8,551.8
XS Rating Curve= 0 ,0
Exp/Cntr=0.3,0.1

Type RM Length L Ch R = 1 ,17672.5 ,274.7,270.1,265.9
XS GIS Cut Line= 3
     1968698.647       311341.76     1968860.082      311840.104
     1969009.234      312331.429
#Sta/Elev= 30
       0 1954.97   197.7 1829.79   217.4 1816.56   227.3 1808.63   266.9 1773.08
     336 1708.13   365.7 1683.77   375.6 1678.74   385.5 1677.45   474.4 1677.11
   519.6 1673.57   523.8  1673.3   534.6 1673.47   583.1 1681.09     593  1684.1
   602.8 1688.94   642.3 1715.28   711.4 1766.88   721.3 1772.79   731.2 1775.82
   770.7 1775.31   780.6  1778.5   790.4 1783.51   829.9 1806.39   849.7 1819.07
   918.8 1869.19   948.4 1891.96   968.2 1905.01   997.8 1922.34  1037.3 1940.83
#Mann= 3 , 0 , 0
       0      .1       0   519.6    .045       0   534.6      .1       0
Bank Sta=519.6,534.6
XS Rating Curve= 0 ,0
Exp/Cntr=0.3,0.1

Type RM Length L Ch R = 1 ,17402.3 ,302.6,300,295.4
XS GIS Cut Line= 3
     1968370.512      311515.479     1968617.914      311951.251
     1968869.861      312435.716
#Sta/Elev= 30
       0 1938.41    39.3 1910.31    88.4 1871.05     167 1813.32   245.6  1757.7
   353.7 1683.61   363.6 1677.44   373.4 1673.12   383.2  1671.1   402.8 1669.52
     452 1667.54   493.6 1664.46   508.6 1663.82     511 1663.79     521 1664.72
   540.8 1668.88   560.7 1671.81   590.5  1672.4   600.4 1673.97   610.3 1679.24
   709.6 1754.35   719.5 1760.27   729.5  1763.6   749.3 1766.68   759.2 1771.44
   769.2 1779.45   808.9 1814.61   818.8  1822.3   888.3 1868.25  1047.2 1969.99
#Mann= 3 , 0 , 0
       0      .1       0   493.6    .045       0   508.6      .1       0
Bank Sta=493.6,508.6
XS Rating Curve= 0 ,0
Exp/Cntr=0.3,0.1

Type RM Length L Ch R = 1 ,17102.3 ,297.6,300,303.5
XS GIS Cut Line= 3
     1968031.245      311632.446     1968349.707      312071.235
     1968711.997      312513.406
#Sta/Elev= 30
       0 1932.03      69 1903.16   157.7 1861.14   226.7 1834.02   256.3 1819.32
   305.6 1789.95   325.3 1775.94   354.9 1750.52   384.4 1720.76   394.3 1711.55
   404.2 1703.92   453.5 1677.31   473.2 1669.36   534.7 1655.79   542.2 1655.09
   549.7 1655.43   660.4 1663.82   680.2 1667.26     690 1671.76   719.6 1690.22
   798.4    1744   808.3 1749.63   837.8 1759.84   867.4 1773.46   887.1  1779.5
   926.6 1803.46     966 1829.68   995.5 1847.92  1054.7 1876.21  1113.8 1908.34
#Mann= 3 , 0 , 0
       0      .1       0   534.7    .045       0   549.7      .1       0
Bank Sta=534.7,549.7
XS Rating Curve= 0 ,0
Exp/Cntr=0.3,0.1

Type RM Length L Ch R = 1 ,16802.3 ,291.7,299.9,310
XS GIS Cut Line= 3
     1967859.175       311782.23     1968149.702      312284.797
     1968424.106      312749.778
#Sta/Elev= 30
       0 1916.03      10 1911.77      40 1904.42    90.1  1888.5   140.1    1861
   180.2 1846.34   190.2 1840.92   220.2 1821.39   300.3 1751.22   320.3 1735.14
   450.4 1666.42   470.4 1658.36   480.4 1656.26     573 1648.12   580.5 1647.69
     588 1647.97   630.5  1656.2   640.5 1659.56   650.5 1665.55   730.5 1728.22
   740.5 1734.34   760.5 1739.91   770.5 1746.41   790.5 1765.92   820.5 1798.62
   830.5 1806.24   860.4  1823.1   900.4 1849.28   970.4 1901.49  1120.4 1993.35
#Mann= 3 , 0 , 0
       0      .1       0     573    .045       0     588      .1       0
Bank Sta=573,588
XS Rating Curve= 0 ,0
Exp/Cntr=0.3,0.1

Type RM Length L Ch R = 1 ,16502.3 ,289.6,284.5,277.8
XS GIS Cut Line= 3
     1967776.673      311808.572     1967863.702      312349.831
     1967910.773      312864.867
#Sta/Elev= 30
       0 1924.84      10 1917.32    19.9 1910.89    59.8 1889.25   109.6 1858.04
   149.5 1832.05   239.2 1783.65   328.9 1737.91   408.7 1699.37   438.6 1683.78
   478.4 1661.84   488.4 1657.36   518.3 1648.55   540.7 1640.12   548.2 1638.39
   555.7 1638.39   637.7 1646.65   667.6 1655.65   697.4 1667.66   757.1 1695.83
   796.9 1715.45   806.8 1720.91   816.8 1728.34   826.7 1737.05   866.5 1773.78
   876.4 1782.11   886.4 1788.57   965.9 1826.41  1025.6 1851.31  1065.4 1868.78
#Mann= 3 , 0 , 0
       0      .1       0   540.7    .045       0   555.7      .1       0
Bank Sta=540.7,555.7
XS Rating Curve= 0 ,0
Exp/Cntr=0.3,0.1

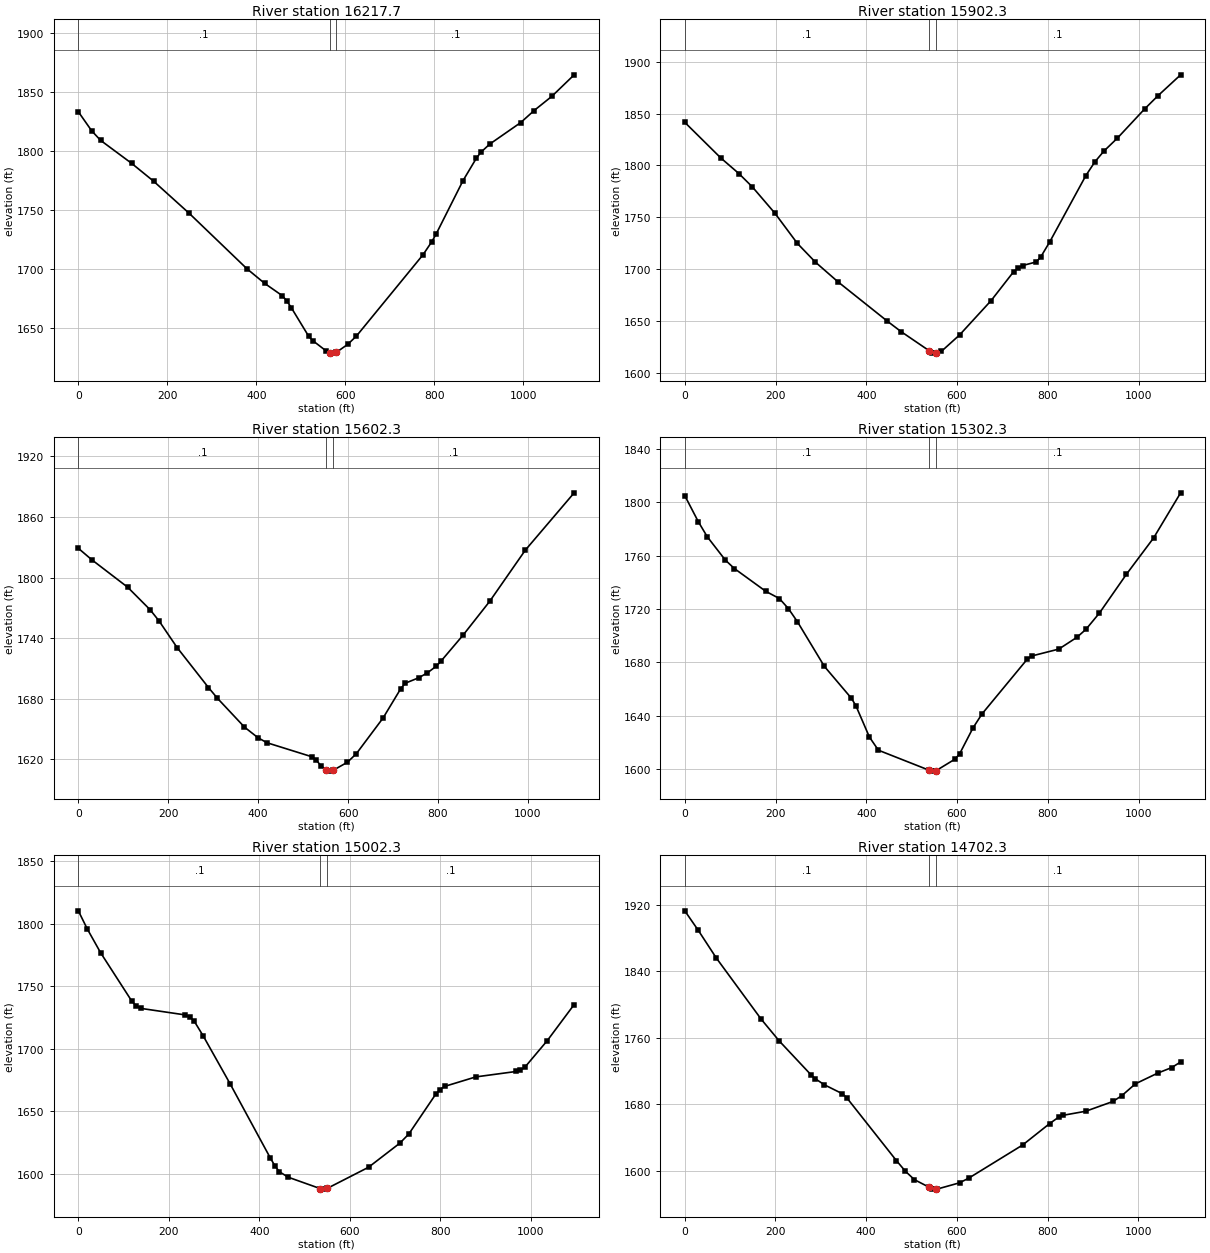
Type RM Length L Ch R = 1 ,16217.7 ,306.3,315.5,325.9
XS GIS Cut Line= 4
     1967421.212      311938.064     1967589.657      312406.882
     1967640.544      312533.223     1967880.176      312948.416
#Sta/Elev= 30
       0 1833.56    29.9 1817.48    49.8  1809.4   119.6  1789.9   169.4 1774.63
   249.1 1747.52   378.6 1700.62   418.4 1688.24   458.3 1677.72   468.3 1673.33
   478.2 1667.74   517.6  1643.3   527.4 1639.48   556.5 1631.04   564.6 1629.55
     576 1629.12   579.6 1629.77   605.2 1636.57   624.6 1643.53   774.2  1712.4
   794.2  1723.6   804.2 1730.34   864.1 1775.21     894 1794.13     904 1799.14
     924 1806.13   993.9 1824.44  1023.9 1834.61  1063.8 1846.67  1113.8 1864.84
#Mann= 3 , 0 , 0
       0      .1       0   564.6    .045       0   579.6      .1       0
Bank Sta=564.6,579.6
XS Rating Curve= 0 ,0
Exp/Cntr=0.3,0.1

Type RM Length L Ch R = 1 ,15902.3 ,291.7,300,305
XS GIS Cut Line= 3
     1967322.009      311945.086     1967311.308      312490.816
     1967271.519      313036.306
#Sta/Elev= 30
       0 1841.48    79.4 1807.16   119.1 1792.19   148.9 1779.29   198.5    1754
   248.1 1724.86   287.8 1706.84   337.4 1687.92   446.6 1649.87   476.4 1639.98
   538.3 1621.56   545.8 1619.69   553.3 1619.29   555.8 1619.16   565.7 1620.92
   605.5 1636.62   675.1 1669.76   724.8 1697.63   734.8 1701.28   744.7 1703.56
   774.6    1707   784.5  1711.8   804.4 1726.38   883.9 1790.17   903.8 1803.42
   923.7 1813.77   953.6 1826.35  1013.2 1854.26    1043 1867.18  1092.8 1887.26
#Mann= 3 , 0 , 0
       0      .1       0   538.3    .045       0   553.3      .1       0
Bank Sta=538.3,553.3
XS Rating Curve= 0 ,0
Exp/Cntr=0.3,0.1

Type RM Length L Ch R = 1 ,15602.3 ,294.6,300,307.8
XS GIS Cut Line= 3
     1967228.321      311929.738     1967017.979      312447.733
     1966860.136      312968.071
#Sta/Elev= 30
       0 1828.94      30 1817.57   109.8 1790.35   159.7 1768.04   179.7 1756.86
   219.6 1730.64   289.5 1690.93   309.5 1680.28   369.4 1651.82   399.3 1641.33
   419.3 1636.32   519.1 1622.44   529.1 1619.15   539.1  1613.7   551.6 1609.08
   559.1 1608.15   566.6 1608.94   598.6 1616.97   618.4 1625.45   677.7 1660.74
   717.3 1689.96   727.1 1695.26   756.8 1700.59   776.6 1705.59   796.4 1712.23
   806.2 1716.91   855.7 1742.88     915 1776.42   994.1 1827.07  1102.8  1883.9
#Mann= 3 , 0 , 0
       0      .1       0   551.6    .045       0   566.6      .1       0
Bank Sta=551.6,566.6
XS Rating Curve= 0 ,0
Exp/Cntr=0.3,0.1

Type RM Length L Ch R = 1 ,15302.3 ,300.8,300,300.3
XS GIS Cut Line= 3
     1967094.251      311832.461     1966776.342      312276.103
     1966450.325      312715.394
#Sta/Elev= 30
       0 1804.92    29.8 1785.39    49.6 1774.08    89.3 1756.65   109.2 1750.32
   178.6  1733.2   208.4 1727.83   228.2 1720.33   248.1 1710.52   307.6 1676.98
   367.2 1653.08   377.1 1647.46   406.9    1624   426.7 1614.14   538.3 1599.16
   545.8 1598.46   553.3 1598.69   595.5 1607.45   605.5 1611.29   635.3 1630.92
   655.2 1641.39   754.7 1682.34   764.6 1684.76   824.3 1689.92   864.1 1698.73
     884 1704.68   913.8 1716.91   973.5 1746.08  1033.2 1773.21  1092.8 1807.04
#Mann= 3 , 0 , 0
       0      .1       0   538.3    .045       0   553.3      .1       0
Bank Sta=538.3,553.3
XS Rating Curve= 0 ,0
Exp/Cntr=0.3,0.1

Type RM Length L Ch R = 1 ,15002.3 ,307.7,299.9,291.3
XS GIS Cut Line= 3
     1966845.651       311638.31     1966544.705      312089.508
     1966208.218      312528.354
#Sta/Elev= 30
       0 1810.17    19.7 1795.72    49.3 1776.62   118.3 1737.87   128.2 1734.05
     138 1732.18   236.7 1726.93   246.5  1725.3   256.4 1721.72   276.1 1710.03
   335.3 1671.89     424 1612.68   433.9 1606.52   443.7 1601.69   463.5 1597.23
   534.9 1588.04   542.4 1587.68   549.9 1588.28   641.1 1605.16   710.2 1624.41
     730 1631.69   789.2 1663.38   799.1 1667.32     809 1669.78   878.1  1677.4
     967 1681.73   976.8 1682.82   986.7 1685.22  1036.1 1706.45  1095.4 1735.25
#Mann= 3 , 0 , 0
       0      .1       0   534.9    .045       0   549.9      .1       0
Bank Sta=534.9,549.9
XS Rating Curve= 0 ,0
Exp/Cntr=0.3,0.1

Type RM Length L Ch R = 1 ,14702.3 ,302.8,300,296.2
XS GIS Cut Line= 3
     1966409.082      311432.595      1966275.57      311962.184
     1966128.179      312489.354
#Sta/Elev= 30
       0 1912.76    29.8 1889.23    69.5 1856.05   168.8 1782.25   208.5 1756.18
     278 1715.81     288 1710.81   307.8 1703.62   347.6 1692.84   357.5  1687.8
   466.7 1612.48   486.6 1599.64   506.4 1589.55   538.7  1580.5   546.2 1578.76
   553.7 1578.31   556.1 1578.16   605.9 1585.74   625.8 1591.21   745.2 1631.24
   804.9 1657.05   824.8 1664.76   834.8 1666.97   884.5 1671.83   944.3 1683.55
   964.2 1690.68     994 1704.82  1043.8 1717.82  1073.6 1724.23  1093.6 1731.02
#Mann= 3 , 0 , 0
       0      .1       0   538.7    .045       0   553.7      .1       0
Bank Sta=538.7,553.7
XS Rating Curve= 0 ,0
Exp/Cntr=0.3,0.1

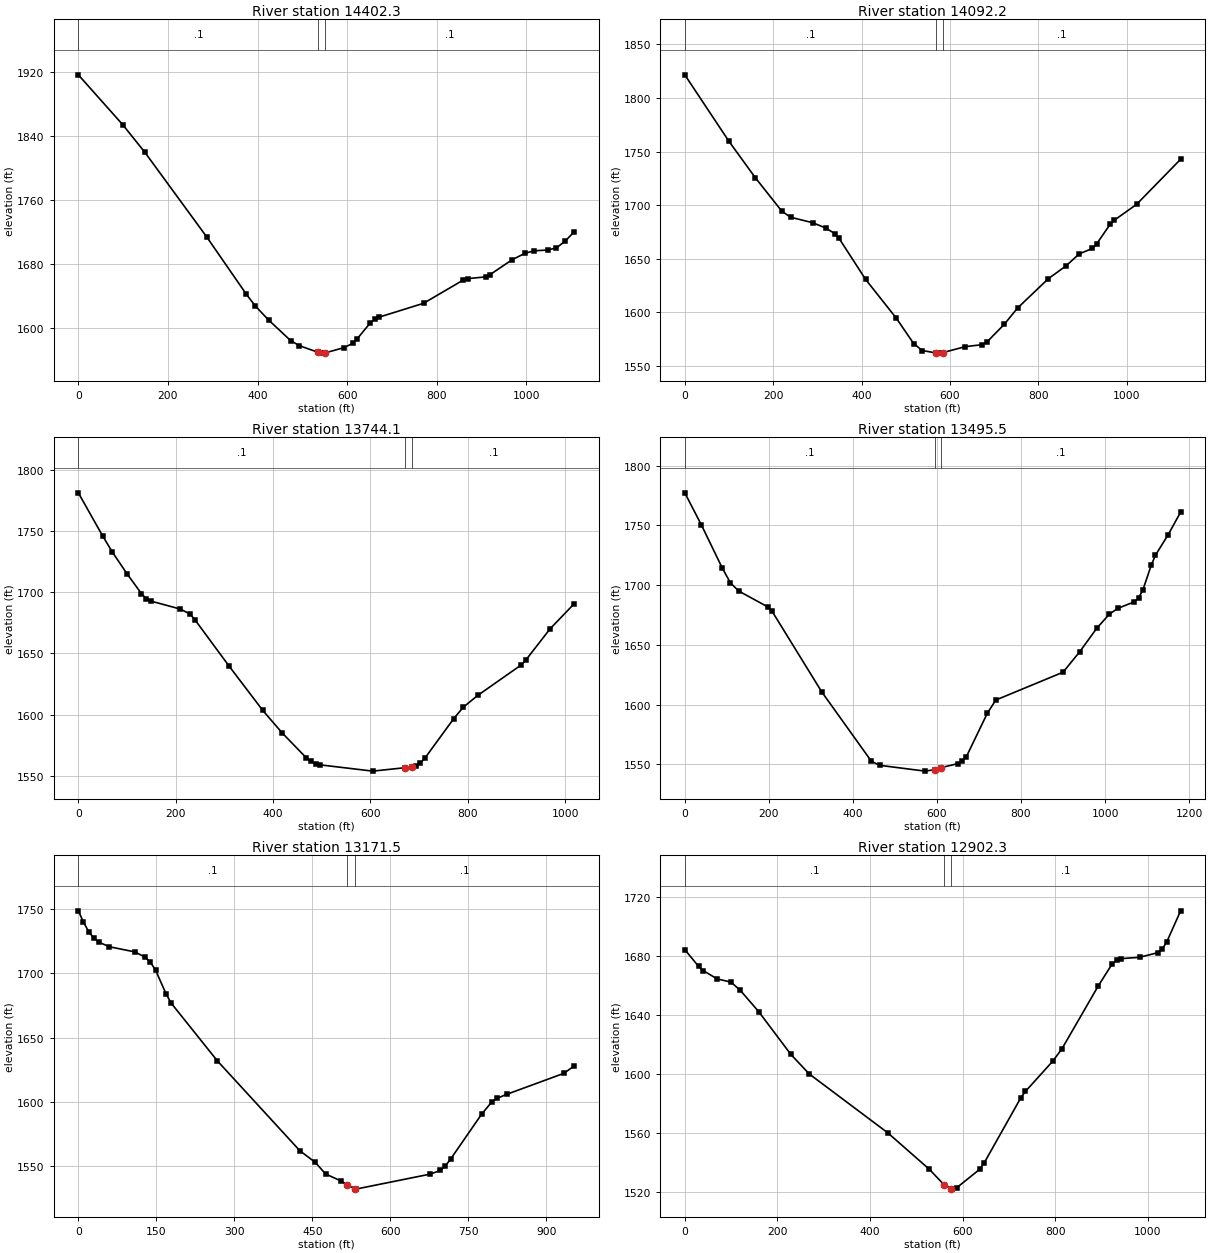
Type RM Length L Ch R = 1 ,14402.3 ,319.7,310.1,300.8
XS GIS Cut Line= 3
     1966056.619      311331.175     1965991.938      311870.191
     1965933.728      312430.839
#Sta/Elev= 30
       0 1916.57    98.7  1854.5   148.1 1820.04   286.2 1714.29   375.1 1642.31
   394.8 1627.88   424.4 1610.36   473.8 1584.51   493.5 1578.14   535.4 1569.83
   542.9 1568.88   550.4 1569.11   592.3 1575.66   612.1 1580.93     622 1586.56
   651.7  1606.8   661.6 1611.21   671.4 1613.86   770.3 1631.11   859.3 1660.28
   869.2 1661.98   908.8 1664.14   918.7 1666.89   968.1 1685.58   997.8  1693.9
  1017.6 1696.72  1047.2 1697.68    1067  1700.4  1086.8 1708.99  1106.5 1720.39
#Mann= 3 , 0 , 0
       0      .1       0   535.4    .045       0   550.4      .1       0
Bank Sta=535.4,550.4
XS Rating Curve= 0 ,0
Exp/Cntr=0.3,0.1

Type RM Length L Ch R = 1 ,14092.2 ,331.7,348.1,364.4
XS GIS Cut Line= 4
     1965627.719      311339.913     1965668.227      311817.292
     1965729.642      312012.068     1965847.498      312434.987
#Sta/Elev= 30
       0 1821.55    99.8  1759.6   159.7 1725.54   219.6 1694.36   239.6 1688.69
   289.4  1683.6   319.4  1678.6   339.4 1673.44   349.3 1668.94   409.2 1630.78
   479.1 1594.38     518 1570.89   537.4 1564.39   568.9 1562.09   576.4 1561.94
   583.9 1562.39   634.7 1567.98   673.6 1569.84   683.3 1572.06   723.2 1588.81
   753.2 1603.97     823 1631.39   862.9  1643.3   892.9 1654.52   922.8 1659.61
   932.8  1664.1   962.7 1682.06   972.7 1686.08  1022.6 1700.67  1122.4 1742.78
#Mann= 3 , 0 , 0
       0      .1       0   568.9    .045       0   583.9      .1       0
Bank Sta=568.9,583.9
XS Rating Curve= 0 ,0
Exp/Cntr=0.3,0.1

Type RM Length L Ch R = 1 ,13744.1 ,242.5,248.6,254.8
XS GIS Cut Line= 4
     1965548.714      311353.279     1965471.697      311775.179
     1965345.356        312061.2     1965240.072      312317.391
#Sta/Elev= 30
       0 1781.08    49.9 1745.94    69.8 1732.77    99.7 1715.21   129.7 1698.78
   139.6 1694.75   149.6 1692.67   209.4 1686.23   229.4 1682.18   239.4 1677.55
   309.2 1639.92     379 1603.45   418.9 1585.08     468 1564.93   477.7 1561.84
   487.5 1559.89   497.3 1559.06   604.8 1553.97   671.4 1556.78   686.4 1557.46
   692.7 1557.99   702.5 1560.42   712.2 1564.72   771.2 1596.86     791 1606.23
   820.7 1615.84   909.7  1640.6   919.6 1644.81   969.1 1670.12  1018.5 1690.54
#Mann= 3 , 0 , 0
       0      .1       0   671.4    .045       0   686.4      .1       0
Bank Sta=671.4,686.4
XS Rating Curve= 0 ,0
Exp/Cntr=0.3,0.1

Type RM Length L Ch R = 1 ,13495.5 ,346,323.9,301.9
XS GIS Cut Line= 4
     1965475.212      311323.299     1965304.997       311701.48
     1965141.807       311898.01     1964947.624      312369.249
#Sta/Elev= 30
       0 1777.34    39.5 1750.46    88.9 1714.58   108.6 1701.97   128.4 1695.12
   197.5 1681.88   207.4 1678.38   325.8 1610.78   444.2 1552.59   463.8 1549.28
   571.9 1544.43   594.9 1545.66   609.9 1547.37   650.5 1550.77   660.4 1552.72
   670.2 1556.66   720.1 1593.05   740.1 1603.93     900 1627.21     940 1644.46
     980 1663.88    1010 1675.73    1030 1680.58  1069.9 1686.17  1079.9 1689.52
  1089.9 1695.96  1109.9 1716.81  1119.9 1725.16  1149.9 1742.12  1179.8 1761.21
#Mann= 3 , 0 , 0
       0      .1       0   594.9    .045       0   609.9      .1       0
Bank Sta=594.9,609.9
XS Rating Curve= 0 ,0
Exp/Cntr=0.3,0.1

Type RM Length L Ch R = 1 ,13171.5 ,268.7,269.4,270.2
XS GIS Cut Line= 4
     1964894.732      311156.973     1964943.523      311640.065
     1965003.184      311852.387     1965010.203      312099.804
#Sta/Elev= 30
       0 1748.58     9.9 1739.79    19.8 1732.47    29.7 1727.39    39.6  1724.2
    59.5 1720.66     109 1716.62   128.8 1712.42   138.7 1708.55   148.6 1702.42
   168.5 1684.22   178.4 1676.89   267.6 1631.84   426.1 1562.03   455.8 1552.98
   475.6 1543.96   504.7 1538.63   516.6 1535.44   531.6 1532.42   533.5  1532.2
   677.3 1543.92   696.5 1546.77   706.1 1550.35     716 1555.58   775.4 1590.32
   795.2 1600.03   805.1 1602.77   824.9 1606.06   933.8 1622.22   953.6 1627.98
#Mann= 3 , 0 , 0
       0      .1       0   516.6    .045       0   531.6      .1       0
Bank Sta=516.6,531.6
XS Rating Curve= 0 ,0
Exp/Cntr=0.3,0.1

Type RM Length L Ch R = 1 ,12902.3 ,292,299.8,316.3
XS GIS Cut Line= 3
     1964583.634      311258.289      1964720.19      311809.298
     1964838.239      312298.089
#Sta/Elev= 30
       0 1684.39    29.9 1672.98    39.8 1670.14    69.7 1664.52    99.6 1662.32
   119.5 1656.85   159.4 1642.32   229.1 1613.18   268.9 1599.89   438.2 1559.97
   527.8 1535.24   560.2 1524.51   575.2 1521.91   577.5 1521.72   587.4 1522.74
   636.7 1535.19   646.6 1539.65   725.4 1583.71   735.3 1588.04   794.4 1608.62
   814.2    1617     893 1659.91   922.6 1674.62   932.5 1677.25   942.4 1678.27
   981.8 1679.17  1021.2 1682.32  1031.1 1684.77  1040.9 1689.88  1070.5 1710.74
#Mann= 3 , 0 , 0
       0      .1       0   560.2    .045       0   575.2      .1       0
Bank Sta=560.2,575.2
XS Rating Curve= 0 ,0
Exp/Cntr=0.3,0.1

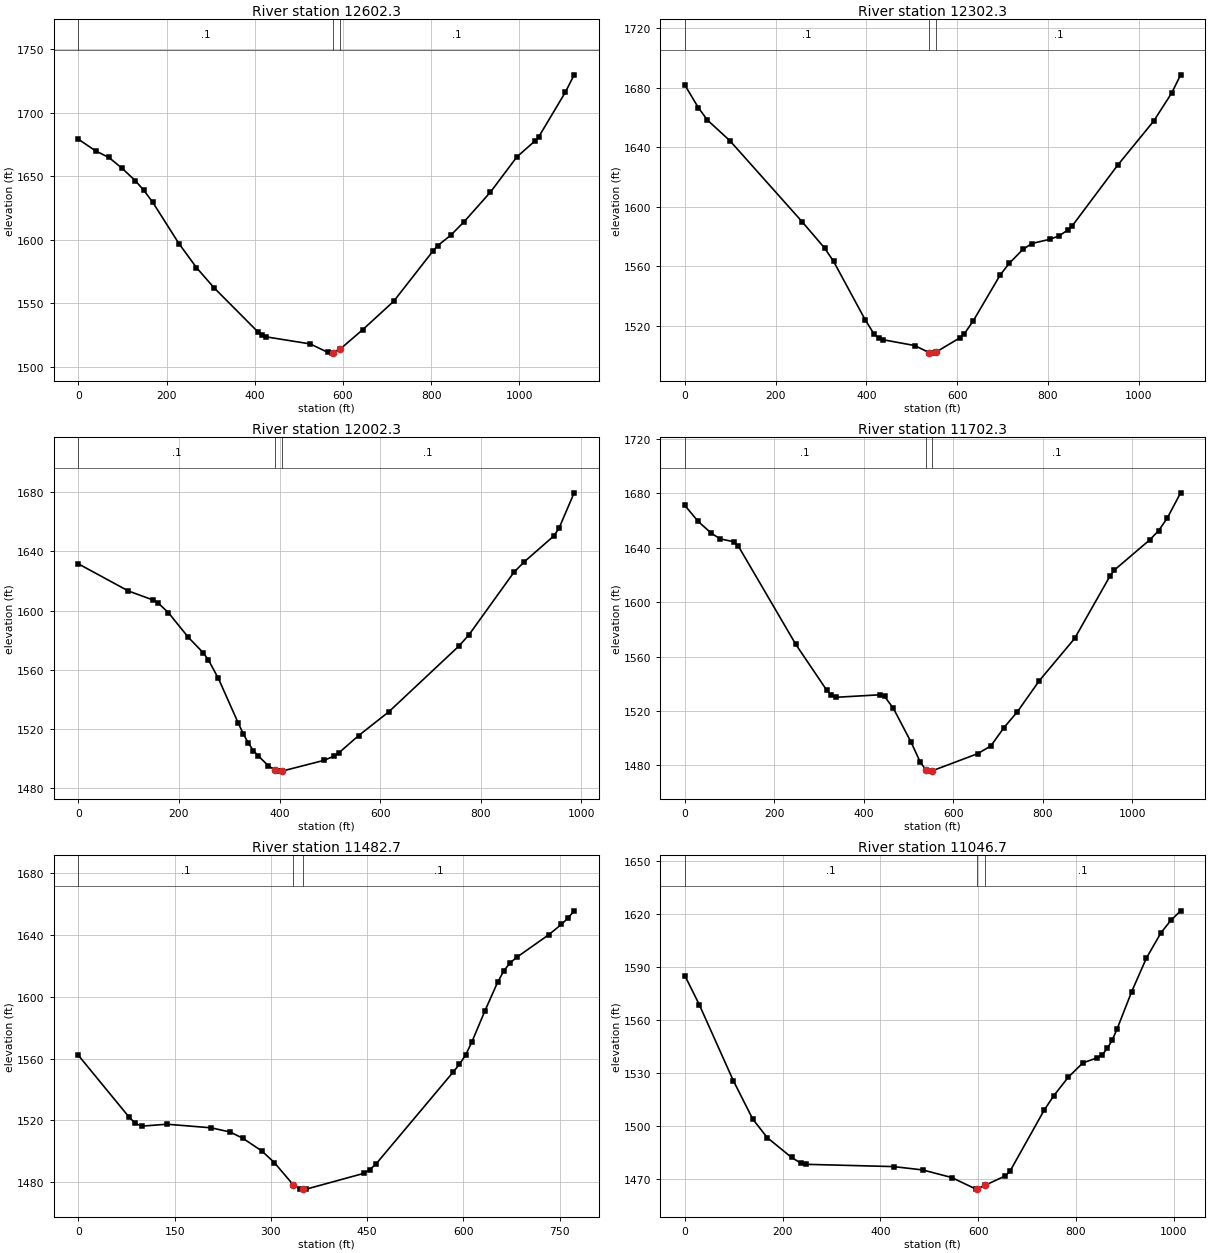
Type RM Length L Ch R = 1 ,12602.3 ,295.3,299.9,295.7
XS GIS Cut Line= 3
     1964498.659      311263.973     1964432.926      311845.604
     1964178.866      312320.918
#Sta/Elev= 30
       0 1679.13    39.7 1669.83    69.4 1664.74    99.2 1656.26     129 1646.56
   148.8 1638.82   168.7  1629.5   228.2 1596.98   267.9 1578.13   307.6  1562.3
   406.8 1527.71   416.7 1525.02   426.6 1523.61   525.8  1518.1   565.5 1511.48
   575.4 1510.85   577.8 1511.09   592.8 1513.76   645.2  1529.4   715.1 1551.64
   804.9 1591.51   814.9 1595.41   844.8  1603.7   874.8 1614.22   934.6 1637.56
   994.5 1665.23  1034.5 1677.48  1044.4 1681.23  1104.3 1716.07  1124.3 1729.77
#Mann= 3 , 0 , 0
       0      .1       0   577.8    .045       0   592.8      .1       0
Bank Sta=577.8,592.8
XS Rating Curve= 0 ,0
Exp/Cntr=0.3,0.1

Type RM Length L Ch R = 1 ,12302.3 ,309.1,300,290.4
XS GIS Cut Line= 3
     1964322.178      311204.286      1964159.32      311725.433
     1963996.463      312246.579
#Sta/Elev= 30
       0  1681.9    29.8 1666.62    49.6 1658.34    99.3 1644.37   258.1 1589.94
   307.8 1572.18   327.6 1563.21   397.1 1523.97     417 1514.17   426.9 1511.61
   436.8 1510.43   506.3 1506.52   538.5 1501.72     546 1501.42   553.5 1502.16
   605.6 1511.69   615.5 1514.38   635.4 1523.19   694.9 1554.16   714.8 1561.96
   744.6  1571.2   764.4  1575.2   804.1 1578.05     824 1580.29   843.8 1584.31
   853.8 1587.27     953 1627.77  1032.4 1657.48  1072.2  1676.4    1092 1688.72
#Mann= 3 , 0 , 0
       0      .1       0   538.5    .045       0   553.5      .1       0
Bank Sta=538.5,553.5
XS Rating Curve= 0 ,0
Exp/Cntr=0.3,0.1

Type RM Length L Ch R = 1 ,12002.3 ,307.3,300,295.3
XS GIS Cut Line= 3
     1963866.118      311224.193     1963881.244       311621.62
     1963911.741      312208.597
#Sta/Elev= 30
       0 1631.56    99.4 1613.22   149.1 1607.03   159.1 1604.89     179 1598.56
   218.7 1581.84   248.6 1571.32   258.5 1566.54   278.4 1554.07   318.2  1523.6
   328.1 1516.48   338.1 1510.23     348 1505.26   357.9 1501.56   377.8    1495
   390.2 1492.19   397.7 1491.39   405.2 1491.44   487.4 1498.59   507.3 1501.36
   517.3 1503.61   557.1 1515.42   616.9 1531.44   756.4 1575.95   776.3 1583.51
   865.9 1625.91   885.9 1632.79   945.6 1650.57   955.6 1655.82   985.5 1679.58
#Mann= 3 , 0 , 0
       0      .1       0   390.2    .045       0   405.2      .1       0
Bank Sta=390.2,405.2
XS Rating Curve= 0 ,0
Exp/Cntr=0.3,0.1

Type RM Length L Ch R = 1 ,11702.3 ,218.5,219.6,218.5
XS GIS Cut Line= 3
     1963374.435      311195.805     1963597.121      311693.905
     1963777.834      312226.528
#Sta/Elev= 30
       0 1671.09    29.8 1659.36    59.5 1650.56    79.4 1646.48   109.1 1644.41
     119 1641.54     248 1568.98   317.4 1535.16   327.4 1531.65   337.3 1530.04
   436.5 1531.91   446.4 1530.73   466.2  1521.9   505.9 1496.94   525.8 1482.68
   538.1 1476.96   545.6 1475.79   553.1 1476.03   654.2 1488.58   683.8 1494.25
   713.4 1507.82     743 1519.29   792.3 1542.28   871.2 1573.29   950.2 1619.15
     960 1623.58    1039 1645.72  1058.7 1652.42  1078.5 1661.92  1108.1 1680.34
#Mann= 3 , 0 , 0
       0      .1       0   538.1    .045       0   553.1      .1       0
Bank Sta=538.1,553.1
XS Rating Curve= 0 ,0
Exp/Cntr=0.3,0.1

Type RM Length L Ch R = 1 ,11482.7 ,414.9,436,457.1
XS GIS Cut Line= 3
     1963372.178      311468.135     1963399.363       311782.27
     1963565.492      312208.165
#Sta/Elev= 30
       0 1562.21    78.8 1522.28    88.7 1518.13    98.5 1516.28     138 1517.54
   206.9 1515.21   236.5 1512.49   256.2 1508.46   285.8 1500.23   305.5 1492.63
   334.4 1478.46   345.1 1475.71   349.4 1475.61   355.1 1475.48   444.5 1485.66
   454.4 1488.19   464.4 1492.08   583.6 1551.14   593.6 1556.26   603.5 1562.44
   613.4 1571.11   633.3 1590.82   653.2 1609.49   663.1 1617.07   673.1 1622.24
     683 1625.68   732.7 1640.26   752.6    1647   762.5 1650.92   772.5 1655.81
#Mann= 3 , 0 , 0
       0      .1       0   334.4    .045       0   349.4      .1       0
Bank Sta=334.4,349.4
XS Rating Curve= 0 ,0
Exp/Cntr=0.3,0.1

Type RM Length L Ch R = 1 ,11046.7 ,277.1,287.6,298.2
XS GIS Cut Line= 3
     1963335.932      311419.806     1962907.017      312111.508
     1962958.366      312304.821
#Sta/Elev= 30
       0 1584.94    29.8 1568.33    99.2 1525.42     139 1503.64   168.7 1493.13
   218.4 1481.91   238.2 1478.55   248.1 1478.04   426.8 1476.75   486.4 1474.86
   545.9 1470.55   595.5 1463.99     598 1464.22     613 1466.05   655.1 1471.44
     665 1474.13   734.5 1508.53   754.3 1516.83   784.1 1527.34   813.9 1535.45
   843.9 1538.43   853.9  1540.2   863.9 1543.63   873.9  1548.3   883.9 1554.64
   913.9 1575.88   943.9  1594.8   973.9 1609.22   993.9 1616.18  1013.9 1621.58
#Mann= 3 , 0 , 0
       0      .1       0     598    .045       0     613      .1       0
Bank Sta=598,613
XS Rating Curve= 0 ,0
Exp/Cntr=0.3,0.1

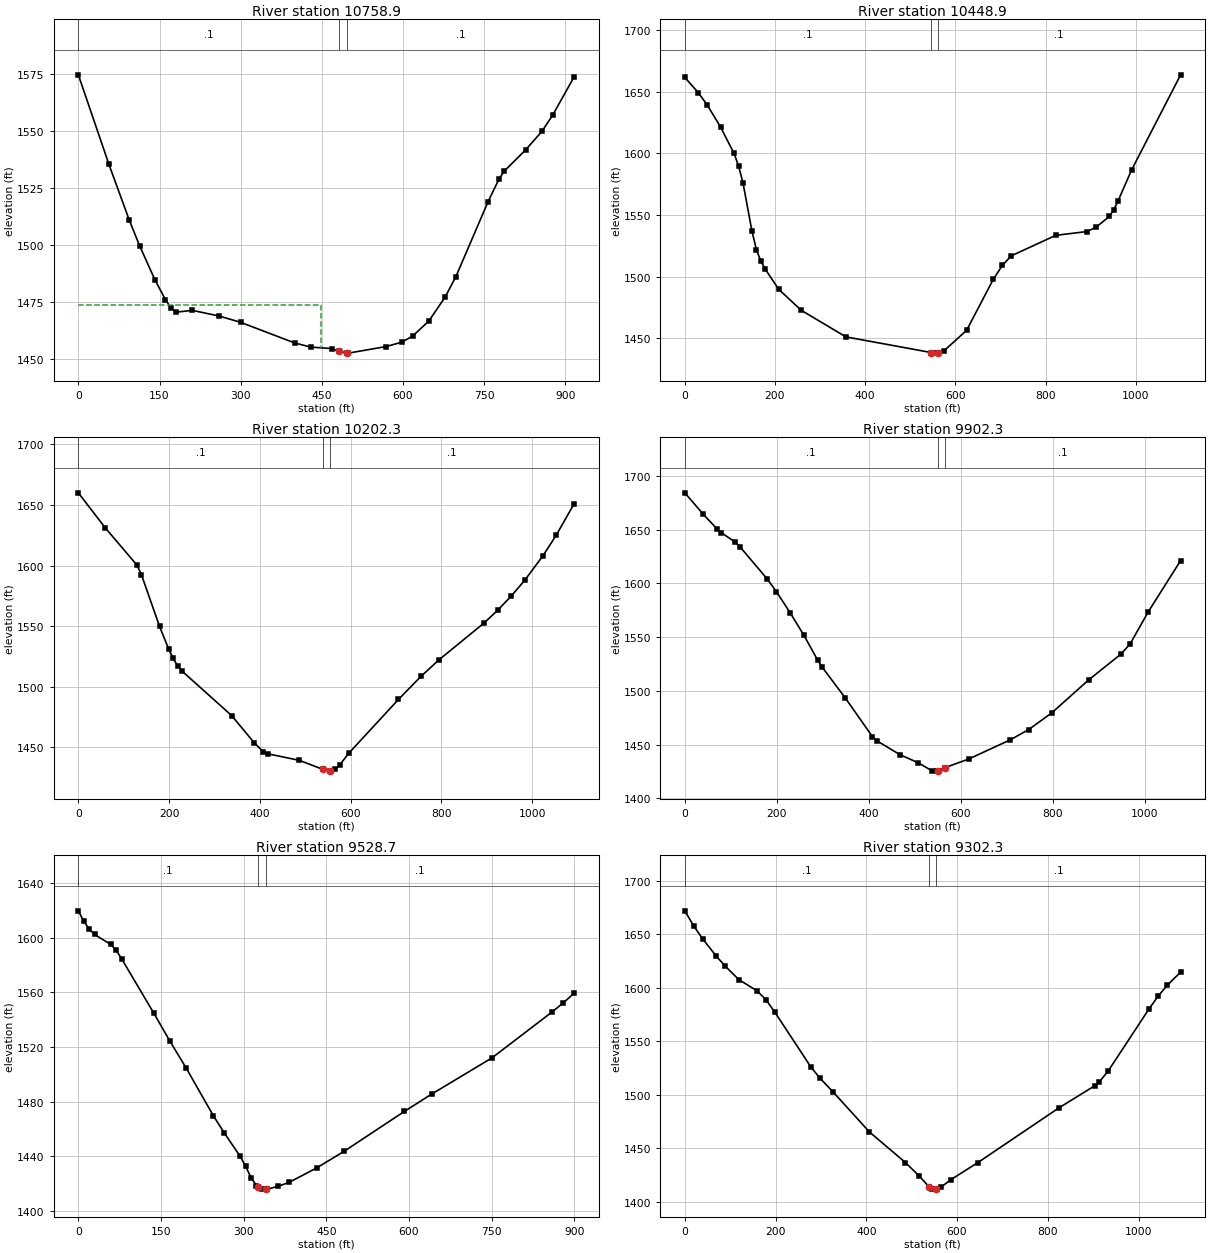
Type RM Length L Ch R = 1 ,10758.9 ,312,310,310.7
XS GIS Cut Line= 3
     1963254.378      311392.622     1963163.762      311513.443
     1962514.348      311918.194
#Sta/Elev= 30
       0 1574.79    56.6 1535.39    94.4 1510.78   113.3 1499.64   141.6 1484.67
     161    1476   170.9 1472.41   180.8  1470.5   210.6 1471.28   260.3 1468.79
   300.1 1466.01   399.5 1456.98   429.3 1455.15     469 1454.48     482 1453.21
     497 1452.52   498.8 1452.49   568.4 1455.36   598.2 1457.33   618.1 1460.06
   647.9 1466.65   677.7 1477.11   697.6 1486.07   757.2 1519.08   777.1 1528.88
     787 1532.46   826.8 1541.88   856.6 1549.94   876.5 1557.07   916.2 1573.94
#Mann= 3 , 0 , 0
       0      .1       0     482    .045       0     497      .1       0
#XS Ineff= 2 , 0
          448.28 1473.82
Permanent Ineff=
       F       F
Bank Sta=482,497
XS Rating Curve= 0 ,0
Exp/Cntr=0.3,0.1

Type RM Length L Ch R = 1 ,10448.9 ,242.5,246.6,249.2
XS GIS Cut Line= 3
     1963102.659      311138.874     1962658.863      311473.365
     1962185.086      311740.084
#Sta/Elev= 30
       0 1661.42    29.8 1649.14    49.6 1639.17    79.4 1621.12   109.2 1599.77
   119.1 1589.76     129 1575.96   148.9 1536.88   158.8 1521.74   168.7  1512.4
   178.6 1505.82   208.4 1489.59     258 1472.66   357.3 1451.06   546.1 1438.39
   555.7 1437.89   561.1 1437.99   575.5 1439.99   624.9 1456.41   684.2 1497.85
     704 1508.99   723.8 1516.75   822.6 1533.38   891.8 1536.46   911.6  1539.9
   941.3 1548.66   951.2 1554.14     961 1561.59   990.7 1586.42  1099.4 1663.52
#Mann= 3 , 0 , 0
       0      .1       0   546.1    .045       0   561.1      .1       0
Bank Sta=546.1,561.1
XS Rating Curve= 0 ,0
Exp/Cntr=0.3,0.1

Type RM Length L Ch R = 1 ,10202.3 ,293,300,305.8
XS GIS Cut Line= 3
     1963024.507      311016.604     1962536.103      311261.906
      1962034.39      311477.388
#Sta/Elev= 30
       0 1660.09    59.6 1631.06   129.2 1600.42   139.1 1592.44   178.9 1549.89
   198.7 1531.52   208.7 1523.57   218.6 1517.27   228.6 1512.92   337.9  1476.2
   387.6 1453.75   407.4 1446.41   417.4 1444.66   486.9 1439.28     539 1431.79
     554 1430.46   556.5 1430.36   566.4 1431.75   576.3 1435.64   596.2 1445.24
   705.4 1489.53     755 1508.56   794.7 1522.23     894 1552.62   923.8 1563.06
   953.6 1574.73   983.4 1587.77  1023.1 1607.75  1052.9 1624.96  1092.6 1651.15
#Mann= 3 , 0 , 0
       0      .1       0     539    .045       0     554      .1       0
Bank Sta=539,554
XS Rating Curve= 0 ,0
Exp/Cntr=0.3,0.1

Type RM Length L Ch R = 1 ,9902.3  ,379.3,373.4,367.6
XS GIS Cut Line= 3
     1962981.116      310894.198     1962431.022      310981.794
     1961916.612      311061.003
#Sta/Elev= 30
       0 1684.13    39.8 1664.36    69.6 1650.78    79.6    1647   109.4 1638.32
   119.4  1634.2     179 1604.05   198.9 1592.34   228.8 1572.69   258.6 1551.85
   288.5 1528.75   298.4 1522.09   348.1 1493.76   407.8 1457.39   417.8  1453.4
   467.5 1440.65   507.3 1433.06   537.1 1425.68   547.1 1425.32   549.5 1425.62
   564.5 1428.43   617.1  1436.6   707.2 1454.39   747.2 1463.96   797.2 1479.39
   877.3 1510.02   947.4 1534.03   967.4 1543.39  1007.4 1573.63  1077.5 1621.11
#Mann= 3 , 0 , 0
       0      .1       0   549.5    .045       0   564.5      .1       0
Bank Sta=549.5,564.5
XS Rating Curve= 0 ,0
Exp/Cntr=0.3,0.1

Type RM Length L Ch R = 1 ,9528.7  ,230.8,226.7,223.1
XS GIS Cut Line= 3
     1962690.448      310497.735      1962386.88      310634.604
      1961867.48      310860.964
#Sta/Elev= 30
       0 1619.71     9.8 1612.18    19.6  1606.3    29.4 1602.37    58.8 1595.11
    68.6 1590.86    78.4 1584.68   137.1 1544.62   166.5 1524.01   195.9 1504.37
   244.8 1469.73   264.4 1457.27   293.8 1439.76   303.6 1432.43   313.4 1424.32
   323.2 1418.42     326 1417.69     333 1415.88     341 1415.85   342.9 1415.84
   362.8 1417.94   382.7 1420.84   432.4 1431.37   482.1 1443.51   591.4 1472.72
   641.1 1485.47   750.5 1511.99   859.8 1545.69   879.7 1552.24   899.6 1559.38
#Mann= 3 , 0 , 0
       0      .1       0     326    .045       0     341      .1       0
Bank Sta=326,341
XS Rating Curve= 0 ,0
Exp/Cntr=0.3,0.1

Type RM Length L Ch R = 1 ,9302.3  ,349.2,346,341.4
XS GIS Cut Line= 3
     1962720.445      310136.729     1962268.766      310443.225
     1961805.008      310732.991
#Sta/Elev= 30
       0 1671.96    19.8  1657.7    39.7 1645.59    69.5 1629.53    89.3  1620.1
   119.1 1607.64   158.8 1597.22   178.6 1588.96   198.5 1577.14   277.9 1525.87
   297.7 1515.48   327.5 1502.24   406.9 1465.13   486.3 1436.49   516.1 1424.16
   538.4 1413.77   545.8 1411.73   553.4 1411.67   555.8 1411.65   565.7 1413.79
   585.6  1420.3   645.3 1436.31   824.2 1487.58   903.8 1508.41   913.7 1512.05
   933.6 1522.47  1023.1 1580.25    1043 1592.08  1062.9 1602.22  1092.7 1614.63
#Mann= 3 , 0 , 0
       0      .1       0   538.4    .045       0   553.4      .1       0
Bank Sta=538.4,553.4
XS Rating Curve= 0 ,0
Exp/Cntr=0.3,0.1