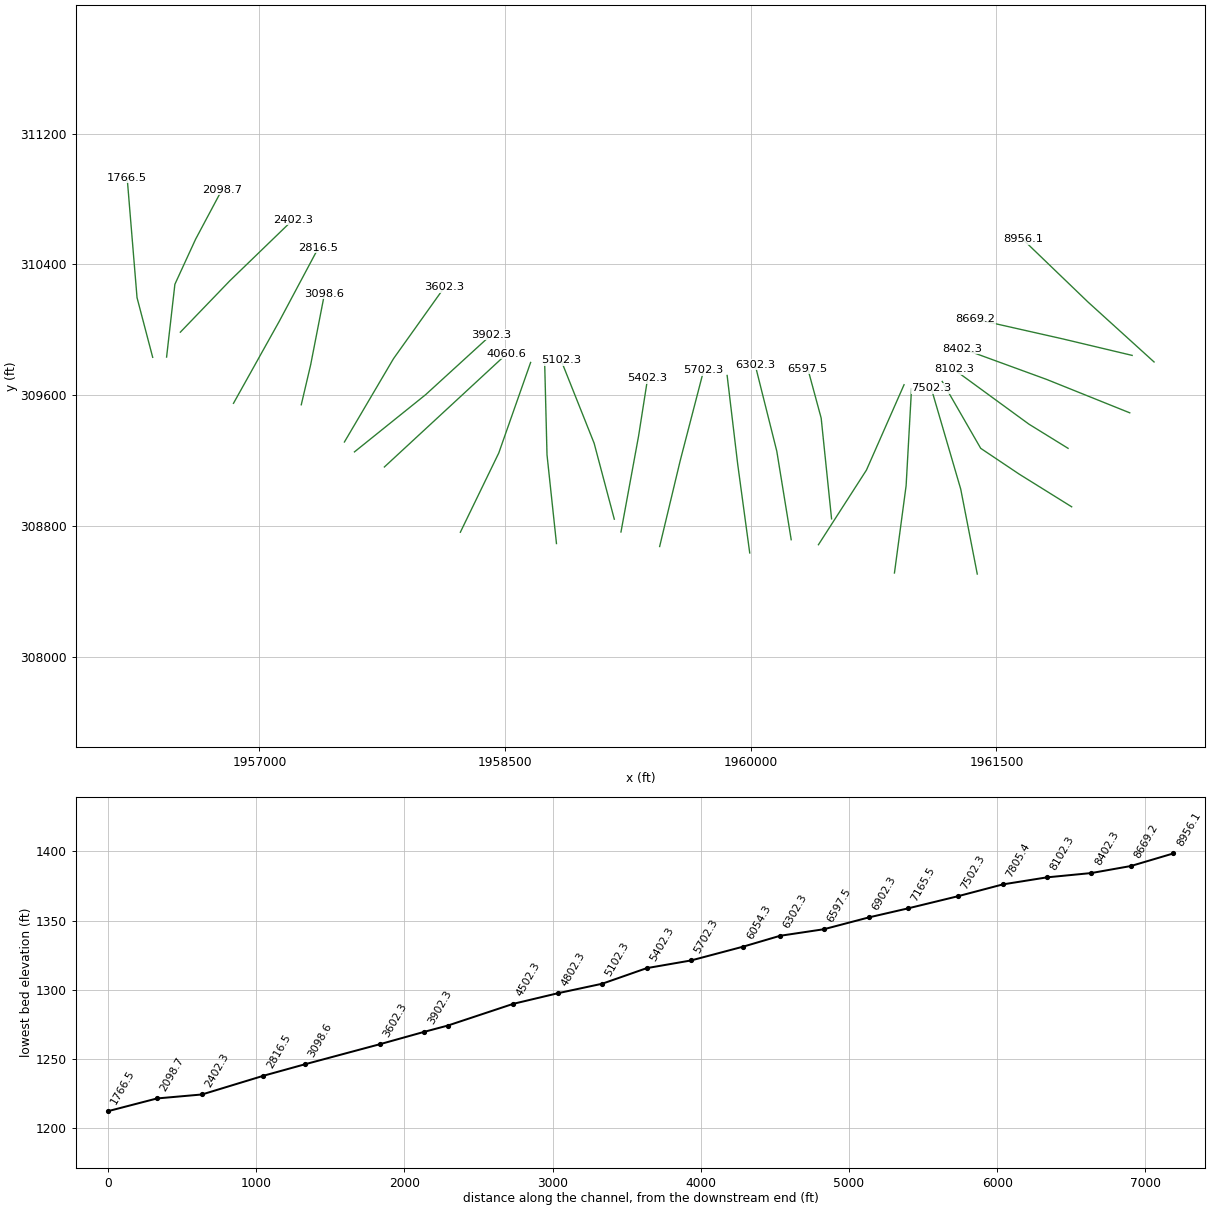
HEC-RAS study LaurelCrk.prj: LaurelCrk

--- LaurelCrk.g01 (geometry) --- (continued)

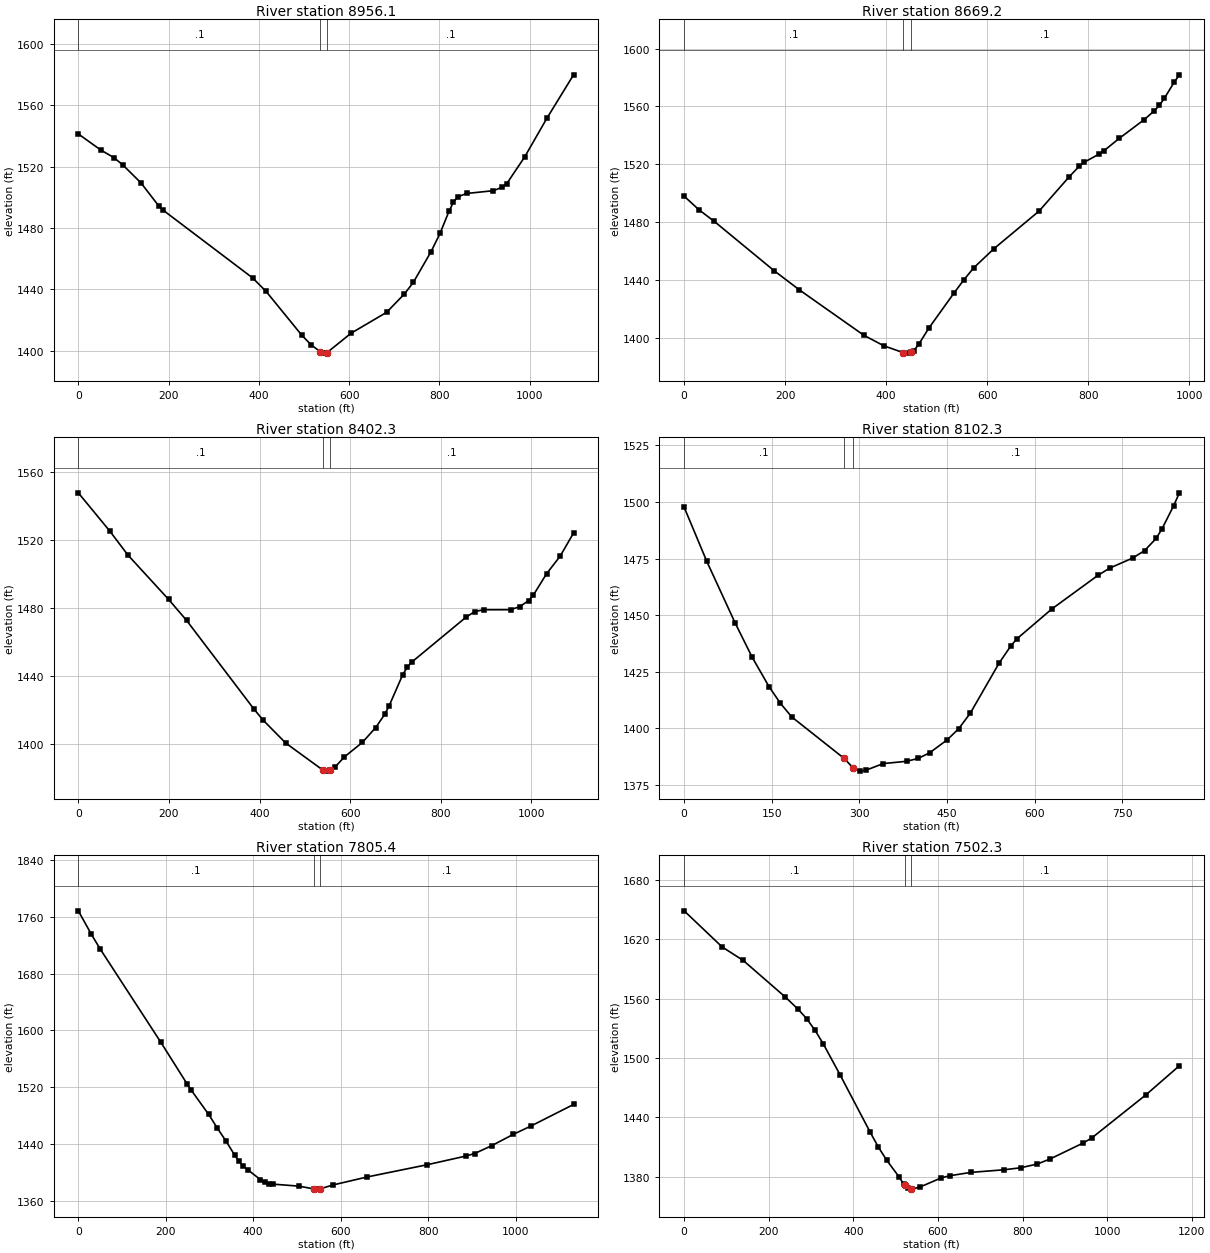
Type RM Length L Ch R = 1 ,8956.1  ,275.4,286.8,299.1
XS GIS Cut Line= 3
     1962462.854      309802.979     1962059.678      310169.505
     1961661.984      310552.827
#Sta/Elev= 30
       0 1541.33    49.5 1530.91    79.3  1525.8    99.1 1520.98   138.7 1509.46
   178.3 1494.36   188.2 1491.56   386.4 1447.42   416.1 1438.65   495.3 1410.04
   515.2 1404.03   536.1  1399.3   544.9 1398.43   551.1 1398.78   604.1 1411.38
     683 1425.02   722.4 1436.98   742.2 1444.53   781.6 1464.64   801.3 1476.45
   821.1  1490.8   830.9 1496.72   840.8 1500.37   860.5 1502.52   919.7 1504.33
   939.4 1506.64   949.3 1508.97   988.7 1526.22    1038 1551.48  1097.2 1579.86
#Mann= 3 , 0 , 0
       0      .1       0   536.1    .045       0   551.1      .1       0
Bank Sta=536.1,551.1
XS Rating Curve= 0 ,0
Exp/Cntr=0.3,0.1

Type RM Length L Ch R = 1 ,8669.2  ,270.4,266.9,264
XS GIS Cut Line= 3
     1962328.974       309843.22     1961905.829      309944.052
     1961373.416      310064.446
#Sta/Elev= 30
       0 1497.93    29.7 1488.41    59.3 1480.59     178 1446.42   227.4 1433.31
   355.9 1401.69   395.4 1394.42   434.3 1389.63   444.9 1389.34   449.3  1390.1
   454.8 1391.05   464.8 1395.59   484.6 1406.62   534.2 1430.81   554.1 1440.11
   573.9  1448.5   613.6 1461.61     703 1487.64   762.5 1511.33   782.4  1518.6
   792.3 1521.42     822 1527.08     832 1529.53   861.8 1537.95   911.4 1550.97
   931.2 1557.03   941.2 1560.79   951.1 1565.71   970.9 1576.97   980.8 1581.89
#Mann= 3 , 0 , 0
       0      .1       0   434.3    .045       0   449.3      .1       0
Bank Sta=434.3,449.3
XS Rating Curve= 0 ,0
Exp/Cntr=0.3,0.1

Type RM Length L Ch R = 1 ,8402.3  ,303.7,299.9,293.5
XS GIS Cut Line= 3
     1962314.256      309491.884     1961806.393      309696.395
      1961293.88      309883.901
#Sta/Elev= 30
       0  1547.9    69.7 1525.35   109.5 1511.31   199.1  1485.3   238.9 1472.92
   388.2 1420.57   408.1 1414.21   457.9 1400.76     540 1384.84   547.5 1384.26
     555 1384.65   567.3 1386.83   587.2 1392.58   626.9  1401.1   656.6 1409.91
   676.5 1417.72   686.4 1422.83   716.2 1441.01   726.1 1445.35     736 1448.36
   855.1 1474.61   874.9 1478.07   894.8 1479.14   954.3 1479.18   974.2 1480.97
     994 1484.52  1003.9 1487.53  1033.7 1500.34  1063.5 1510.63  1093.2 1524.26
#Mann= 3 , 0 , 0
       0      .1       0     540    .045       0     555      .1       0
Bank Sta=540,555
XS Rating Curve= 0 ,0
Exp/Cntr=0.3,0.1

Type RM Length L Ch R = 1 ,8102.3  ,298.1,297,297.7
XS GIS Cut Line= 3
     1961937.669      309274.687     1961698.492      309422.738
     1961241.333      309757.047
#Sta/Elev= 30
       0 1497.67    38.8 1473.74    87.3 1446.55   116.4 1431.44   145.5 1418.35
   164.9 1411.04   184.3 1405.04   273.8 1386.76   288.8 1382.69   301.2 1381.14
   311.1 1381.54   340.9 1384.48   380.6 1385.48   400.5 1386.74   420.4 1389.27
   450.2 1394.96   470.1 1399.92     490 1406.84   539.6 1429.07   559.5 1436.54
   569.4 1439.53     629 1452.68   708.5 1467.64   728.4 1470.78   768.2  1475.3
     788 1478.51   807.9  1483.9   817.8  1488.1   837.7 1498.28   847.6 1504.02
#Mann= 3 , 0 , 0
       0      .1       0   273.8    .045       0   288.8      .1       0
Bank Sta=273.8,288.8
XS Rating Curve= 0 ,0
Exp/Cntr=0.3,0.1

Type RM Length L Ch R = 1 ,7805.4  ,320.7,303,287.3
XS GIS Cut Line= 4
      1961959.71      308916.923     1961639.365      309116.762
     1961404.231      309274.687     1961169.241      309683.881
#Sta/Elev= 30
       0 1768.44    29.8 1735.43    49.7 1714.94   188.8 1583.07   248.4 1524.82
   258.3  1515.6   298.1 1481.46     318 1462.07   337.8 1443.79   357.7 1423.99
   367.6 1415.07   377.6 1408.45   387.3 1403.47   416.6 1389.43   426.4  1385.8
   436.2 1383.99   445.9 1383.07   504.5 1380.28   538.7 1376.38   543.6 1376.07
   553.7  1376.6   582.7 1381.96   660.8 1393.25   798.4 1410.52   886.9 1422.77
   906.6 1426.27   945.9 1437.48     995 1453.34  1034.4 1464.78  1132.7 1495.43
#Mann= 3 , 0 , 0
       0      .1       0   538.7    .045       0   553.7      .1       0
Bank Sta=538.7,553.7
XS Rating Curve= 0 ,0
Exp/Cntr=0.3,0.1

Type RM Length L Ch R = 1 ,7502.3  ,343.9,336.8,329.1
XS GIS Cut Line= 3
     1961383.303      308505.621     1961282.319      309024.979
     1961102.521      309641.137
#Sta/Elev= 30
       0 1648.67    89.8  1612.2   139.8  1598.5   239.6 1561.43   269.5 1549.25
   289.5 1539.83   309.5 1527.97   329.4 1513.97   369.4 1482.39   439.2 1425.56
   459.2    1410   479.2 1396.54   509.1 1379.38   519.1 1372.23   521.6 1371.24
   529.1 1368.27   536.6 1367.71     539 1367.53   558.7 1369.84   608.1 1378.94
   627.8 1381.02   677.2 1384.41   756.2 1387.08   795.7  1389.1   835.2 1392.92
   864.8  1397.9   943.8 1414.21   963.6 1419.17  1091.9 1462.82  1170.9 1492.16
#Mann= 3 , 0 , 0
       0      .1       0   521.6    .045       0   536.6      .1       0
Bank Sta=521.6,536.6
XS Rating Curve= 0 ,0
Exp/Cntr=0.3,0.1

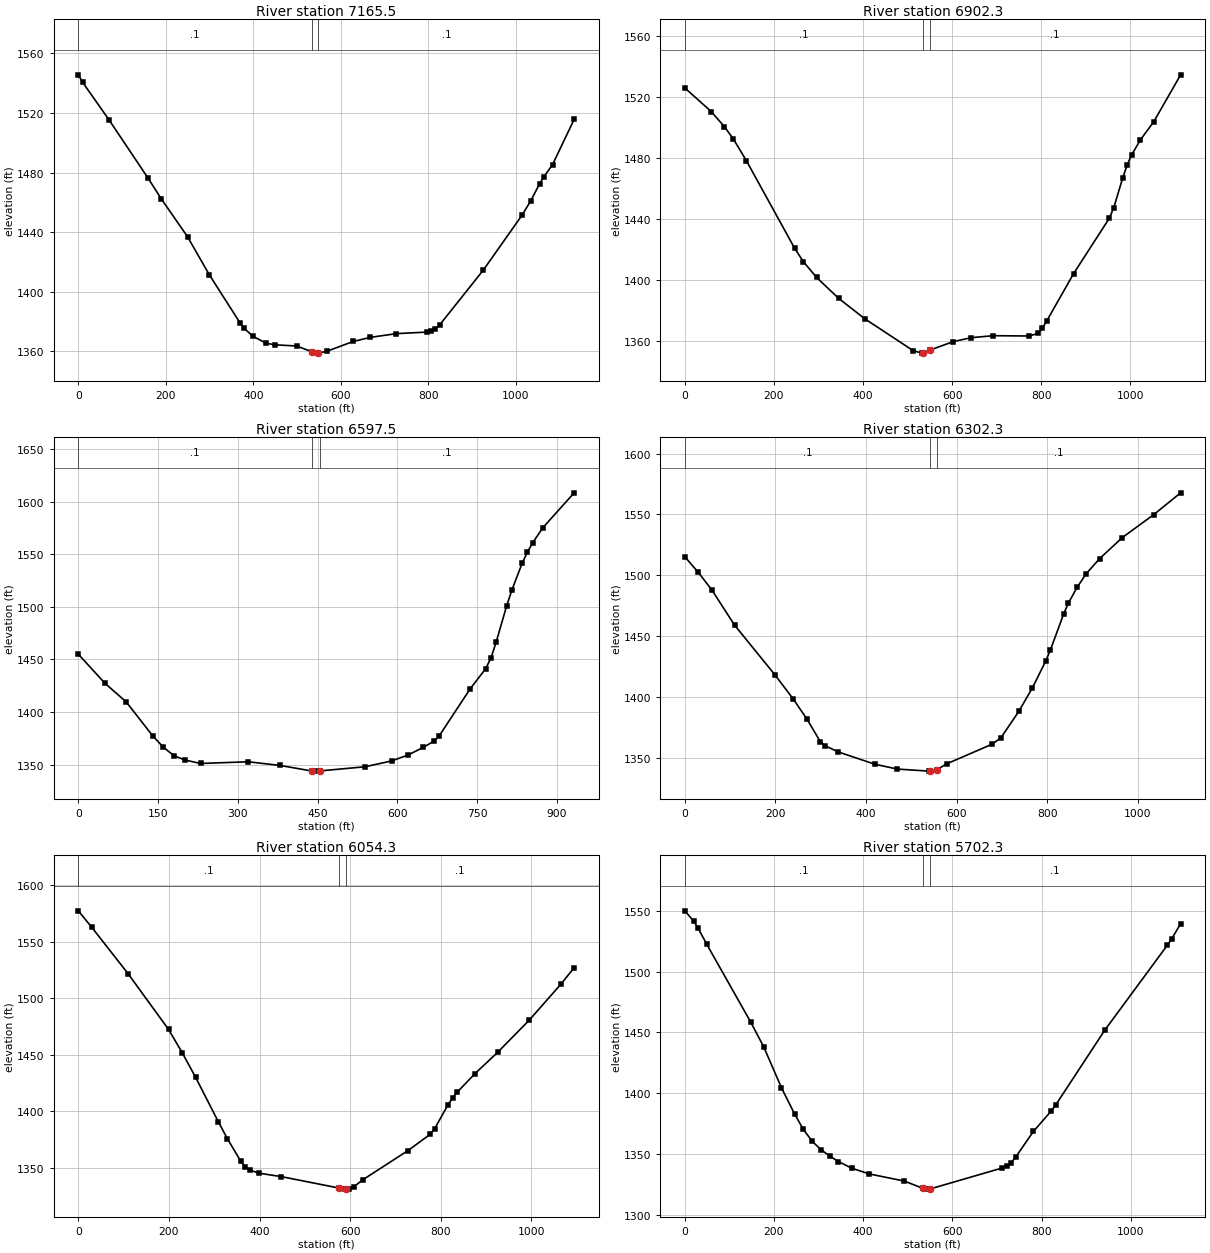
Type RM Length L Ch R = 1 ,7165.5  ,273.4,263.6,255.5
XS GIS Cut Line= 3
     1960877.612      308511.997     1960948.841      309046.166
     1960981.883      309639.553
#Sta/Elev= 30
       0 1545.64      10 1540.55    69.9  1515.5   159.7 1476.12   189.6 1462.36
   249.5 1436.96   299.4 1411.36   369.2 1379.25   379.2 1375.37   399.2 1370.07
   429.1 1365.44   449.1 1364.35     499 1363.56   533.8 1359.69   548.8 1358.77
   568.6 1360.07     628 1366.58   667.7 1369.37   727.1 1371.86   796.4 1372.89
   806.3 1373.38   816.2 1374.99   826.2 1377.87   925.2 1414.38  1014.3 1451.49
  1034.2 1461.16    1054 1472.38  1063.9 1477.15  1083.7 1485.27  1133.2 1515.75
#Mann= 3 , 0 , 0
       0      .1       0   533.8    .045       0   548.8      .1       0
Bank Sta=533.8,548.8
XS Rating Curve= 0 ,0
Exp/Cntr=0.3,0.1

Type RM Length L Ch R = 1 ,6902.3  ,289.1,304.4,316.4
XS GIS Cut Line= 3
     1960413.526      308684.959     1960706.541      309141.486
     1960936.217      309663.697
#Sta/Elev= 30
       0 1526.15    59.2 1510.67    88.8 1500.74   108.5 1492.92   138.1 1478.51
   246.6 1420.97   266.3 1412.17   295.9 1401.87   345.2  1388.2   404.4  1374.7
   512.9 1353.84   532.6 1352.26     535 1352.48     550  1354.2   602.5  1359.8
   642.6 1362.37   692.6  1363.7   772.7 1363.48   792.7 1365.15   802.7 1368.66
   812.7 1373.49   872.8 1404.42   952.8 1440.63   962.8  1447.5   982.8 1466.93
   992.9 1475.52  1002.9 1482.18  1022.9 1492.15  1052.9 1504.09    1113 1534.73
#Mann= 3 , 0 , 0
       0      .1       0     535    .045       0     550      .1       0
Bank Sta=535,550
XS Rating Curve= 0 ,0
Exp/Cntr=0.3,0.1

Type RM Length L Ch R = 1 ,6597.5  ,294.1,295.1,298
XS GIS Cut Line= 3
     1960493.614      308843.295     1960430.183      309459.483
     1960348.629      309761.536
#Sta/Elev= 30
       0 1454.85      50 1427.24    89.9 1409.56   139.9 1377.23   159.9 1366.41
   179.8 1358.39   199.8 1354.34   229.8 1350.98   319.7 1352.59   379.7 1349.06
   439.4  1343.8   449.6  1343.7   454.4  1343.9   539.5 1347.87   589.5 1353.46
   619.4  1358.9   648.8  1366.3   668.3 1372.05   678.1 1376.87   736.8 1421.94
   766.1 1441.21   775.9 1451.34   785.7  1466.4   805.2 1500.55     815 1515.53
   834.5 1541.39   844.3  1551.8   854.1 1560.66   873.6  1575.2   932.3 1608.27
#Mann= 3 , 0 , 0
       0      .1       0   439.4    .045       0   454.4      .1       0
Bank Sta=439.4,454.4
XS Rating Curve= 0 ,0
Exp/Cntr=0.3,0.1

Type RM Length L Ch R = 1 ,6302.3  ,249,248,245.2
XS GIS Cut Line= 3
     1960247.122      308715.665     1960159.191      309257.096
     1960026.873      309786.361
#Sta/Elev= 30
       0 1515.21    29.9 1502.27    59.8 1487.84   109.7 1459.02   199.5 1417.83
   239.4  1398.2   269.3 1381.88   299.2 1363.12   309.2  1359.9   339.1  1354.7
   418.9 1344.71   468.7 1340.68   538.6 1338.98     541 1339.01     556 1340.12
   578.3 1345.04   677.5 1361.02   697.3 1366.22     737 1388.08   766.8 1407.22
   796.5 1429.52   806.4 1438.23   836.2 1468.38   846.1  1476.9   865.9 1490.14
   885.8 1501.28   915.5 1513.66   965.1 1530.84  1034.6 1549.75  1094.1 1567.71
#Mann= 3 , 0 , 0
       0      .1       0     541    .045       0     556      .1       0
Bank Sta=541,556
XS Rating Curve= 0 ,0
Exp/Cntr=0.3,0.1

Type RM Length L Ch R = 1 ,6054.3  ,359.9,351.9,343.5
XS GIS Cut Line= 3
     1959993.948      308634.601     1959920.473      309177.654
     1959855.932      309720.505
#Sta/Elev= 30
       0 1577.55    29.9 1562.85   109.6 1522.02   199.3 1472.49   229.2 1452.06
   259.1 1430.03   308.9 1390.98   328.8 1375.98   358.7 1355.83   368.7 1350.78
   378.6 1348.01   398.6  1345.3   448.4 1342.22   575.1 1332.16   587.8 1331.17
   590.1 1331.21   597.7 1331.33   607.6 1332.99   627.5 1339.31   726.9 1365.04
   776.6 1379.65   786.6  1384.6   816.4 1406.02   826.3 1412.12   836.2 1416.89
     876 1433.53   925.7 1452.25   995.3 1480.67  1064.9 1512.38  1094.7 1527.23
#Mann= 3 , 0 , 0
       0      .1       0   575.1    .045       0   590.1      .1       0
Bank Sta=575.1,590.1
XS Rating Curve= 0 ,0
Exp/Cntr=0.3,0.1

Type RM Length L Ch R = 1 ,5702.3  ,297,300,302.9
XS GIS Cut Line= 3
     1959443.896      308674.021     1959569.815      309200.765
     1959712.862      309752.734
#Sta/Elev= 30
       0 1550.04    19.7 1541.65    29.5 1535.96    49.2 1522.56   147.7  1458.6
   177.2 1438.02   216.6 1404.67   246.2 1382.96   265.9 1370.24   285.6 1360.54
   305.3 1353.63     325 1348.38   344.6 1343.84   374.2 1338.42   413.6 1333.69
   492.4  1327.8   534.1 1321.79   541.6 1321.19   549.1 1321.24   711.6 1338.56
   721.6 1339.85   731.6 1342.77   741.7 1347.44   781.7 1368.64   821.7 1385.44
   831.7 1390.41   941.7 1451.89  1081.8 1521.64  1091.8 1527.07  1111.8 1539.39
#Mann= 3 , 0 , 0
       0      .1       0   534.1    .045       0   549.1      .1       0
Bank Sta=534.1,549.1
XS Rating Curve= 0 ,0
Exp/Cntr=0.3,0.1

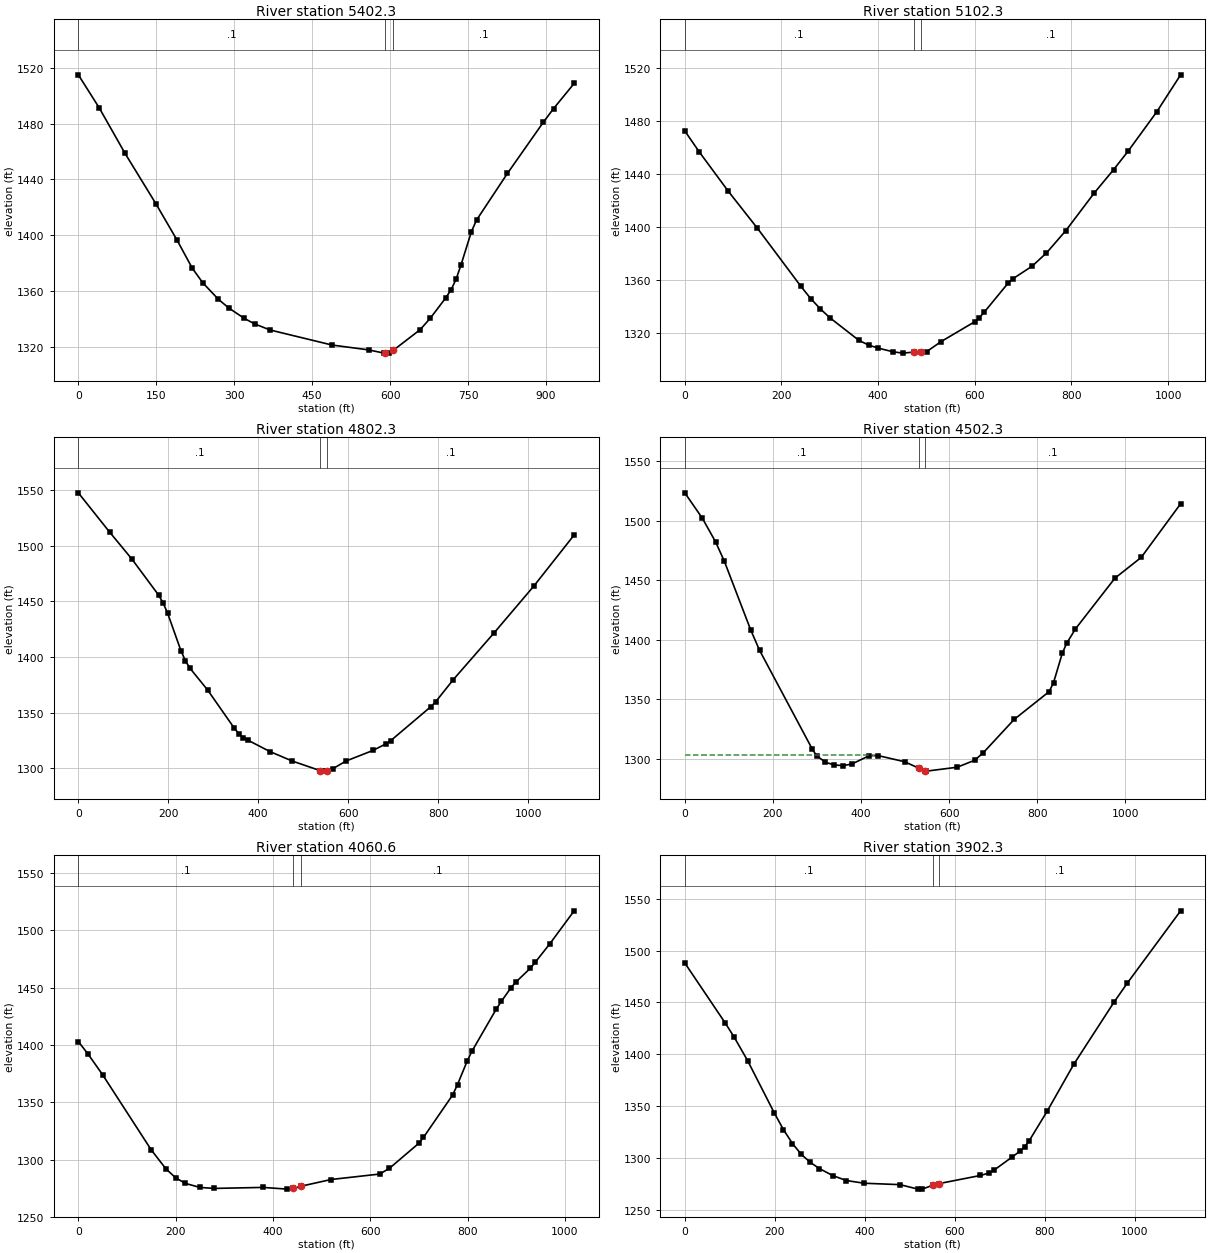
Type RM Length L Ch R = 1 ,5402.3  ,291.6,299.9,311.4
XS GIS Cut Line= 3
     1959207.734      308762.805       1959315.5      309351.299
     1959370.498      309702.842
#Sta/Elev= 30
       0 1514.96    39.9 1491.49    89.7  1458.8   149.6 1422.41   189.5 1396.86
   219.4 1376.37   239.3 1366.09   269.2 1354.27   289.2 1348.05   319.1 1340.55
     339  1336.6   368.9  1332.2   488.6 1321.38   558.4 1317.96   588.3 1315.62
   590.8 1315.71   598.3 1315.98   605.8 1317.57   657.6 1332.38   677.4 1340.68
     707 1355.22   716.9 1360.76   726.8 1368.44   736.6 1379.07   756.4 1402.68
   766.3 1410.97   825.6  1444.3   894.8 1481.01   914.6 1490.83   954.1 1508.82
#Mann= 3 , 0 , 0
       0      .1       0   590.8    .045       0   605.8      .1       0
Bank Sta=590.8,605.8
XS Rating Curve= 0 ,0
Exp/Cntr=0.3,0.1

Type RM Length L Ch R = 1 ,5102.3  ,303.7,300,292
XS GIS Cut Line= 3
     1959166.949      308841.269     1959043.797      309306.047
     1958842.296      309812.605
#Sta/Elev= 30
       0 1472.72      30 1456.76    90.2 1426.91   150.3 1398.96   240.4  1354.9
   260.4 1345.76   280.5 1337.86   300.5  1331.1   360.6 1313.95   380.6 1310.47
   400.7 1308.12   430.7 1305.42   450.8 1304.38   473.3 1305.14   488.3 1305.04
   500.6 1305.54   530.4 1313.14   599.8 1328.13   609.7  1331.3   619.6  1335.4
   669.2 1357.47   679.1 1360.76   718.7 1370.25   748.4 1380.28   788.1 1397.04
   847.6 1425.84   887.2 1443.32     917 1457.22   976.4 1487.05    1026  1515.2
#Mann= 3 , 0 , 0
       0      .1       0   473.3    .045       0   488.3      .1       0
Bank Sta=473.3,488.3
XS Rating Curve= 0 ,0
Exp/Cntr=0.3,0.1

Type RM Length L Ch R = 1 ,4802.3  ,312.6,300,291.8
XS GIS Cut Line= 3
     1958813.909       308692.22     1958756.137       309234.65
      1958742.01      309791.479
#Sta/Elev= 30
       0 1547.44    69.4 1512.25     119    1488   178.5 1455.59   188.4 1448.62
   198.4 1439.49   228.1 1405.69     238 1396.65     248 1390.02   287.6  1370.3
   347.1 1335.88     357 1331.03     367  1327.7   376.9 1325.34   426.5 1314.97
   476.1 1306.49     538 1297.92   545.5  1297.5     553 1297.81   565.4 1299.54
   595.2 1306.57   654.9 1316.04   684.8 1322.18   694.7 1324.89   784.2 1355.51
   794.2 1359.62     834 1379.79   923.5 1421.22    1013 1463.78  1102.5 1509.58
#Mann= 3 , 0 , 0
       0      .1       0     538    .045       0     553      .1       0
Bank Sta=538,553
XS Rating Curve= 0 ,0
Exp/Cntr=0.3,0.1

Type RM Length L Ch R = 1 ,4502.3  ,450.2,441.6,430.6
XS GIS Cut Line= 3
     1958226.979      308761.295      1958461.65      309246.281
     1958656.101      309800.056
#Sta/Elev= 30
       0 1523.23    39.9  1501.9    69.8 1482.17    89.8 1465.84   149.7 1408.21
   169.6 1391.28   289.3  1308.4   299.3 1302.76   319.3  1297.3   339.2 1295.04
   359.2 1294.51   379.1 1295.81     419 1302.86     439 1302.88   498.9 1297.76
   531.3 1292.36   546.3 1290.12   548.7 1289.87   618.4 1293.14   658.2    1299
     678 1305.42   747.7 1333.19   827.3 1356.58   837.2 1364.14   857.1  1388.8
   867.1 1397.12     887 1409.15   976.5 1451.66  1036.2 1469.07  1125.7 1514.06
#Mann= 3 , 0 , 0
       0      .1       0   531.3    .045       0   546.3      .1       0
#XS Ineff= 2 , 0
          429.13 1303.43
Permanent Ineff=
       F       F
Bank Sta=531.3,546.3
XS Rating Curve= 0 ,0
Exp/Cntr=0.3,0.1

Type RM Length L Ch R = 1 ,4060.6  ,159.9,158.3,158.2
XS GIS Cut Line= 2
     1957763.164       309160.63     1958510.478      309853.149
#Sta/Elev= 30
       0 1402.96      20 1392.02    49.9 1373.99   149.8 1308.43   179.8 1291.98
   199.8 1284.13   219.8 1279.22   249.7 1275.67   279.7 1274.82   379.6 1275.69
   429.5 1274.19     442 1274.77     457 1276.69   519.4 1282.59   619.3 1287.35
   639.3 1292.37   699.2 1314.04   709.2 1319.34   769.1 1356.31   779.1 1365.41
   799.1 1386.06   809.1 1394.75     859 1431.47     869 1437.94     889 1449.87
     899 1454.82     929 1467.04   938.9 1472.17   968.9 1488.31  1018.8 1517.02
#Mann= 3 , 0 , 0
       0      .1       0     442    .045       0     457      .1       0
Bank Sta=442,457
XS Rating Curve= 0 ,0
Exp/Cntr=0.3,0.1

Type RM Length L Ch R = 1 ,3902.3  ,292,300,304.6
XS GIS Cut Line= 3
     1957580.408      309252.877     1958015.039      309602.942
     1958416.211      309970.056
#Sta/Elev= 30
       0 1487.99    89.7 1430.13   109.6 1416.51   139.5 1393.78   199.3 1342.89
   219.2 1327.17   239.2 1313.72   259.1 1303.12     279 1295.49     299 1289.54
   328.9 1282.76   358.8    1278   398.6 1275.37   478.4    1274   518.2 1269.68
   528.2 1269.81   550.6 1273.33   565.6 1275.07     657 1282.87   676.7  1285.3
   686.6  1287.8   726.2 1300.27   745.9 1306.64   755.8 1310.71   765.7 1316.61
   805.3 1344.87   864.6 1390.29   953.6 1449.97   983.2 1468.43  1101.9 1538.32
#Mann= 3 , 0 , 0
       0      .1       0   550.6    .045       0   565.6      .1       0
Bank Sta=550.6,565.6
XS Rating Curve= 0 ,0
Exp/Cntr=0.3,0.1

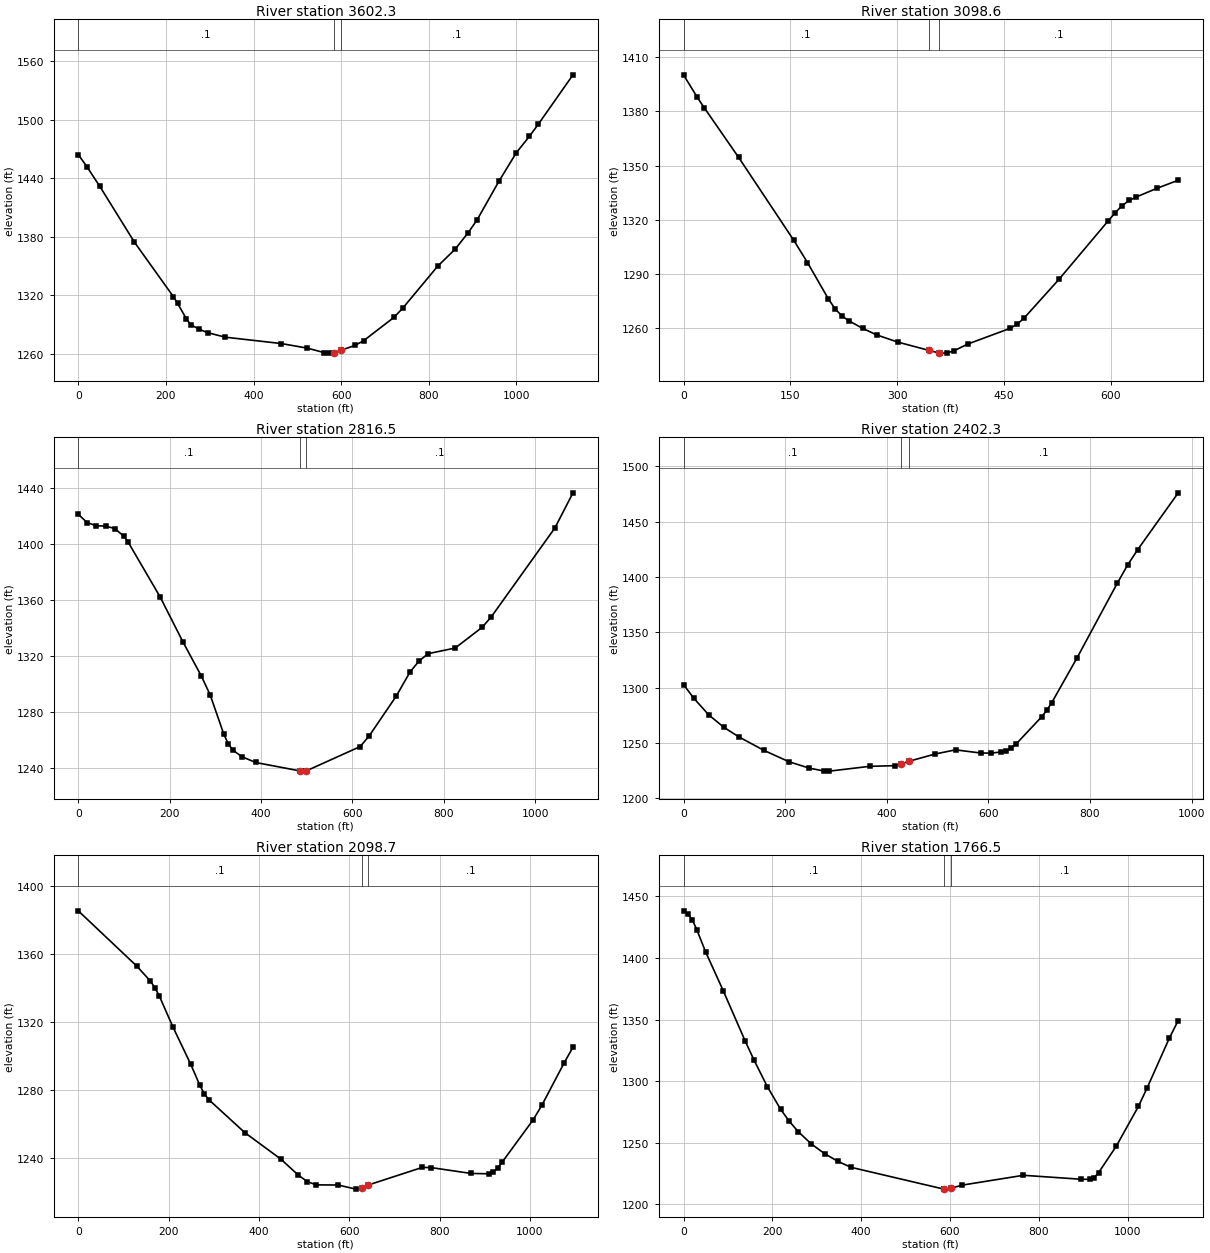
Type RM Length L Ch R = 1 ,3602.3  ,495.9,503.5,513
XS GIS Cut Line= 3
     1957519.141      309313.383     1957818.864        309823.3
     1958130.641      310261.469
#Sta/Elev= 30
       0  1464.2    19.7  1451.7    49.3 1431.48   128.2 1374.39   216.9 1318.72
   226.7 1311.69   246.4 1296.07   256.3 1289.99     276 1285.15   295.7 1281.68
   335.2 1277.08   463.3 1270.55   522.5 1265.87   561.9 1261.21   571.8 1260.73
     584 1261.27     599 1263.57   631.3 1268.59   651.2 1273.43   720.9 1297.48
   740.9 1306.95   820.5 1349.86   860.4 1367.31   890.2 1384.28   910.2 1397.18
     960 1436.71   999.8    1466  1029.7 1482.86  1049.6 1494.98  1129.2 1545.87
#Mann= 3 , 0 , 0
       0      .1       0     584    .045       0     599      .1       0
Bank Sta=584,599
XS Rating Curve= 0 ,0
Exp/Cntr=0.3,0.1

Type RM Length L Ch R = 1 ,3098.6  ,289,281.9,275.3
XS GIS Cut Line= 3
     1957255.608      309541.038     1957312.998        309785.7
     1957397.572      310220.657
#Sta/Elev= 30
       0 1400.17    19.3 1387.76      29 1382.02    77.3 1354.56   154.6 1308.78
     174 1296.38     203  1276.5   212.6 1270.86   222.3 1266.88     232 1264.21
   251.3 1260.01     271  1256.4   300.5 1252.43   343.9 1247.88   358.9 1246.36
   359.6  1246.3   369.5 1246.35   379.3 1247.53     399 1251.32   458.1 1259.96
   467.9 1262.19   477.8 1265.55     527 1287.09   595.9 1319.33   605.8 1323.87
   615.6 1327.86   625.5 1330.69   635.3 1332.59   664.9 1337.49   694.4 1341.89
#Mann= 3 , 0 , 0
       0      .1       0   343.9    .045       0   358.9      .1       0
Bank Sta=343.9,358.9
XS Rating Curve= 0 ,0
Exp/Cntr=0.3,0.1

Type RM Length L Ch R = 1 ,2816.5  ,420.1,414.2,407.1
XS GIS Cut Line= 3
     1956841.795      309550.099     1957122.704      310054.527
     1957360.077      310500.995
#Sta/Elev= 30
       0 1421.52    19.9 1415.47    39.8 1413.37    59.7 1413.09    79.6 1411.37
    99.6 1405.93   109.5 1401.46   179.2 1362.46     229 1330.39   268.8 1306.29
   288.7 1292.49   318.6 1264.34   328.5 1257.37   338.5  1252.9   358.4 1248.28
   388.2 1244.13   484.3 1238.19   487.8 1237.96   499.3 1238.16     617 1255.49
   636.9 1263.14   696.4 1291.74   726.1 1308.74   745.9 1316.64   765.8  1321.9
   825.2 1325.95   884.7  1340.9   904.6 1348.43  1043.4 1411.77    1083 1436.87
#Mann= 3 , 0 , 0
       0      .1       0   484.3    .045       0   499.3      .1       0
Bank Sta=484.3,499.3
XS Rating Curve= 0 ,0
Exp/Cntr=0.3,0.1

Type RM Length L Ch R = 1 ,2402.3  ,296.4,303.6,311.7
XS GIS Cut Line= 3
     1956517.305      309985.353     1956819.163       310299.47
     1957205.516      310673.749
#Sta/Elev= 30
       0 1302.72    19.8 1290.59    49.5 1275.38    79.2 1264.13   108.9 1255.42
   158.4 1243.18   207.9 1232.89   247.5 1227.17   277.2 1224.53   287.1 1224.46
   366.3 1228.79   415.8  1229.4   428.1 1230.98   443.1  1233.3   495.4 1239.96
   535.3  1243.7   585.1 1240.81     605 1240.76   624.9 1241.73   634.9 1242.54
   644.8 1245.07   654.8 1249.12   704.6 1273.44   714.6 1279.28   724.5 1286.22
   774.3 1326.71     854 1394.64     874 1410.79   893.9 1424.75   973.6 1476.06
#Mann= 3 , 0 , 0
       0      .1       0   428.1    .045       0   443.1      .1       0
Bank Sta=428.1,443.1
XS Rating Curve= 0 ,0
Exp/Cntr=0.3,0.1

Type RM Length L Ch R = 1 ,2098.7  ,320.6,332.2,343.9
XS GIS Cut Line= 4
     1956433.262      309832.977     1956483.965      310278.393
     1956610.306      310553.886     1956771.741      310857.455
#Sta/Elev= 30
       0 1385.62   129.5 1353.04   159.4 1344.31   169.4 1340.39   179.3 1335.48
   209.2 1317.35     249 1295.16     269 1282.87   278.9 1277.76   288.9 1274.34
   368.6 1254.91   448.3 1239.31   487.4 1229.78     507 1226.06   526.5  1224.1
   575.4 1224.01   614.5 1221.59   627.2 1222.35   642.2 1224.04   761.2 1234.36
   780.8  1234.3   869.3 1230.84   908.6 1230.63   918.4 1231.58   928.2 1233.94
     938 1237.35  1006.8 1262.36  1026.4 1271.07  1075.6 1295.98  1095.2 1305.28
#Mann= 3 , 0 , 0
       0      .1       0   627.2    .045       0   642.2      .1       0
Bank Sta=627.2,642.2
XS Rating Curve= 0 ,0
Exp/Cntr=0.3,0.1

Type RM Length L Ch R = 1 ,1766.5  ,666.8,665.9,665.1
XS GIS Cut Line= 3
     1956348.378       309831.51     1956252.792      310196.492
     1956192.381      310930.481
#Sta/Elev= 30
       0  1438.3     9.9 1435.98    19.9 1430.92    29.8 1423.08    49.6  1405.1
    89.4 1373.46     139 1332.47   158.9    1317   188.6 1295.65   218.4 1277.28
   238.3 1267.38   258.2 1259.04   287.9 1248.99   317.7 1241.16   347.5 1234.91
   377.3 1230.05   586.3 1212.36     587 1212.36     602 1212.96   626.1 1215.54
   765.4 1223.59   894.8 1220.39   914.7 1220.32   924.7 1221.78   934.6 1225.81
   974.4 1247.27  1024.2 1279.56  1044.1 1294.77  1093.9 1335.04  1113.8 1349.26
#Mann= 3 , 0 , 0
       0      .1       0     587    .045       0     602      .1       0
Bank Sta=587,602
XS Rating Curve= 0 ,0
Exp/Cntr=0.3,0.1