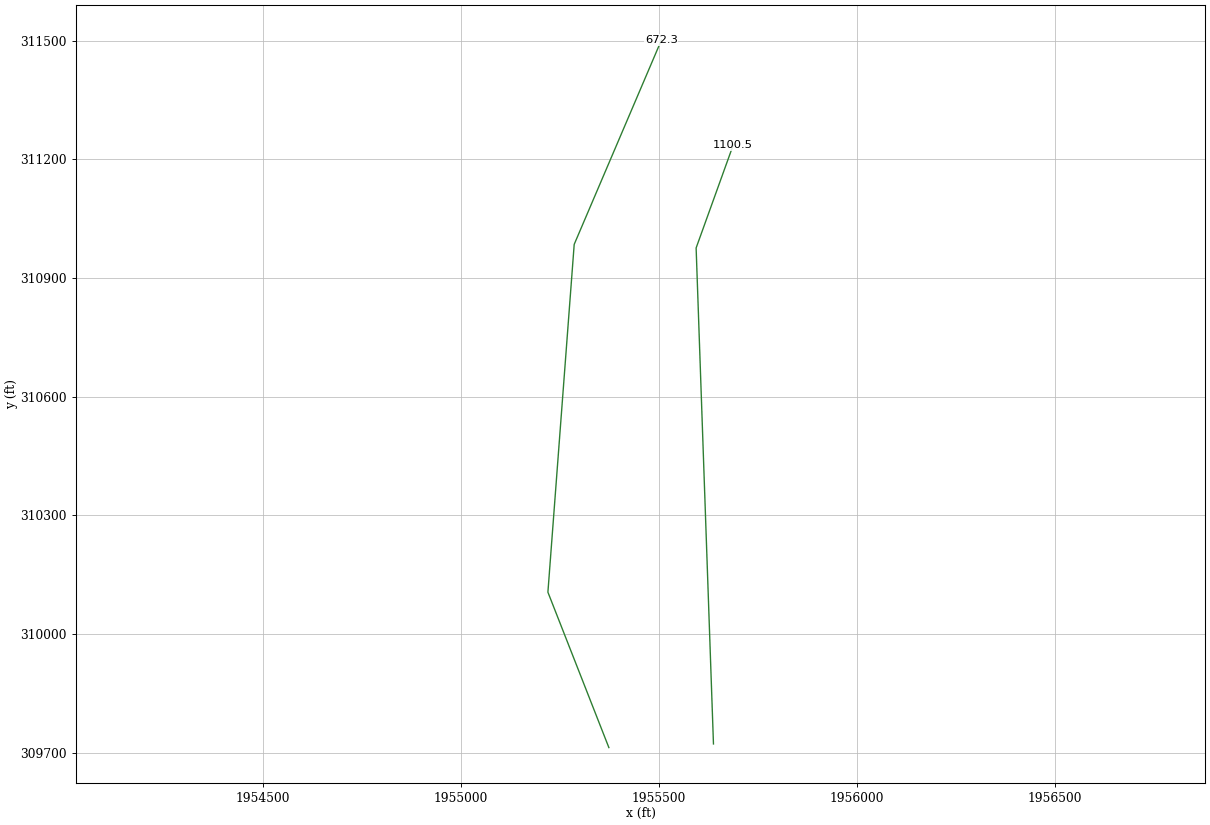
HEC-RAS study LaurelCrk.prj: LaurelCrk

--- LaurelCrk.g01 (geometry) --- (continued)

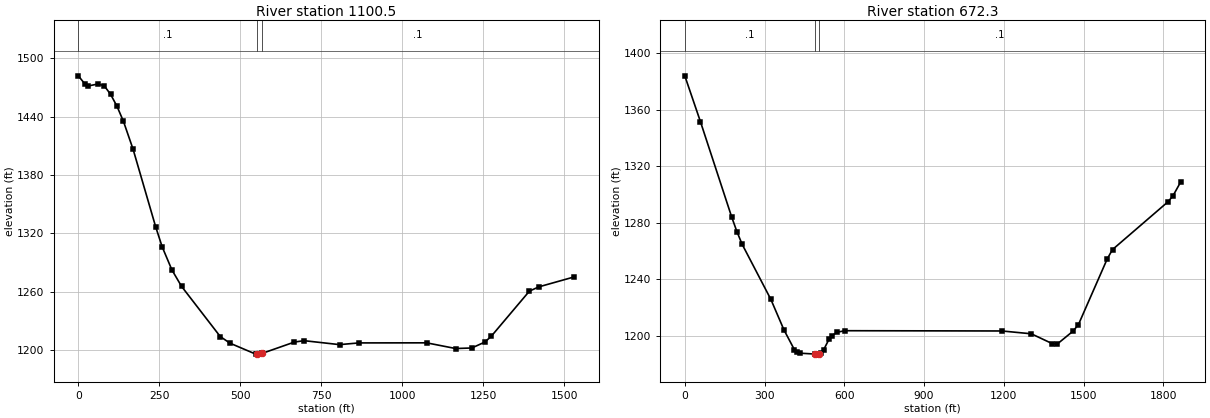
Type RM Length L Ch R = 1 ,1100.5  ,434.3,428.2,421.7
XS GIS Cut Line= 3
     1955638.143      309722.382     1955594.317      310975.789
     1955687.953      311235.554
#Sta/Elev= 30
       0  1481.9    19.9 1473.66    29.9 1471.45    59.7 1473.43    79.6  1471.8
    99.5 1462.91   119.4 1450.52   139.4 1434.96   169.2 1406.17   238.9 1326.42
   258.8 1306.05   288.7 1282.42   318.5 1265.45     438 1213.86   467.8 1207.05
   547.5 1195.76     552 1195.76     567 1196.49   666.9 1208.17   696.8 1209.59
   806.2 1205.53     866 1207.29    1075 1207.37  1164.6 1201.51  1214.4 1202.08
  1254.2 1208.09  1273.9  1213.9  1392.2 1260.56  1421.8 1264.98  1530.3 1275.14
#Mann= 3 , 0 , 0
       0      .1       0     552    .045       0     567      .1       0
Bank Sta=552,567
XS Rating Curve= 0 ,0
Exp/Cntr=0.3,0.1

Type RM Length L Ch R = 1 ,672.3   ,679.8,672.3,665
XS GIS Cut Line= 4
     1955373.818      309713.208     1955219.771      310105.876
     1955286.223       310984.85     1955506.721      311501.361
#Sta/Elev= 30
       0 1384.07    58.9  1351.6   176.6 1284.05   196.2 1273.74   215.8 1264.84
   323.7  1225.9   372.8 1204.38     412 1190.39   421.8 1188.38   431.8 1187.86
   488.6 1187.23   491.9 1187.17   503.6 1187.34     512 1187.91     522 1190.16
     542 1197.54     552 1200.01   572.1 1202.63   602.1 1203.74  1193.1 1203.55
  1303.3 1201.56  1382.1 1194.59  1401.8 1194.45  1460.9 1203.53  1480.6 1208.09
    1589  1254.6  1608.7 1261.15  1815.6 1294.67  1835.3  1298.9  1864.9  1308.9
#Mann= 3 , 0 , 0
       0      .1       0   488.6    .045       0   503.6      .1       0
Bank Sta=488.6,503.6
XS Rating Curve= 0 ,0
Exp/Cntr=0.3,0.1

Chan Stop Cuts=-1
Use User Specified Reach Order=0
Composite Channel Slope=5